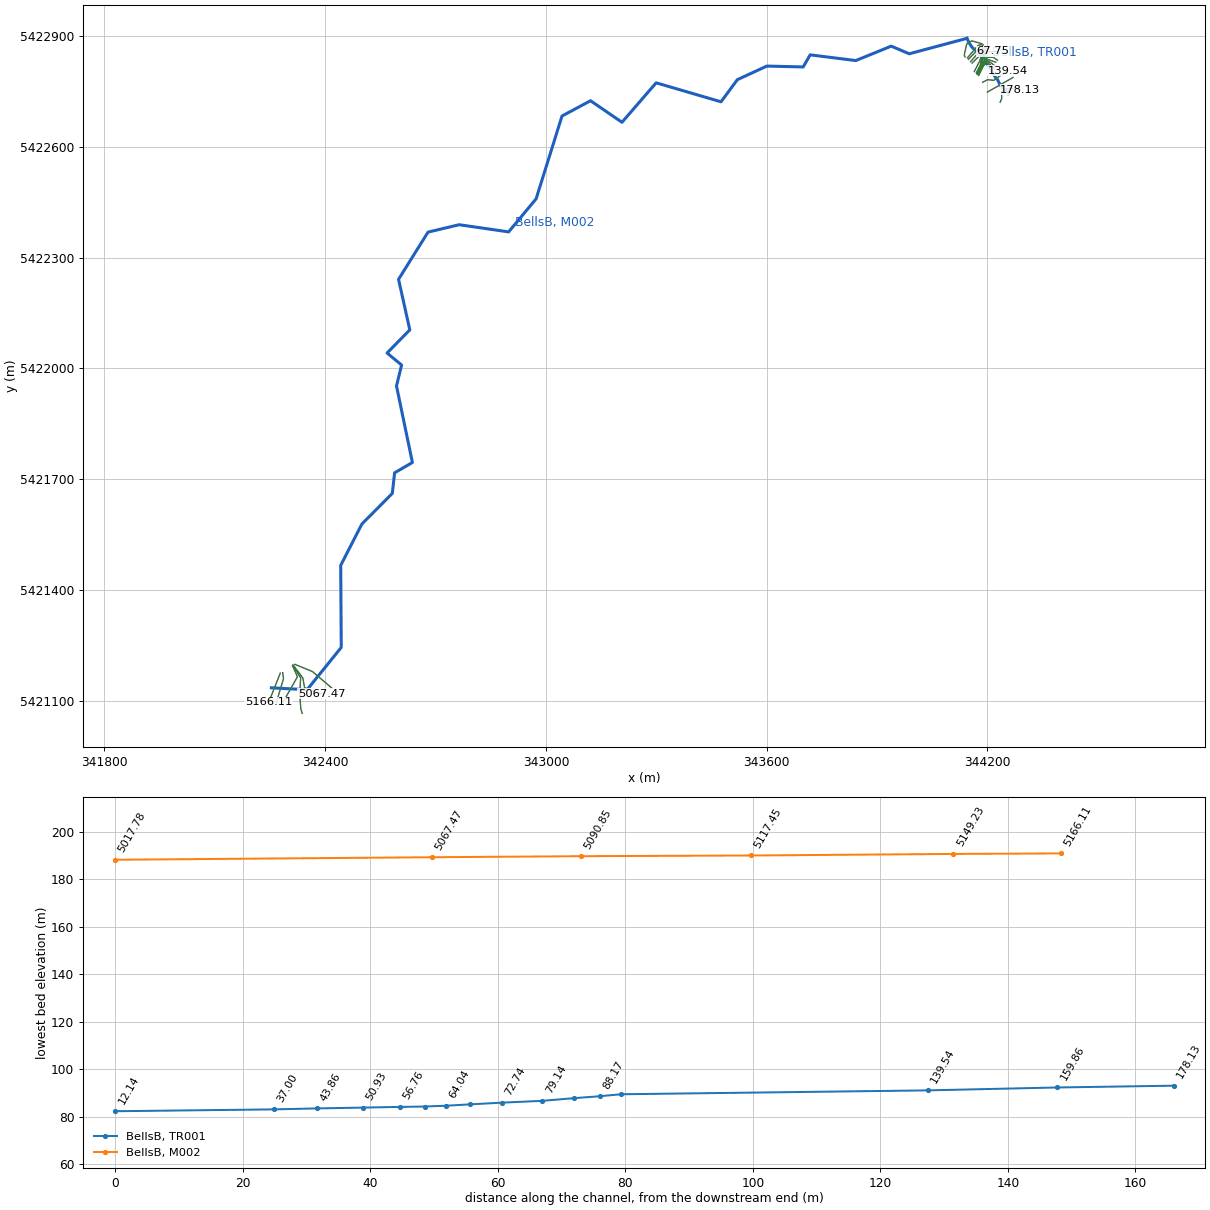
HEC-RAS study Corner_Brook2.prj: Corner_Brook2

--- Corner_Brook2.f03 (steady flow) ---

Flow Title=100yr-2013
Program Version=4.10
Number of Profiles= 5
Profile Names=100-Existing,AMEC-100-2020-Max,AMEC-100-2050-Max,FINNIS-100-2050-Max,AMEC-100-2080-Max
River Rch & RM=BellsB,TR001           ,178.13
    17.7    19.8    20.1    41.7    21.4
River Rch & RM=BellsB,M002            ,5166.11
    14.6    16.2    16.4    33.4    17.4
River Rch & RM=BellsB,M002            ,4436.28
    26.5    29.3    29.7    59.7    31.1
River Rch & RM=BellsB,M002            ,3329.08
    33.4    37.1    37.6    75.2    39.9
River Rch & RM=BellsB,M002            ,2295.83
    35.9    39.9    40.5      81    43.1
River Rch & RM=BellsB,M001            ,1582.05
    57.2    63.7    64.6   130.2    68.8
River Rch & RM=BellsB,M001            ,816.09
    58.5    65.2    66.2   133.2    70.5
River Rch & RM=CornerB,M004            ,2888.71
   178.7   201.5   203.8   422.4   215.4
River Rch & RM=CornerB,TR001           ,206.04
    32.1      36    36.6    75.6    38.8
River Rch & RM=CornerB,M003            ,2689.92
   196.3   222.8   225.2   471.5   237.4
River Rch & RM=CornerB,M003            ,2267.71
   196.6   223.3   225.7   472.6   237.9
River Rch & RM=CornerB,TR002           ,21.04
    12.2    13.5    13.7    27.6    14.5
River Rch & RM=CornerB,M002            ,1826.39
   198.6   225.8   228.2   477.8   240.3
River Rch & RM=CornerB,M002            ,1539.91
   197.5   224.6   227.2   477.9   238.9
River Rch & RM=CornerB,M002            ,915.75
   196.6   223.8   226.4   477.9     238
River Rch & RM=CornerB,M002            ,828.33
   190.8   217.9   220.4   470.5   231.8
River Rch & RM=CornerB,M001            ,659.37
     201   230.7   233.5     500   244.9
Boundary for River Rch & Prof#=BellsB,TR001           , 1
Up Type= 3
Up Slope=0.043
Dn Type= 0
Boundary for River Rch & Prof#=BellsB,TR001           , 2
Up Type= 3
Up Slope=0.043
Dn Type= 0
Boundary for River Rch & Prof#=BellsB,TR001           , 3
Up Type= 3
Up Slope=0.043
Dn Type= 0
Boundary for River Rch & Prof#=BellsB,TR001           , 4
Up Type= 3
Up Slope=0.043
Dn Type= 0
Boundary for River Rch & Prof#=BellsB,TR001           , 5
Up Type= 3
Up Slope=0.043
Dn Type= 0
Boundary for River Rch & Prof#=BellsB,M002            , 1
Up Type= 3
Up Slope=0.013
Dn Type= 0
Boundary for River Rch & Prof#=BellsB,M002            , 2
Up Type= 3
Up Slope=0.013
Dn Type= 0
Boundary for River Rch & Prof#=BellsB,M002            , 3
Up Type= 3
Up Slope=0.013
Dn Type= 0
Boundary for River Rch & Prof#=BellsB,M002            , 4
Up Type= 3
Up Slope=0.013
Dn Type= 0
Boundary for River Rch & Prof#=BellsB,M002            , 5
Up Type= 3
Up Slope=0.013
Dn Type= 0
Boundary for River Rch & Prof#=BellsB,M001            , 1
Up Type= 0
Dn Type= 0
Boundary for River Rch & Prof#=BellsB,M001            , 2
Up Type= 0
Dn Type= 0
Boundary for River Rch & Prof#=BellsB,M001            , 3
Up Type= 0
Dn Type= 0
Boundary for River Rch & Prof#=BellsB,M001            , 4
Up Type= 0
Dn Type= 0
Boundary for River Rch & Prof#=BellsB,M001            , 5
Up Type= 0
Dn Type= 0
Boundary for River Rch & Prof#=CornerB,M004            , 1
Up Type= 3
Up Slope=0.006
Dn Type= 0
Boundary for River Rch & Prof#=CornerB,M004            , 2
Up Type= 3
Up Slope=0.006
Dn Type= 0
Boundary for River Rch & Prof#=CornerB,M004            , 3
Up Type= 3
Up Slope=0.006
Dn Type= 0
Boundary for River Rch & Prof#=CornerB,M004            , 4
Up Type= 3
Up Slope=0.006
Dn Type= 0
Boundary for River Rch & Prof#=CornerB,M004            , 5
Up Type= 3
Up Slope=0.006
Dn Type= 0
Boundary for River Rch & Prof#=CornerB,TR001           , 1
Up Type= 3
Up Slope=0.042
Dn Type= 0
Boundary for River Rch & Prof#=CornerB,TR001           , 2
Up Type= 3
Up Slope=0.042
Dn Type= 0
Boundary for River Rch & Prof#=CornerB,TR001           , 3
Up Type= 3
Up Slope=0.042
Dn Type= 0
Boundary for River Rch & Prof#=CornerB,TR001           , 4
Up Type= 3
Up Slope=0.042
Dn Type= 0
Boundary for River Rch & Prof#=CornerB,TR001           , 5
Up Type= 3
Up Slope=0.042
Dn Type= 0
Boundary for River Rch & Prof#=CornerB,M003            , 1
Up Type= 0
Dn Type= 0
Boundary for River Rch & Prof#=CornerB,M003            , 2
Up Type= 0
Dn Type= 0
Boundary for River Rch & Prof#=CornerB,M003            , 3
Up Type= 0
Dn Type= 0
Boundary for River Rch & Prof#=CornerB,M003            , 4
Up Type= 0
Dn Type= 0
Boundary for River Rch & Prof#=CornerB,M003            , 5
Up Type= 0
Dn Type= 0
Boundary for River Rch & Prof#=CornerB,TR002           , 1
Up Type= 3
Up Slope=0.15
Dn Type= 0
Boundary for River Rch & Prof#=CornerB,TR002           , 2
Up Type= 3
Up Slope=0.15
Dn Type= 0
Boundary for River Rch & Prof#=CornerB,TR002           , 3
Up Type= 3
Up Slope=0.15
Dn Type= 0
Boundary for River Rch & Prof#=CornerB,TR002           , 4
Up Type= 3
Up Slope=0.15
Dn Type= 0
Boundary for River Rch & Prof#=CornerB,TR002           , 5
Up Type= 3
Up Slope=0.15
Dn Type= 0
Boundary for River Rch & Prof#=CornerB,M002            , 1
Up Type= 0
Dn Type= 0
Boundary for River Rch & Prof#=CornerB,M002            , 2
Up Type= 0
Dn Type= 0
Boundary for River Rch & Prof#=CornerB,M002            , 3
Up Type= 0
Dn Type= 0
Boundary for River Rch & Prof#=CornerB,M002            , 4
Up Type= 0
Dn Type= 0
Boundary for River Rch & Prof#=CornerB,M002            , 5
Up Type= 0
Dn Type= 0
Boundary for River Rch & Prof#=CornerB,M001            , 1
Up Type= 0
Dn Type= 1
Dn Known WS=2.8
Boundary for River Rch & Prof#=CornerB,M001            , 2
Up Type= 0
Dn Type= 1
Dn Known WS=2.85
Boundary for River Rch & Prof#=CornerB,M001            , 3
Up Type= 0
Dn Type= 1
Dn Known WS=3.03
Boundary for River Rch & Prof#=CornerB,M001            , 4
Up Type= 0
Dn Type= 1
Dn Known WS=3.03
Boundary for River Rch & Prof#=CornerB,M001            , 5
Up Type= 0
Dn Type= 1
Dn Known WS=3.36
Gate Openings=CornerB         ,M003            ,2263.0  ,Gate #1     ,
   2.134       0   2.134       0   2.134       0   2.134       0   2.134       0
DSS Import GetInterval= 0
DSS Import GetPeak= 0
DSS Import FillOption= 0

--- Corner_Brook2.f04 (steady flow) ---

Flow Title=20yr-2013
Program Version=4.10
Number of Profiles= 5
Profile Names=20-Existing,AMEC-20-2020-Max,AMEC-20-2050-Max,FINNIS-20-2050-Max,AMEC-20-2080-Max
River Rch & RM=BellsB,TR001           ,178.13
    12.5    14.8      15    28.6      16
River Rch & RM=BellsB,M002            ,5166.11
    10.4    12.2    12.3    23.1    12.2
River Rch & RM=BellsB,M002            ,4436.28
    18.8    21.9    22.2      41    21.9
River Rch & RM=BellsB,M002            ,3329.08
    23.8    27.5      28    51.1    27.5
River Rch & RM=BellsB,M002            ,2295.83
      26    29.6    30.1    54.8    29.6
River Rch & RM=BellsB,M001            ,1582.05
    41.3    47.3      48    88.3    47.3
River Rch & RM=BellsB,M001            ,816.09
    42.5    48.4    49.2    90.4    48.4
River Rch & RM=CornerB,M004            ,2888.71
   127.5   152.9   154.6     294   152.9
River Rch & RM=CornerB,TR001           ,206.04
    22.9    27.3    27.6    52.4    27.3
River Rch & RM=CornerB,M003            ,2689.92
   140.1   168.1     170   326.9   168.1
River Rch & RM=CornerB,M003            ,2267.71
   140.5   168.5   170.4   327.7   168.5
River Rch & RM=CornerB,TR002           ,21.04
     8.7    10.1    10.3    19.1    10.1
River Rch & RM=CornerB,M002            ,1826.39
     142   170.3   172.2   331.5   170.3
River Rch & RM=CornerB,M002            ,1539.91
   141.5   169.6   171.4   331.4   169.6
River Rch & RM=CornerB,M002            ,915.75
   140.7   168.8   170.6     331   168.8
River Rch & RM=CornerB,M002            ,828.33
   135.9   163.8   165.5   324.3   163.8
River Rch & RM=CornerB,M001            ,659.37
   142.9   173.3     175   344.8   173.3
Boundary for River Rch & Prof#=BellsB,TR001           , 1
Up Type= 3
Up Slope=0.043
Dn Type= 0
Boundary for River Rch & Prof#=BellsB,TR001           , 2
Up Type= 3
Up Slope=0.043
Dn Type= 0
Boundary for River Rch & Prof#=BellsB,TR001           , 3
Up Type= 3
Up Slope=0.043
Dn Type= 0
Boundary for River Rch & Prof#=BellsB,TR001           , 4
Up Type= 3
Up Slope=0.043
Dn Type= 0
Boundary for River Rch & Prof#=BellsB,TR001           , 5
Up Type= 3
Up Slope=0.043
Dn Type= 0
Boundary for River Rch & Prof#=BellsB,M002            , 1
Up Type= 3
Up Slope=0.013
Dn Type= 0
Boundary for River Rch & Prof#=BellsB,M002            , 2
Up Type= 3
Up Slope=0.013
Dn Type= 0
Boundary for River Rch & Prof#=BellsB,M002            , 3
Up Type= 3
Up Slope=0.013
Dn Type= 0
Boundary for River Rch & Prof#=BellsB,M002            , 4
Up Type= 3
Up Slope=0.013
Dn Type= 0
Boundary for River Rch & Prof#=BellsB,M002            , 5
Up Type= 3
Up Slope=0.013
Dn Type= 0
Boundary for River Rch & Prof#=BellsB,M001            , 1
Up Type= 0
Dn Type= 0
Boundary for River Rch & Prof#=BellsB,M001            , 2
Up Type= 0
Dn Type= 0
Boundary for River Rch & Prof#=BellsB,M001            , 3
Up Type= 0
Dn Type= 0
Boundary for River Rch & Prof#=BellsB,M001            , 4
Up Type= 0
Dn Type= 0
Boundary for River Rch & Prof#=BellsB,M001            , 5
Up Type= 0
Dn Type= 0
Boundary for River Rch & Prof#=CornerB,M004            , 1
Up Type= 3
Up Slope=0.006
Dn Type= 0
Boundary for River Rch & Prof#=CornerB,M004            , 2
Up Type= 3
Up Slope=0.006
Dn Type= 0
Boundary for River Rch & Prof#=CornerB,M004            , 3
Up Type= 3
Up Slope=0.006
Dn Type= 0
Boundary for River Rch & Prof#=CornerB,M004            , 4
Up Type= 3
Up Slope=0.006
Dn Type= 0
Boundary for River Rch & Prof#=CornerB,M004            , 5
Up Type= 3
Up Slope=0.006
Dn Type= 0
Boundary for River Rch & Prof#=CornerB,TR001           , 1
Up Type= 3
Up Slope=0.042
Dn Type= 0
Boundary for River Rch & Prof#=CornerB,TR001           , 2
Up Type= 3
Up Slope=0.042
Dn Type= 0
Boundary for River Rch & Prof#=CornerB,TR001           , 3
Up Type= 3
Up Slope=0.042
Dn Type= 0
Boundary for River Rch & Prof#=CornerB,TR001           , 4
Up Type= 3
Up Slope=0.042
Dn Type= 0
Boundary for River Rch & Prof#=CornerB,TR001           , 5
Up Type= 3
Up Slope=0.042
Dn Type= 0
Boundary for River Rch & Prof#=CornerB,M003            , 1
Up Type= 0
Dn Type= 0
Boundary for River Rch & Prof#=CornerB,M003            , 2
Up Type= 0
Dn Type= 0
Boundary for River Rch & Prof#=CornerB,M003            , 3
Up Type= 0
Dn Type= 0
Boundary for River Rch & Prof#=CornerB,M003            , 4
Up Type= 0
Dn Type= 0
Boundary for River Rch & Prof#=CornerB,M003            , 5
Up Type= 0
Dn Type= 0
Boundary for River Rch & Prof#=CornerB,TR002           , 1
Up Type= 3
Up Slope=0.15
Dn Type= 0
Boundary for River Rch & Prof#=CornerB,TR002           , 2
Up Type= 3
Up Slope=0.15
Dn Type= 0
Boundary for River Rch & Prof#=CornerB,TR002           , 3
Up Type= 3
Up Slope=0.15
Dn Type= 0
Boundary for River Rch & Prof#=CornerB,TR002           , 4
Up Type= 3
Up Slope=0.15
Dn Type= 0
Boundary for River Rch & Prof#=CornerB,TR002           , 5
Up Type= 3
Up Slope=0.15
Dn Type= 0
Boundary for River Rch & Prof#=CornerB,M002            , 1
Up Type= 0
Dn Type= 0
Boundary for River Rch & Prof#=CornerB,M002            , 2
Up Type= 0
Dn Type= 0
Boundary for River Rch & Prof#=CornerB,M002            , 3
Up Type= 0
Dn Type= 0
Boundary for River Rch & Prof#=CornerB,M002            , 4
Up Type= 0
Dn Type= 0
Boundary for River Rch & Prof#=CornerB,M002            , 5
Up Type= 0
Dn Type= 0
Boundary for River Rch & Prof#=CornerB,M001            , 1
Up Type= 0
Dn Type= 1
Dn Known WS=2.8
Boundary for River Rch & Prof#=CornerB,M001            , 2
Up Type= 0
Dn Type= 1
Dn Known WS=2.85
Boundary for River Rch & Prof#=CornerB,M001            , 3
Up Type= 0
Dn Type= 1
Dn Known WS=3.03
Boundary for River Rch & Prof#=CornerB,M001            , 4
Up Type= 0
Dn Type= 1
Dn Known WS=3.03
Boundary for River Rch & Prof#=CornerB,M001            , 5
Up Type= 0
Dn Type= 1
Dn Known WS=3.36
Gate Openings=CornerB         ,M003            ,2263.0  ,Gate #1     ,
   2.134       0   2.134       0   2.134       0   2.134       0   2.134       0
DSS Import GetInterval= 0
DSS Import GetPeak= 0
DSS Import FillOption= 0

--- Corner_Brook2.g01 (geometry) ---

Geom Title=CB_no_below_waterline
Program Version=4.10
BEGIN GEOM DESCRIPTION:
Created based on a TIN with 1 z tolerance
END GEOM DESCRIPTION:

Junct Name=1
Junct Desc=, 0 , 0 ,-1 ,0
Up River,Reach=CornerB         ,M002
Up River,Reach=BellsB          ,M001
Dn River,Reach=CornerB         ,M001
Junc L&A=29.8,
Junc L&A=20.5,0

Junct Name=3
Junct Desc=, 0 , 0 ,-1 ,0
Up River,Reach=CornerB         ,M003
Up River,Reach=CornerB         ,TR002
Dn River,Reach=CornerB         ,M002
Junc L&A=46.25,
Junc L&A=18.08,0

Junct Name=5
Junct Desc=, 0 , 0 ,-1 ,0
Up River,Reach=CornerB         ,M004
Up River,Reach=CornerB         ,TR001
Dn River,Reach=CornerB         ,M003
Junc L&A=42.09,
Junc L&A=21.3,0

Junct Name=8
Junct Desc=, 0 , 0 ,-1 ,0
Up River,Reach=BellsB          ,M002
Up River,Reach=BellsB          ,TR001
Dn River,Reach=BellsB          ,M001
Junc L&A=6.47,
Junc L&A=12.15,

River Reach=BellsB          ,TR001
Reach XY= 21
344257.073913574 5422744.4309082344255.4655151375422747.44512939
344251.8466796885422749.35412598344246.4182739265422753.37310791
 344240.386718755422759.60247803344234.2293090825422768.79211426
 344229.40411377 5422778.1362915 344227.293090825422782.85852051
344223.7747192385422785.47088623344199.6320800785422823.99731445
344195.6109008795422830.12628174344194.1030883795422839.06848145
344192.3941040045422845.09710693344189.9815063485422849.01568604
344186.3624877935422852.13031006344177.4935302735422855.59729004
344168.0441284185422861.22387695344159.0972900395422868.85992432
344152.8646850595422877.60131836344149.5474853525422883.42871094
344144.2833251955422894.11730957

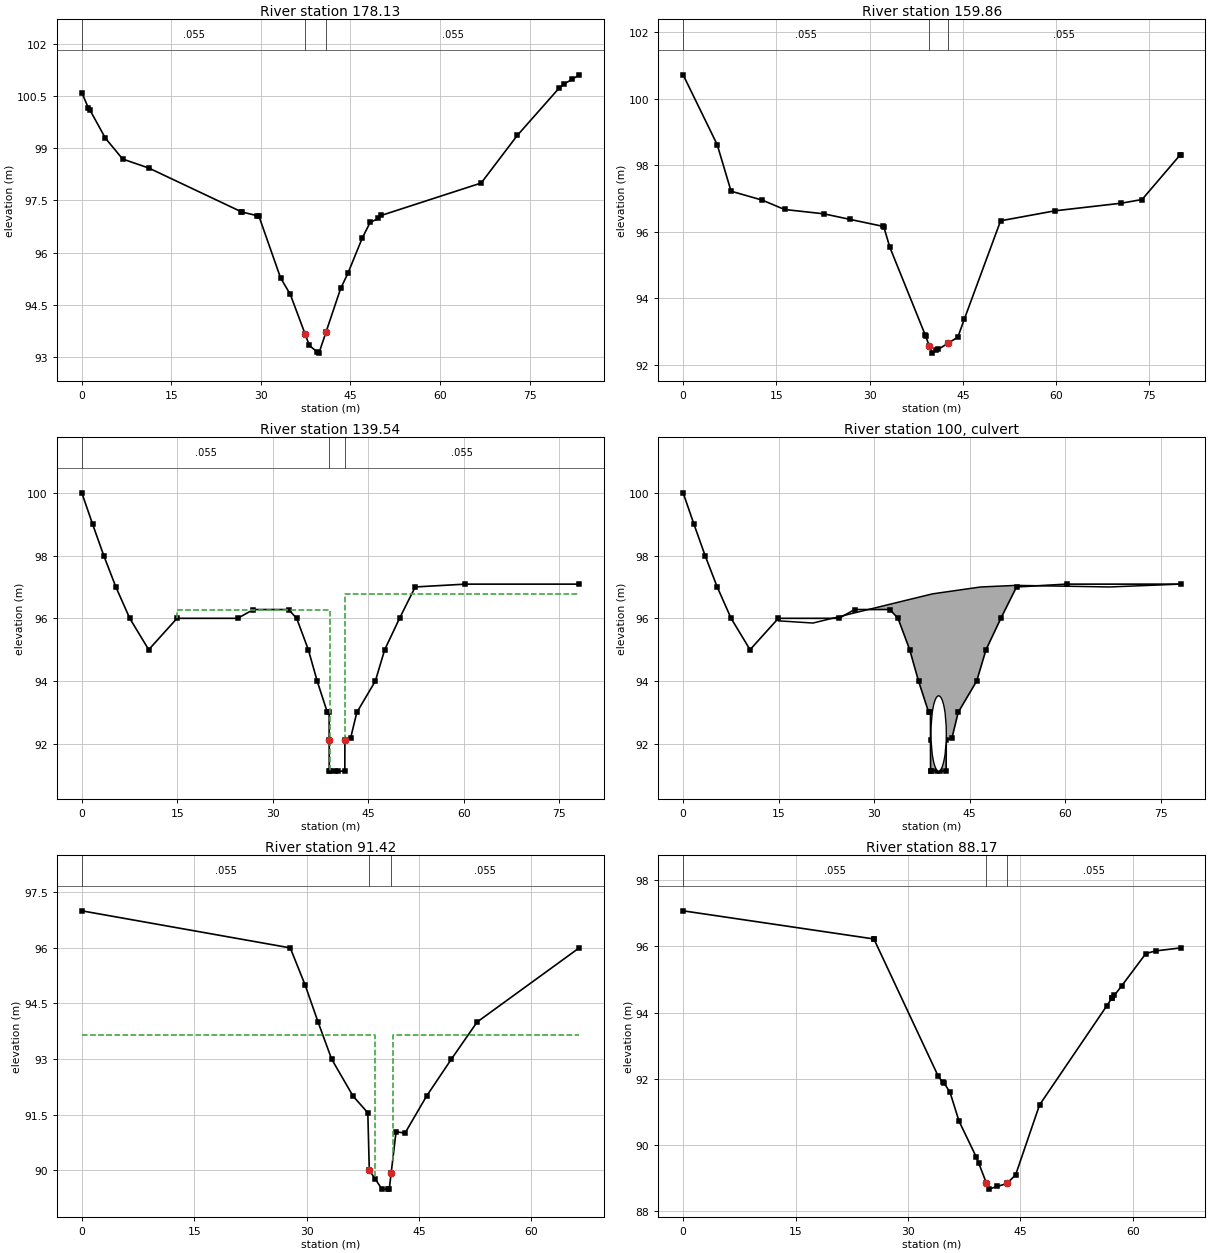
Type RM Length L Ch R = 1 ,178.13  ,18.25,18.27,18.06
XS GIS Cut Line= 6
344234.4996948245422720.95068359344238.9260864265422731.27270508
344238.0407104495422749.41009521344253.2380981455422758.25750732
344279.2062988285422758.69989014344288.9442749025422755.16088867
#Sta/Elev= 29
       0   100.6    1.07  100.17    1.36   100.1    3.95   99.29    6.84   98.69
   11.23   98.43   26.64   97.18   26.75   97.17   29.39   97.06   29.64   97.06
    33.3   95.27   34.92    94.8    37.4   93.66   38.11   93.33   39.46   93.14
   39.72   93.11   40.89  93.708   43.36   94.97   44.56    95.4   46.98   96.42
    48.3   96.87   49.69   96.98   50.19   97.07   66.89      98   72.95   99.37
    79.9  100.72   80.71  100.84   82.12  100.98   83.31  101.11
#Mann= 3 , 0 , 0
       0    .055       0    37.4    .035       0   40.89    .055       0
Bank Sta=37.4,40.89
XS Rating Curve= 0 ,0
Exp/Cntr=0.3,0.1

Type RM Length L Ch R = 1 ,159.86  ,19.69,20.32,20.7
XS GIS Cut Line= 2
344199.8156738285422748.48608398344269.362304688 5422788.0244751
#Sta/Elev= 25
       0  100.72    5.48   98.62    7.71   97.22   12.75   96.95   16.31   96.67
   22.63   96.54   26.89   96.37   32.21   96.16   32.29   96.14   33.23   95.54
   38.95   92.89      39   92.86   39.61   92.56   40.09   92.35   40.73   92.43
      41   92.46   42.58  92.644   44.18   92.83   45.24   93.38   51.06   96.33
   59.79   96.63    70.5   96.86   73.81   96.97   79.98   98.32      80   98.32
#Mann= 3 , 0 , 0
       0    .055       0   39.61    .035       0   42.58    .055       0
Bank Sta=39.61,42.58
XS Rating Curve= 0 ,0
Exp/Cntr=0.3,0.1

Type RM Length L Ch R = 1 ,139.54  ,49.06,48.13,33.83
XS GIS Cut Line= 5
       344187.04     5422775.179      344200.338      5422782.01
      344217.269     5422780.434      344217.269     5422780.434
      344255.016     5422806.982
#Sta/Elev= 30
       0     100     1.7      99    3.45      98    5.35      97    7.53      96
   10.51      95   14.95      96   24.47      96   26.94   96.28   32.46   96.28
   33.74      96   35.57      95   36.96      94   38.56      93   38.84   93.02
  38.845   92.11   38.85   91.14   38.92   91.14   39.81   91.14   40.26   91.13
    41.3   91.13   41.31   92.11   42.23    92.2   43.18      93   46.09      94
   47.56      95   49.89      96   52.35      97   60.24   97.09    78.1   97.09
#Mann= 3 , 0 , 0
       0    .055       0  38.845    .035       0   41.31    .055       0
#XS Ineff= 2 , 0
   14.95   38.92   96.28   41.32   14.95   96.78
Permanent Ineff=
       F       F
Bank Sta=38.845,41.31
XS Rating Curve= 0 ,0
Exp/Cntr=0.5,0.3

Type RM Length L Ch R = 2 ,100     ,,,
BEGIN DESCRIPTION:
O'Connell Drive/Mount Batten Road (Structure #2130)
END DESCRIPTION:
Bridge Culvert--1,0,-1,-1, 0
Deck Dist Width WeirC Skew NumUp NumDn MinLoCord MaxHiCord MaxSubmerge Is_Ogee
12,19.2,1.67,0, 7, 8, 95, , 0.98, 0, 0.73,0.57,,
   14.95   20.39   39.15   46.73   52.28   66.99    78.1
   95.92   95.85   96.78      97   97.05      97   97.09
                                                        
       0   19.48   28.32   36.51   40.19   45.24   49.91   66.38
      97   95.92   95.85      96      96   95.71   95.42      97
                                                                
BR Coef=-1 , 0 , 0 ,, 0 ,,,0.8,-1,,0,
WSPro=,,,, 1 ,,,, 0 ,,,, 0 ,,,,-1 ,-1 ,-1 , 0 , 0 , 0 , 0 , 0
Culvert=1,2.4,,44.2,0.03,0.7,1,2,2,91.13,40.12,89.49,40.27,Culvert #1  , 0 ,1.4
Culvert Bottom n=0.03
BC Design=,, 0 ,, 0 ,,,,,,
BC Use User HTab Curves=0
BC User HTab FreeFlow(D)= 0

Type RM Length L Ch R = 1 ,91.42   ,3.23,3.25,0.95
XS GIS Cut Line= 6
344176.3275146485422793.74768066344187.5899047855422816.60327148
344192.6146850595422823.52929688344201.1046752935422826.99230957
344212.5405273445422816.77648926344218.2583007815422811.40887451
#Sta/Elev= 19
       0      97   27.82      96    29.8      95   31.53      94   33.34      93
    36.2      92   38.17   91.55   38.37      90   39.17  89.759   40.06   89.49
   40.82   89.49   41.03   89.49   41.29  89.933   41.94   91.04   43.13      91
   46.01      92   49.33      93   52.76      94   66.38      96
#Mann= 3 , 0 , 0
       0    .055       0   38.37    .035       0   41.29    .055       0
#XS Ineff= 2 , 0
       0   39.07   93.65   41.47       0   93.65
Permanent Ineff=
       F       F
Bank Sta=38.37,41.29
XS Rating Curve= 0 ,0
Exp/Cntr=0.5,0.3

Type RM Length L Ch R = 1 ,88.17   ,2.5,4.05,10.03
XS GIS Cut Line= 6
344174.2482910165422796.34509277344185.5106811525422819.20068359
344190.5355224615422826.12652588344199.0255126955422829.58947754
344210.4613037115422819.37371826344216.1790771485422814.00610352
#Sta/Elev= 24
       0   97.07   25.47   96.22   25.48   96.21   34.04   92.08   34.66   91.89
   34.86   91.86   35.62   91.59   36.82   90.72   39.14   89.63   39.42   89.47
   40.45  88.864   40.78   88.67   41.92   88.75   43.21   88.84   44.37    89.1
   47.56   91.21    56.5   94.19   57.23   94.44   57.28   94.45   57.55   94.52
   58.54   94.81   61.75   95.78   63.05   95.86   66.38   95.95
#Mann= 3 , 0 , 0
       0    .055       0   40.45    .035       0   43.21    .055       0
Bank Sta=40.45,43.21
XS Rating Curve= 0 ,0
Exp/Cntr=0.3,0.1

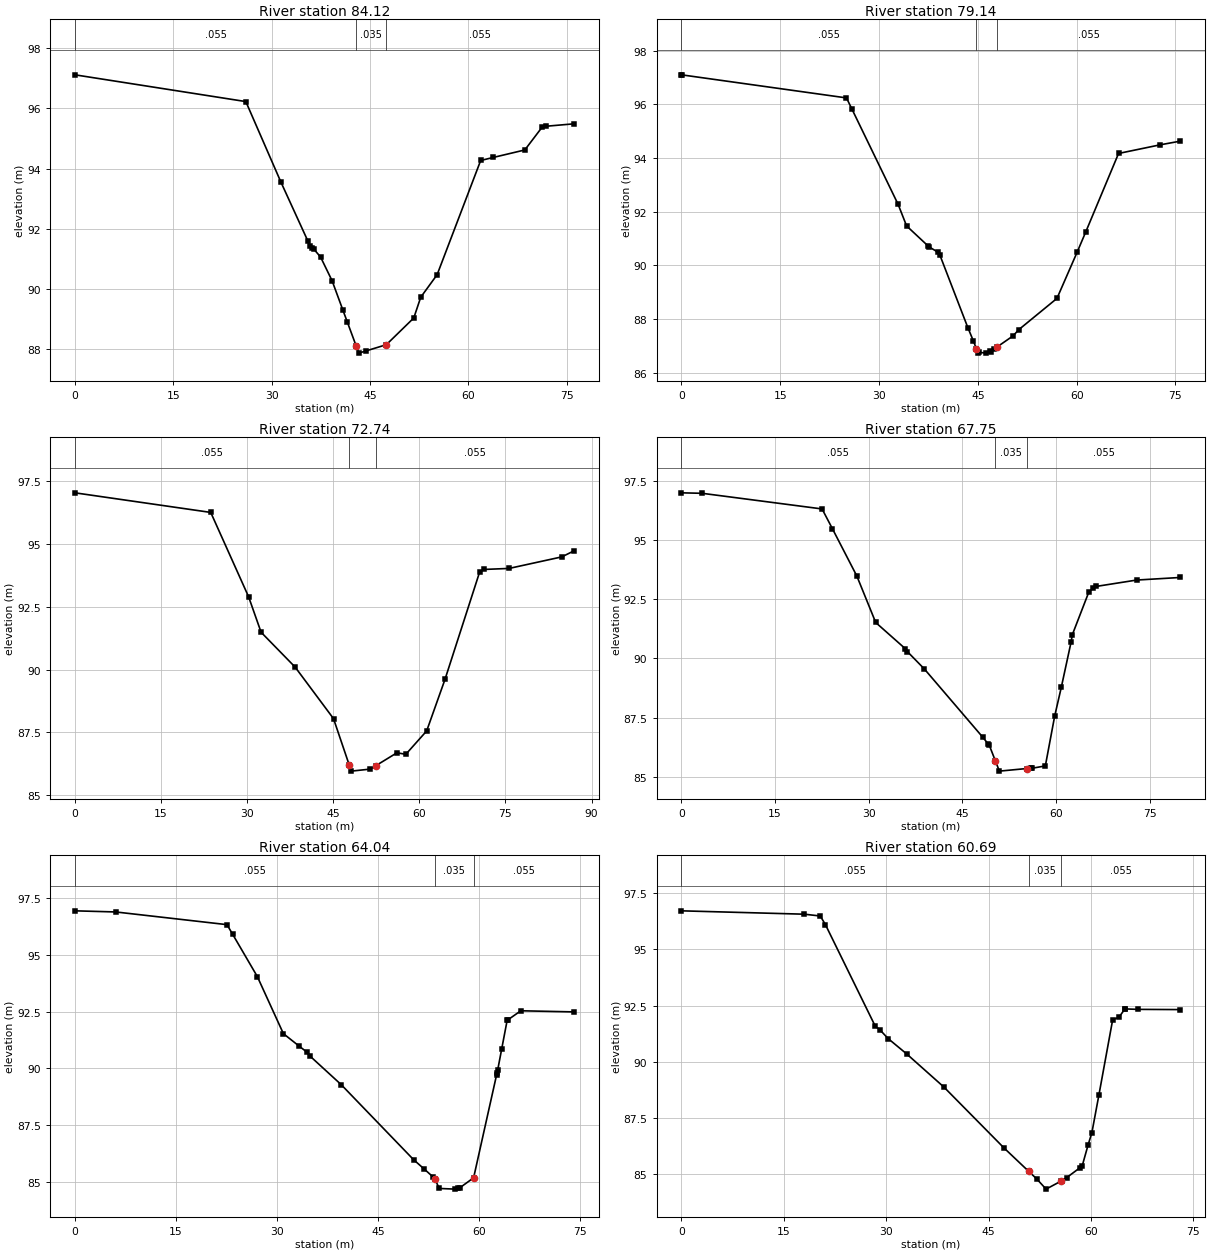
Type RM Length L Ch R = 1 ,84.12   ,3.03,4.98,8.8
XS GIS Cut Line= 6
344172.6889038095422796.34509277344187.4166870125422824.04870605
344193.3076782235422831.49407959344199.372070313 5422834.0914917
344213.0603027345422825.26068115344222.7633056645422817.64227295
#Sta/Elev= 24
       0   97.12   26.05   96.23   31.38   93.56   35.51   91.59   35.77   91.44
    36.2   91.36   36.38   91.33   37.44   91.06    39.2   90.27   40.87   89.28
   41.55   88.88   42.87  88.102   43.28   87.86   44.32   87.93   47.47   88.14
   51.66   89.03   52.72   89.72   55.22   90.47   61.86   94.27   63.76   94.37
   68.59   94.62    71.2   95.37   71.88   95.41   76.09   95.49
#Mann= 3 , 0 , 0
       0    .055       0   42.87    .035       0   47.47    .055       0
Bank Sta=42.87,47.47
XS Rating Curve= 0 ,0
Exp/Cntr=0.3,0.1

Type RM Length L Ch R = 1 ,79.14   ,5.7,6.39,8.69
XS GIS Cut Line= 6
344172.5156860355422797.38391113344184.6442871095422820.23950195
344189.4959106455422830.80151367344192.6146850595422836.86169434
 344198.505676275422838.07373047344222.416687012 5422829.4163208
#Sta/Elev= 28
       0    97.1     .01    97.1   25.05   96.24   25.87   95.83    32.9   92.27
   34.18   91.47    37.5   90.71   37.59   90.69   38.88    90.5   39.24   90.38
   43.48   87.68   44.31   87.19   44.77    86.9   45.02   86.74   45.24   86.76
   46.21   86.73   46.81    86.8   47.05   86.79   47.47   86.88   47.98   86.97
   50.33   87.37   51.24   87.61   57.01   88.77   60.07   90.49   61.37   91.24
   66.36   94.17   72.64   94.49   75.76   94.63
#Mann= 3 , 0 , 0
       0    .055       0   44.77    .035       0   47.98    .055       0
Bank Sta=44.77,47.98
XS Rating Curve= 0 ,0
Exp/Cntr=0.3,0.1

Type RM Length L Ch R = 1 ,72.74   ,2.71,4.99,10
XS GIS Cut Line= 6
344171.8225097665422799.11547852344184.1245117195422820.93212891
344188.6295166025422839.97851563344193.3076782235422843.78771973
344216.6989135745422842.22930908344227.2681274415422834.95709229
#Sta/Elev= 19
       0   97.04   23.65   96.26   30.25    92.9   32.42   91.49   38.36    90.1
   45.04   88.05   47.79  86.196   48.14   85.96   51.41   86.04   52.44   86.18
   56.09   86.69   57.64   86.63   61.27   87.56   64.46   89.61   70.49   93.88
   71.28   93.99   75.63   94.03   84.82   94.49   86.94   94.73
#Mann= 3 , 0 , 0
       0    .055       0   47.79    .035       0   52.44    .055       0
Bank Sta=47.79,52.44
XS Rating Curve= 0 ,0
Exp/Cntr=0.3,0.1

Type RM Length L Ch R = 1 ,67.75   ,2.94,3.71,5.31
XS GIS Cut Line= 5
344170.9561157235422800.32751465344182.3919067385422821.62469482
344188.1096801765422845.86547852344201.4512939455422856.25427246
344215.1395263675422858.85168457
#Sta/Elev= 27
       0   96.98    3.31   96.96   22.52    96.3   24.17   95.47   28.09   93.47
   31.11   91.51   35.87    90.4   36.19   90.28    38.9   89.55   48.29   86.66
   49.08    86.4   49.29   86.34   50.28   85.67   50.92   85.24   55.32   85.35
   55.94   85.37   56.12   85.36   58.28   85.46   59.78   87.57   60.83   88.77
   62.39   90.67   62.61      91   65.25    92.8   65.99   92.96   66.38   93.03
   72.89    93.3   79.92   93.41
#Mann= 3 , 0 , 0
       0    .055       0   50.28    .035       0   55.32    .055       0
Bank Sta=50.28,55.32
XS Rating Curve= 0 ,0
Exp/Cntr=0.3,0.1

Type RM Length L Ch R = 1 ,64.04   ,3.68,3.35,4.35
XS GIS Cut Line= 5
344169.7432861335422800.50048828344180.4859008795422821.27832031
344182.5651245125422830.97467041344185.8572998055422847.59692383
344200.5848999025422866.29711914
#Sta/Elev= 27
       0   96.95    6.05    96.9   22.56   96.34   23.39   95.92   27.06   94.05
   30.93   91.53   33.31   90.97    34.4   90.72   34.92   90.53   39.51   89.28
   50.25   85.97   51.74   85.58   53.17    85.2   53.39   85.13   54.06    84.7
   56.42   84.67   56.83    84.7   57.07   84.72   59.16   85.17   62.57   89.71
   62.64   89.81   62.73   89.92   63.32   90.84   64.14   92.12    64.2   92.13
   66.17   92.54   74.06   92.49
#Mann= 3 , 0 , 0
       0    .055       0   53.39    .035       0   59.16    .055       0
Bank Sta=53.39,59.16
XS Rating Curve= 0 ,0
Exp/Cntr=0.3,0.1

Type RM Length L Ch R = 1 ,60.69   ,4.56,3.94,4.31
XS GIS Cut Line= 5
344164.1987304695422804.13671875344179.4462890635422833.39868164
 344182.738281255422847.25067139344187.9362792975422857.12011719
344197.6392822275422868.20172119
#Sta/Elev= 27
       0   96.71   18.01   96.56   20.34   96.48   21.09    96.1    28.4   91.58
   29.05   91.43   30.29   91.03      33   90.35   38.48   88.87   47.23   86.18
   50.88   85.13   52.04    84.8   53.43   84.34   55.58   84.69   55.79   84.72
   56.44   84.85   58.39   85.29   58.71   85.36   59.59   86.31   60.14   86.85
   61.16   88.51   63.18   91.86   64.13   91.99   64.96   92.34   65.02   92.35
   66.87   92.33   73.12   92.32
#Mann= 3 , 0 , 0
       0    .055       0   50.88    .035       0   55.58    .055       0
Bank Sta=50.88,55.58
XS Rating Curve= 0 ,0
Exp/Cntr=0.3,0.1

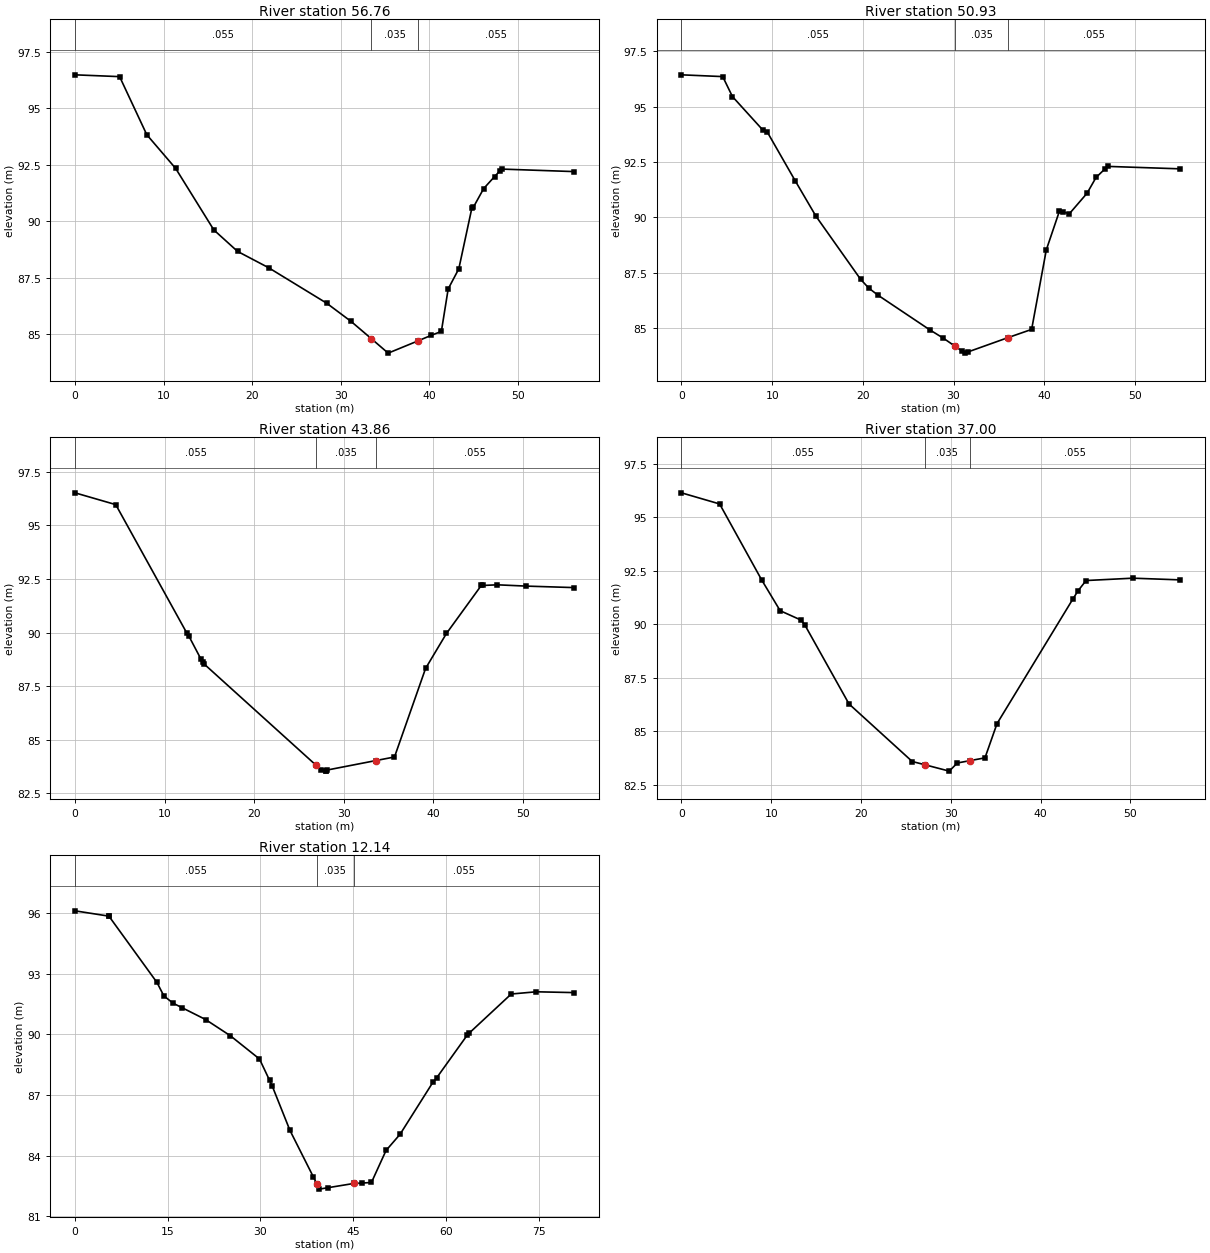
Type RM Length L Ch R = 1 ,56.76   ,7.72,5.83,4.41
XS GIS Cut Line= 4
344158.3076782235422827.16552734 344178.579895025422847.07751465
344186.7235107425422864.21929932344193.4810791025422870.10632324
#Sta/Elev= 23
       0   96.48    5.04    96.4    8.11   93.83   11.37   92.34   15.68   89.62
   18.36   88.67   21.86   87.95   28.42   86.38   31.19   85.57   33.47   84.81
   35.37   84.17   38.73   84.71   40.25   84.96   41.38   85.13   42.15   87.01
   43.35    87.9   44.82   90.58   44.99   90.62   46.16   91.45   47.39   91.98
   47.99   92.23   48.26   92.31   56.36    92.2
#Mann= 3 , 0 , 0
       0    .055       0   33.47    .035       0   38.73    .055       0
Bank Sta=33.47,38.73
XS Rating Curve= 0 ,0
Exp/Cntr=0.3,0.1

Type RM Length L Ch R = 1 ,50.93   ,7.48,7.07,7.18
XS GIS Cut Line= 3
344154.1492919925422830.97467041344182.045288086 5422862.4876709
344192.0949096685422870.62567139
#Sta/Elev= 27
       0   96.43    4.55   96.35    5.62   95.45    8.95   93.95    9.45   93.86
   12.53   91.66   14.82   90.06   19.75   87.21   20.66   86.81   21.68   86.49
   27.38   84.93   28.89   84.55   30.17  84.189   30.91   83.98   31.27   83.88
   31.63   83.94   36.01   84.58   38.61   84.95   40.23   88.54   41.68   90.29
   42.09   90.24   42.78   90.17   44.72   91.09   45.71    91.8    46.7   92.19
   47.04    92.3   55.02   92.19
#Mann= 3 , 0 , 0
       0    .055       0   30.17    .035       0   36.01    .055       0
Bank Sta=30.17,36.01
XS Rating Curve= 0 ,0
Exp/Cntr=0.3,0.1

Type RM Length L Ch R = 1 ,43.86   ,6.35,6.86,7.11
XS GIS Cut Line= 3
344148.4312744145422837.38128662344180.3126831055422869.93310547
344188.4562988285422875.99328613
#Sta/Elev= 21
       0   96.52    4.55   95.97   12.51   89.96   12.71   89.84   14.08   88.75
   14.25   88.65   14.38   88.55   26.94  83.804   27.48    83.6   27.99   83.54
   28.02   83.54   28.14   83.59   33.56   84.03   35.67    84.2   39.14   88.33
   41.47   89.96   45.36    92.2   45.56    92.2   47.15   92.23   50.35   92.17
   55.71    92.1
#Mann= 3 , 0 , 0
       0    .055       0   26.94    .035       0   33.56    .055       0
Bank Sta=26.94,33.56
XS Rating Curve= 0 ,0
Exp/Cntr=0.3,0.1

Type RM Length L Ch R = 1 ,37.00   ,27.23,24.86,22.79
XS GIS Cut Line= 3
344145.4793090825422841.12591553344173.7730712895422874.27587891
 344184.958923345422878.58673096
#Sta/Elev= 19
       0   96.14    4.25   95.62    8.93   92.07   10.99   90.63   13.32   90.19
   13.73   89.97   18.66   86.27    25.7   83.58   27.09   83.43   29.82   83.13
   30.72   83.51   32.12   83.62    33.8   83.75   35.14   85.35   43.58   91.17
   44.18   91.57   45.06   92.04   50.26   92.15   55.57   92.07
#Mann= 3 , 0 , 0
       0    .055       0   27.09    .035       0   32.12    .055       0
Bank Sta=27.09,32.12
XS Rating Curve= 0 ,0
Exp/Cntr=0.3,0.1

Type RM Length L Ch R = 1 ,12.14   ,4.7,12.15,6.96
XS GIS Cut Line= 6
344139.0648803715422843.84472656344136.9857177735422848.86608887
344142.5302734385422874.31890869344145.1292724615422880.89849854
344157.6044921885422887.30487061344184.6342773445422879.51330566
#Sta/Elev= 29
       0    96.1    5.43   95.84    5.48   95.84   13.26   92.56   14.37    91.9
   15.84   91.54   17.28   91.32   21.12   90.73   25.12   89.93   29.84   88.78
   31.48   87.72   31.88   87.46   34.77   85.25   38.56   82.95   39.11  82.606
   39.52   82.35    40.9   82.42   45.09   82.63   46.48   82.65   47.95   82.68
   50.31   84.26   52.58   85.06   57.87   87.62    58.5   87.85   63.47   89.97
   63.73   90.05   70.56   91.99   74.61    92.1   80.71   92.06
#Mann= 3 , 0 , 0
       0    .055       0   39.11    .035       0   45.09    .055       0
Bank Sta=39.11,45.09
XS Rating Curve= 0 ,0
Exp/Cntr=0.3,0.1

River Reach=BellsB          ,M002
Reach XY= 30
342253.7468872075421134.60931396342350.9110717775421129.54528809
342443.6716918955421244.12451172342442.2005004885421466.38751221
342499.714477539  5421578.284729342582.4801025395421661.34710693
342588.6450805665421717.04992676342637.0739135745421745.06988525
342593.8115234385421952.46270752342607.6630859385422009.07128906
342568.2431030275422041.64990234342629.994873047 5422104.3192749
 342599.371093755422241.19927979342679.5280761725422369.15911865
342764.2416992195422389.19268799342898.6043090825422369.78991699
342973.2835083015422459.28948975343043.7155151375422683.67950439
343121.2028808595422725.05749512343206.7385253915422666.71209717
343299.5507202155422773.61712646343475.9014892585422722.18811035
343520.2786865235422782.17248535343600.3688964845422818.95428467
343699.2672729495422816.61627197 343718.119079595422849.35510254
343842.1005249025422833.88592529343938.5328979495422872.97729492
343987.3618774415422852.26452637344144.2833251955422894.11730957

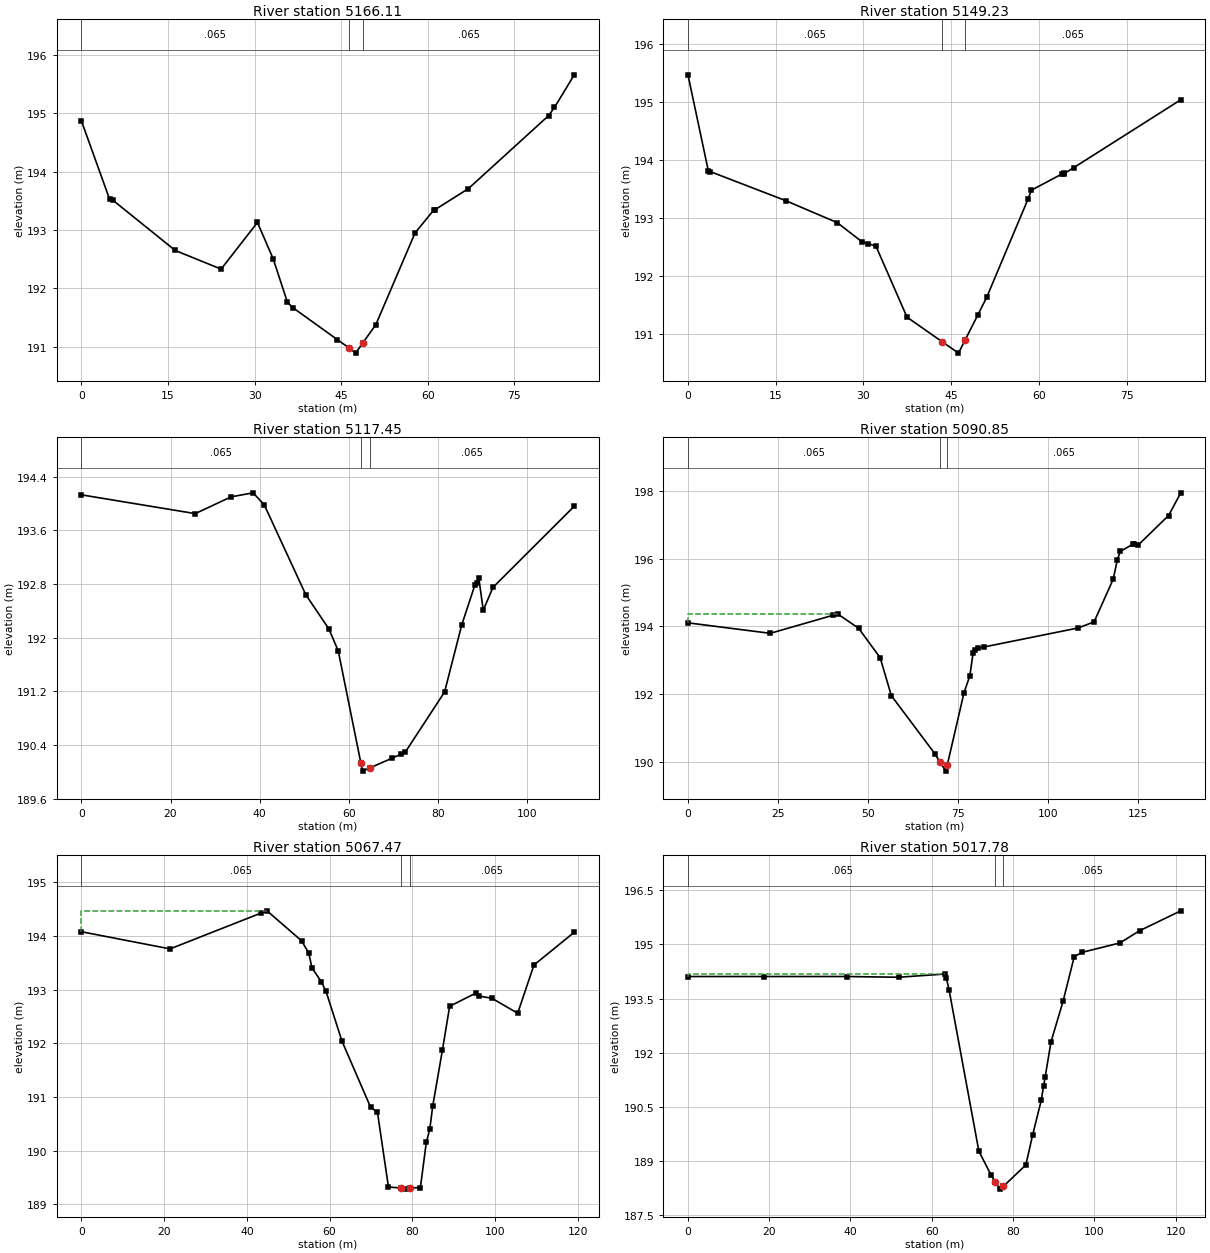
Type RM Length L Ch R = 1 ,5166.11 ,15.85,16.88,18.06
XS GIS Cut Line= 2
342277.9199218755421174.32928467342246.3927001955421094.99212646
#Sta/Elev= 21
       0  194.87    4.87  193.53    5.46  193.51   16.24  192.65    24.2  192.33
   30.49  193.13   33.24   192.5   35.69  191.76   36.61  191.67   44.35  191.12
   46.35  190.98   47.49  190.89   48.76 191.067   51.01  191.38   57.79  192.95
   61.01  193.34   61.28  193.35   67.04  193.71   80.92  194.96   81.94   195.1
   85.37  195.66
#Mann= 3 , 0 , 0
       0    .065       0   46.35     .04       0   48.76    .065       0
Bank Sta=46.35,48.76
XS Rating Curve= 0 ,0
Exp/Cntr=0.3,0.1

Type RM Length L Ch R = 1 ,5149.23 ,31.28,31.78,26.26
XS GIS Cut Line= 3
342284.6198730475421175.58990479342286.6940917975421159.00872803
 342266.990295415421094.41052246
#Sta/Elev= 21
       0  195.47    3.49  193.81    3.84   193.8   16.71   193.3   25.53  192.92
   29.75  192.59   30.83  192.56   32.16  192.51   37.45  191.29   43.45 190.867
   46.25  190.67   47.35  190.89   49.51  191.32   51.06  191.63   58.15  193.33
   58.71  193.48   63.94  193.76   64.25  193.76   64.35  193.77   65.97  193.87
   84.25  195.04
#Mann= 3 , 0 , 0
       0    .065       0   43.45     .04       0   47.35    .065       0
Bank Sta=43.45,47.35
XS Rating Curve= 0 ,0
Exp/Cntr=0.3,0.1

Type RM Length L Ch R = 1 ,5117.45 ,19.84,26.6,30.57
XS GIS Cut Line= 3
342310.9426879885421195.21392822342324.6160888675421164.53149414
342286.500915527  5421097.578125
#Sta/Elev= 22
       0  194.13   25.55  193.85   33.59   194.1   38.54  194.16   41.05  193.98
   50.37  192.64   55.56  192.13   57.66   191.8   62.74 190.128    63.1  190.01
   64.68 190.056   69.63   190.2   71.63  190.26   72.67  190.29   81.52  191.19
   85.37  192.19   88.35  192.79    88.8  192.82    89.2  192.89   90.21  192.41
   92.38  192.75  110.63  193.96
#Mann= 3 , 0 , 0
       0    .065       0   62.74     .04       0   64.68    .065       0
Bank Sta=62.74,64.68
XS Rating Curve= 0 ,0
Exp/Cntr=0.3,0.1

Type RM Length L Ch R = 1 ,5090.85 ,11.72,23.38,30.25
XS GIS Cut Line= 5
342312.2744750985421195.62567139342333.3610839845421161.42669678
342330.595703125 5421119.2824707 342333.706909185421078.17468262
342337.5092773445421065.39331055
#Sta/Elev= 27
       0   194.1   22.87  193.79   40.18  194.32   41.65  194.36   47.43  193.94
   53.42  193.07   56.52  191.95   68.58  190.24   69.99     190   71.67  189.72
   72.07   189.9   76.71  192.03   78.35  192.54   79.25  193.21   79.73  193.31
   80.68  193.35   82.41  193.39  108.53  193.95  112.89  194.13  118.19  195.39
  119.36  195.97  120.17  196.21  123.64  196.42  123.87  196.44  125.17   196.4
  133.58  197.27  136.97  197.94
#Mann= 3 , 0 , 0
       0    .065       0   69.99     .04       0   72.07    .065       0
#XS Ineff= 2 , 0
       0   41.65  194.36               0
Permanent Ineff=
       F       F
Bank Sta=69.99,72.07
XS Rating Curve= 0 ,0
Exp/Cntr=0.3,0.1

Type RM Length L Ch R = 1 ,5067.47 ,48.56,49.69,45.53
XS GIS Cut Line= 4
342313.2647094735421195.98748779342339.321716309 5421161.1796875
342343.9644775395421135.16009521342390.2396850595421118.28967285
#Sta/Elev= 28
       0  194.08   21.43  193.76   43.48  194.43   44.88  194.47   53.25  193.91
   54.99  193.68   55.73  193.41   57.98  193.15   59.14  192.97      63  192.04
   69.91  190.81   71.59  190.71   74.24  189.32   77.36   189.3   78.38  189.28
   79.36   189.3   81.97  189.31   83.39  190.15   84.24   190.4   84.95  190.83
   87.31  191.88   89.04  192.69   95.49  192.94   96.14  192.88   99.25  192.84
  105.49  192.56  109.43  193.46  119.17  194.07
#Mann= 3 , 0 , 0
       0    .065       0   77.36     .04       0   79.36    .065       0
#XS Ineff= 2 , 0
       0   44.88  194.47               0
Permanent Ineff=
       F       F
Bank Sta=77.36,79.36
XS Rating Curve= 0 ,0
Exp/Cntr=0.3,0.1

Type RM Length L Ch R = 1 ,5017.78 ,49.08,50.21,50
XS GIS Cut Line= 3
 342317.392517095421198.30810547342365.3787231455421178.71252441
342418.3422851565421133.77050781
#Sta/Elev= 24
       0  194.11   18.61  194.11   39.21  194.11   51.83  194.09   63.38  194.18
   63.57  194.08   64.28  193.73    71.6  189.27   74.56  188.62   75.65  188.42
   76.84  188.22   77.65   188.3   83.16  188.89   84.81  189.71   86.95  190.68
   87.54  191.09   87.92  191.33   89.35   192.3   92.31  193.42   95.07  194.66
   97.02  194.78   106.3  195.04  111.18  195.38  121.29  195.93
#Mann= 3 , 0 , 0
       0    .065       0   75.65     .04       0   77.65    .065       0
#XS Ineff= 2 , 0
       0   63.38  194.18               0
Permanent Ineff=
       F       F
Bank Sta=75.65,77.65
XS Rating Curve= 0 ,0
Exp/Cntr=0.3,0.1