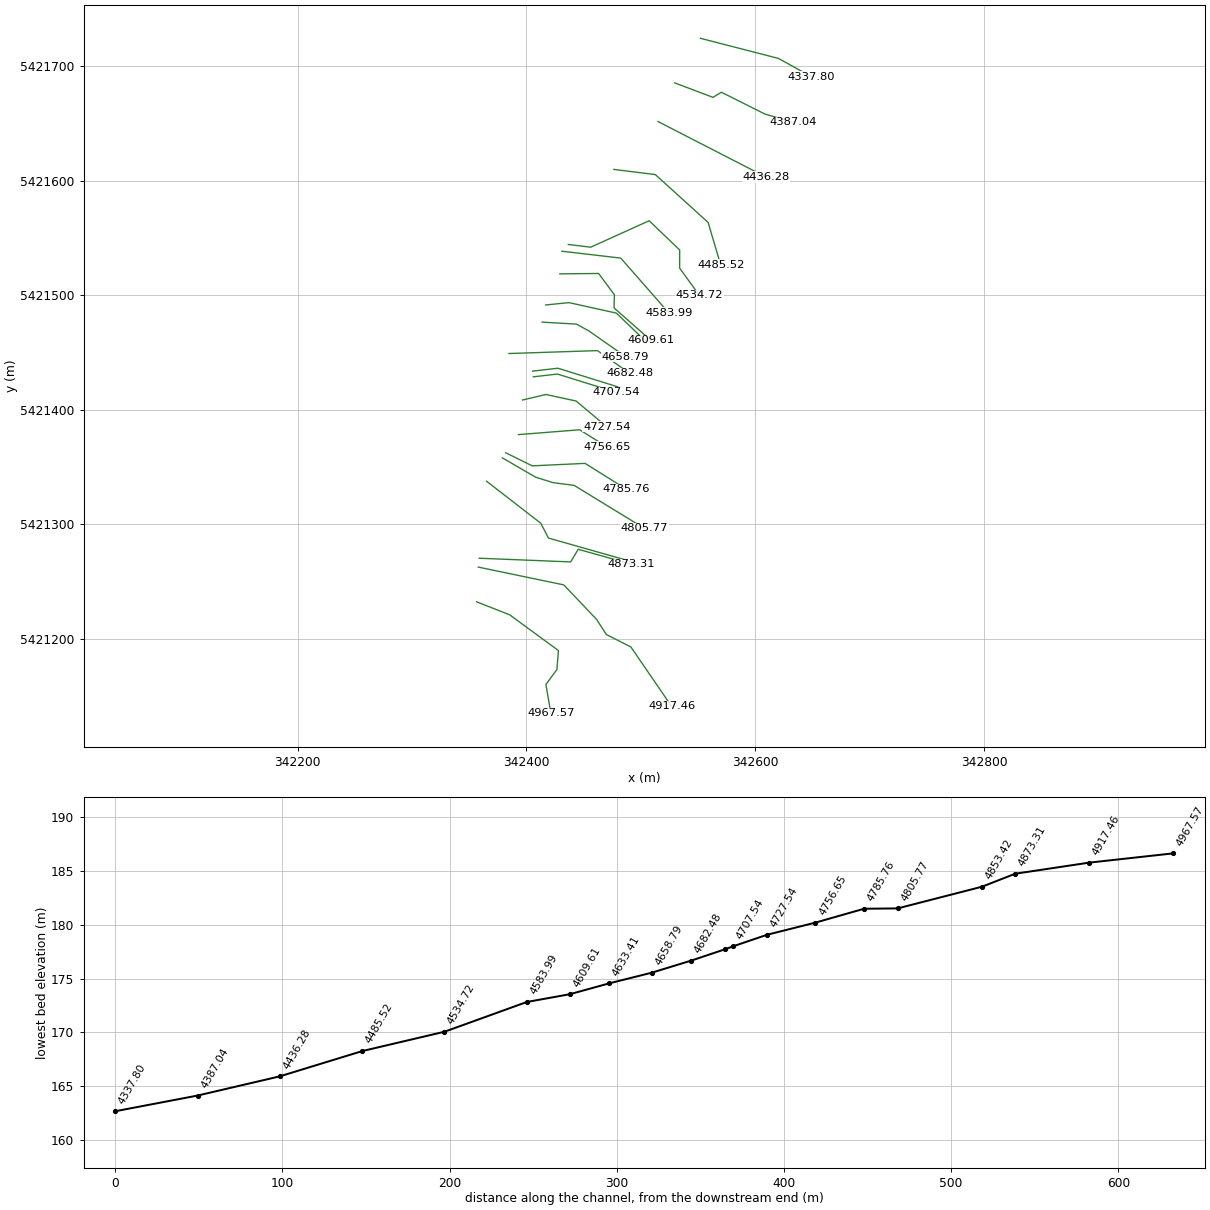
HEC-RAS study Corner_Brook2.prj: Corner_Brook2

--- Corner_Brook2.g01 (geometry) --- (continued)

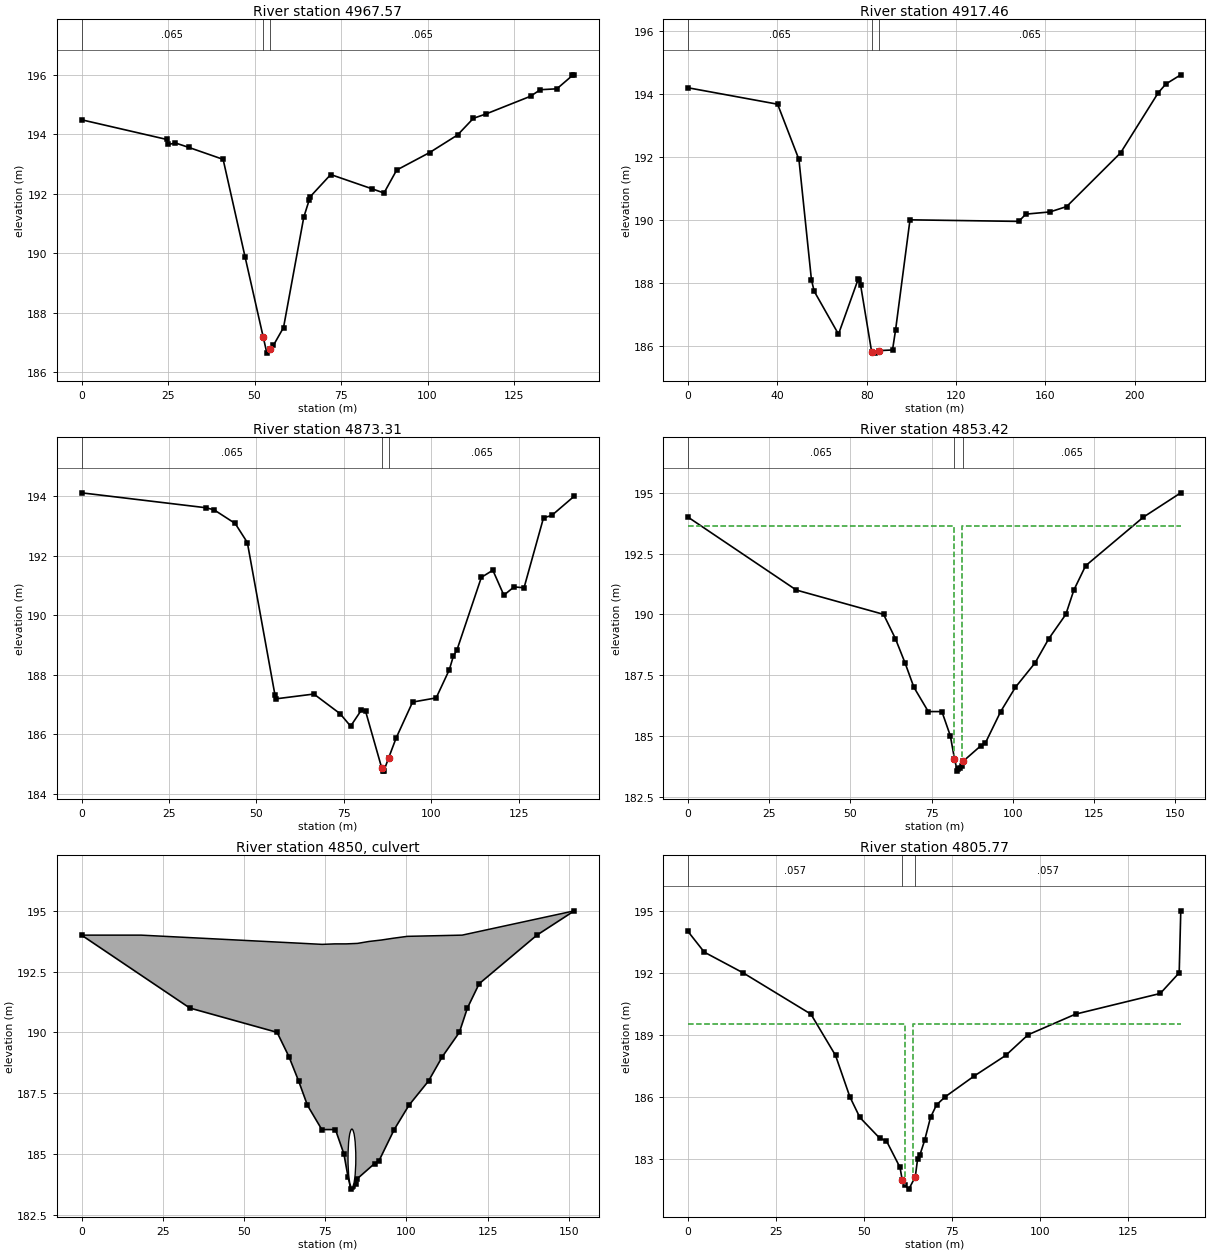
Type RM Length L Ch R = 1 ,4967.57 ,45.92,50.1,48.87
XS GIS Cut Line= 6
342356.3491210945421232.34228516342385.2438964845421220.99768066
342427.9514770515421189.73413086342426.5952758795421173.13287354
 342416.976684575421160.14831543342421.3626708985421134.88031006
#Sta/Elev= 28
       0  194.49   24.59  193.83    25.1  193.66   27.15  193.71   31.04  193.56
   40.92  193.16   47.29  189.87   52.49   187.2   53.57  186.65   54.49  186.78
   55.45  186.91   58.38  187.51   64.24  191.22   65.84  191.81   66.05   191.9
   72.02  192.65   83.97  192.17   87.42  192.03   91.08   192.8  100.63  193.39
  108.69  193.98  113.27  194.54  116.79  194.68  129.77  195.28   132.6   195.5
  137.39  195.53   141.9  195.98  142.43     196
#Mann= 3 , 0 , 0
       0    .065       0   52.49     .04       0   54.49    .065       0
Bank Sta=52.49,54.49
XS Rating Curve= 0 ,0
Exp/Cntr=0.3,0.1

Type RM Length L Ch R = 1 ,4917.46 ,19.17,44.16,54.69
XS GIS Cut Line= 6
342357.8818969735421262.62231445 342432.634704595421247.08508301
342461.317871094 5421216.9163208342469.8649291995421203.72247314
342491.2780761725421192.89349365342526.8798828135421141.00531006
#Sta/Elev= 23
       0  194.19   40.11  193.67   49.66  191.92   55.26  188.11   56.48  187.75
   67.37  186.39   76.23  188.14   76.67  188.12   77.24  187.96   82.26  185.81
   83.82  185.79   85.67  185.87   91.56  185.89   92.94  186.53   99.38  190.01
  148.09  189.96  151.23  190.19  162.06  190.26  169.52  190.43  193.67  192.13
  210.51  194.03  213.95  194.31  220.62   194.6
#Mann= 3 , 0 , 0
       0    .065       0   82.26     .04       0   85.67    .065       0
Bank Sta=82.26,85.67
XS Rating Curve= 0 ,0
Exp/Cntr=0.3,0.1

Type RM Length L Ch R = 1 ,4873.31 ,21.46,19.89,10.45
XS GIS Cut Line= 4
342358.6434936525421270.36907959342438.6124877935421267.15551758
342445.2736816415421278.15710449342491.5441284185421265.21850586
#Sta/Elev= 30
       0  194.11    35.5  193.61   37.89  193.54   43.94  193.08   47.42  192.44
   55.33  187.31   55.68  187.19   66.45  187.35   73.94  186.69   76.96  186.27
   80.03  186.81   81.22  186.78   85.82  184.88   86.08  184.76   86.44  184.76
   87.82   185.2   89.97  185.87   94.68  187.08  101.43  187.22   105.2  188.17
  106.36  188.63  107.34  188.82  114.35  191.27  117.64  191.51  120.79  190.67
   123.7  190.95  126.56  190.92  132.13  193.27  134.49  193.35  140.94     194
#Mann= 3 , 0 , 0
       0    .065       0   85.82     .04       0   87.82    .065       0
Bank Sta=85.82,87.82
XS Rating Curve= 0 ,0
Exp/Cntr=0.3,0.1

Type RM Length L Ch R = 1 ,4853.42 ,50.5,50.5,50.5
XS GIS Cut Line= 4
342365.0905151375421337.63391113342412.5452880865421300.91088867
342419.1926879885421287.99310303342493.4204711915421266.96832275
#Sta/Elev= 26
       0     194   33.33     191   60.19     190   63.84     189   66.81     188
   69.53     187   73.96     186   78.15     186   80.75     185   82.02  184.06
   82.89  183.55   83.22  183.62   83.62  183.67   84.34  183.76   84.64  183.95
   90.18   184.6   91.54  184.71   96.24     186  100.78     187  106.81     188
  111.06     189   116.3     190  118.77     191  122.39     192  140.17     194
  151.68     195
#Mann= 3 , 0 , 0
       0    .065       0   82.02     .04       0   84.64    .065       0
#XS Ineff= 2 , 0
       0   82.02  193.62   84.42       0  193.62
Permanent Ineff=
       F       F
Bank Sta=82.02,84.64
XS Rating Curve= 0 ,0
Exp/Cntr=0.5,0.3

Type RM Length L Ch R = 2 ,4850    ,,,
BEGIN DESCRIPTION:
Ring Road (Structure #2129)
END DESCRIPTION:
Bridge Culvert--1,0,-1,-1, 0
Deck Dist Width WeirC Skew NumUp NumDn MinLoCord MaxHiCord MaxSubmerge Is_Ogee
17.25,12.2,1.67,0, 13, 13, 193.62, , 0.98, 0, 0.64,0.63,,
       0   18.35   68.32   74.04   77.93   81.43   84.94   88.48   92.35   95.81
  100.27  117.15  151.68
     194     194  193.66  193.62  193.64  193.64  193.66  193.74   193.8  193.87
  193.95     194     195
                                                                                
                        
       0     6.5   44.14   47.78   51.11    54.7   58.32   61.86   65.29   68.91
   73.04   98.35  139.95
     194     194  193.02  192.99  192.96  192.98  192.97  193.01  193.08  193.14
  193.06     194     195
                                                                                
                        
BR Coef=-1 , 0 , 0 ,, 0 ,,,0.8,-1,,0,
WSPro=,,,, 1 ,,,, 0 ,,,, 0 ,,,,-1 ,-1 ,-1 , 0 , 0 , 0 , 0 , 0
Culvert=1,2.4,,45.5,0.03,0.9,1,1,1,183.62,83.22,182.06,62.72,Culvert #1  , 0 ,2.3
Culvert Bottom n=0.03
BC Design=,, 0 ,, 0 ,,,,,,
BC Use User HTab Curves=0
BC User HTab FreeFlow(D)= 0

Type RM Length L Ch R = 1 ,4805.77 ,17.89,20,21.25
XS GIS Cut Line= 6
      342378.992     5421357.995      342408.049      5421341.11
      342423.395      5421336.35      342441.668     5421333.993
      342441.668     5421333.993      342503.085     5421296.461
#Sta/Elev= 27
       0     194    4.62     193   15.63     192    34.9     190    41.9     188
   45.96     186    48.8     185   54.42     184   56.37  183.86   60.21  182.58
   60.84  181.97   61.59  181.72   62.72  181.53   64.55  182.13   65.21     183
   65.83  183.17    67.2  183.89   68.87     185   70.59  185.61   73.05     186
   81.24     187   90.22     188   96.57     189  110.06     190  134.12     191
   139.5     192  139.95     195
#Mann= 3 , 0 , 0
       0    .057       0   60.84     .04       0   64.55    .057       0
#XS Ineff= 2 , 0
       0   61.52   189.5   63.92       0   189.5
Permanent Ineff=
       F       F
Bank Sta=60.84,64.55
XS Rating Curve= 0 ,0
Exp/Cntr=0.5,0.3

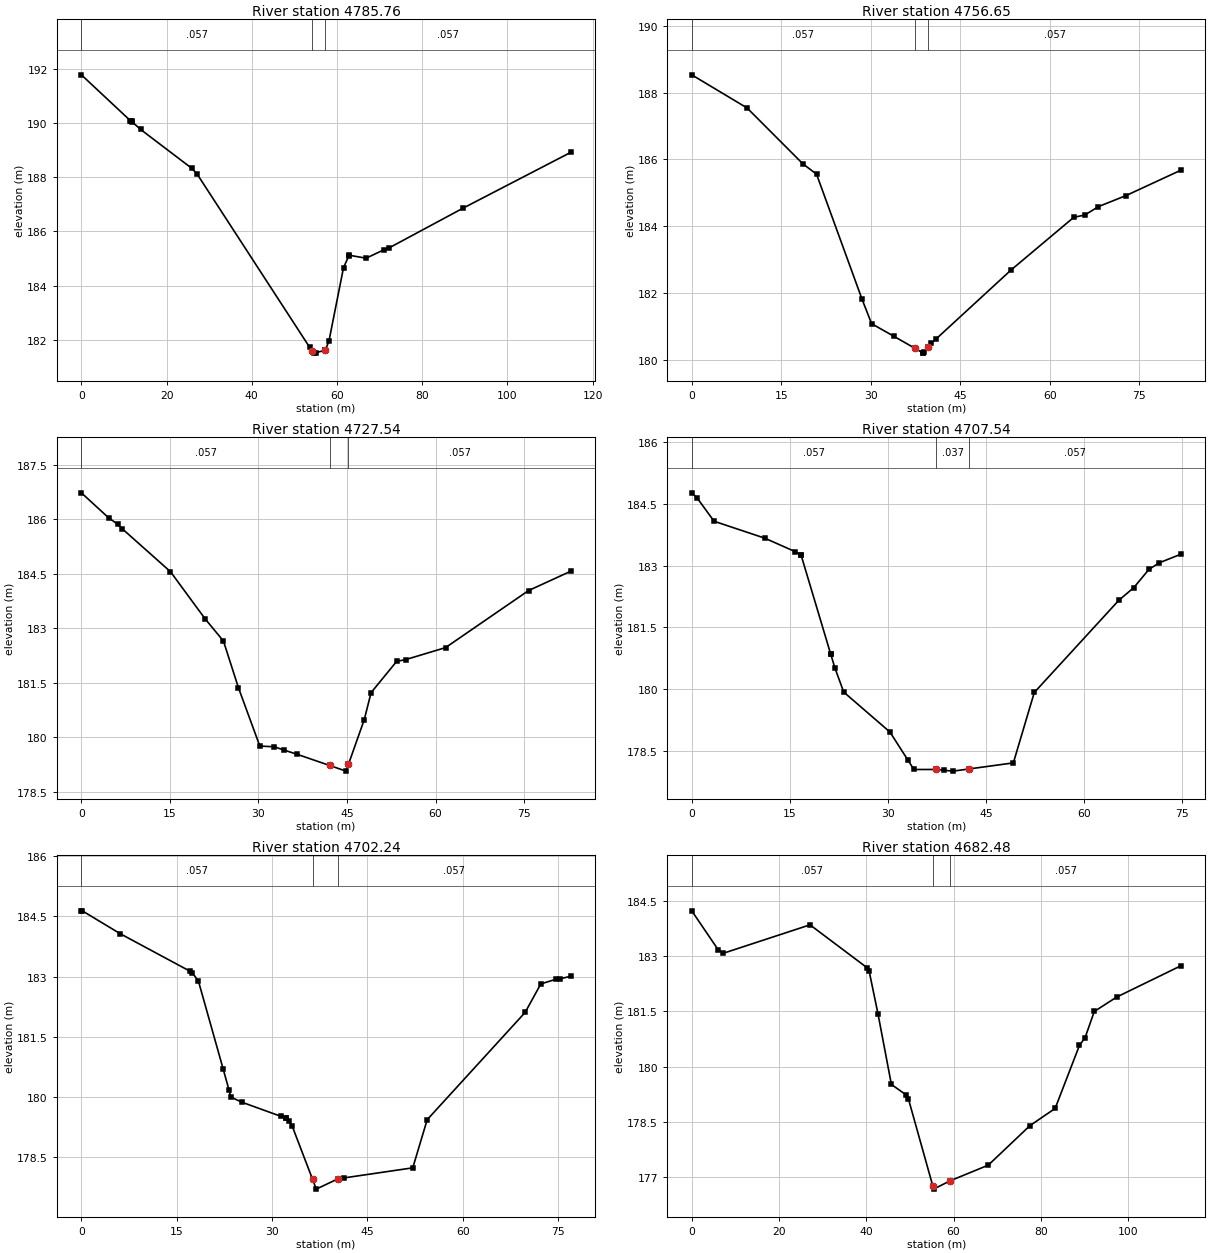
Type RM Length L Ch R = 1 ,4785.76 ,29.07,29.11,29.57
XS GIS Cut Line= 4
342381.8477172855421362.48071289342405.0465087895421351.04650879
 342451.236511235421353.20410156342487.4505004885421330.52331543
#Sta/Elev= 23
       0  191.79   11.47   190.1   11.65  190.08   11.78  190.07   11.92  190.05
   13.91  189.77   25.86  188.34   27.17  188.12    53.6  181.71    54.2 181.581
   54.58   181.5    55.1  181.52    57.1   181.6   57.25   181.6   58.13  181.96
   61.53  184.66   62.79   185.1   62.85  185.12   66.84  185.01   70.98  185.32
    72.1  185.38   89.47  186.85  114.83  188.92
#Mann= 3 , 0 , 0
       0    .057       0    54.2     .04       0    57.1    .057       0
Bank Sta=54.2,57.1
XS Rating Curve= 0 ,0
Exp/Cntr=0.3,0.1

Type RM Length L Ch R = 1 ,4756.65 ,30.95,29.11,26.42
XS GIS Cut Line= 3
342393.0432739265421378.32452393342446.4367065435421382.54150391
342470.5885009775421367.50811768
#Sta/Elev= 20
       0  188.53    9.27  187.54   18.62  185.87   20.92  185.56   28.55  181.82
   30.15  181.09   33.92  180.71   37.43 180.352   38.72  180.22   38.83  180.21
      39  180.25   39.68   180.4   40.13   180.5      41  180.64   53.56   182.7
   64.04  184.27   65.91  184.34   68.17  184.59    72.8  184.92   82.01  185.68
#Mann= 3 , 0 , 0
       0    .057       0   37.43     .04       0   39.68    .057       0
Bank Sta=37.43,39.68
XS Rating Curve= 0 ,0
Exp/Cntr=0.3,0.1

Type RM Length L Ch R = 1 ,4727.54 ,19.26,20,19.72
XS GIS Cut Line= 4
342396.6063232425421408.54730225342417.0162963875421413.36407471
342443.3679199225421407.66790771342470.1505126955421385.22271729
#Sta/Elev= 22
       0  186.73    4.63  186.04    6.12  185.87    6.93  185.74   15.09  184.56
   20.97  183.26   24.07  182.65    26.6  181.37   30.23  179.76   32.67  179.74
   34.33  179.65   36.61  179.53   42.07 179.225   44.84  179.07   45.24 179.254
   47.93  180.49   49.08  181.23   53.41  182.09   54.95  182.14    61.7  182.47
   75.76  184.04   82.88  184.57
#Mann= 3 , 0 , 0
       0    .057       0   42.07    .037       0   45.24    .057       0
Bank Sta=42.07,45.24
XS Rating Curve= 0 ,0
Exp/Cntr=0.3,0.1

Type RM Length L Ch R = 1 ,4707.54 ,5.01,5.31,4.99
XS GIS Cut Line= 3
342405.9539184575421428.78527832342427.0795288095421431.20550537
342478.2404785165421415.30487061
#Sta/Elev= 25
       0  184.77      .8  184.65    3.41  184.08   11.15  183.67   15.84  183.34
   16.68  183.26   16.74  183.25   21.26  180.85   21.27  180.85   21.89  180.52
   23.25  179.93   30.32  178.96   33.06  178.28   33.98  178.05   37.37  178.05
    38.6  178.03      40  178.01   42.46 178.064    49.2  178.21    52.4  179.92
   65.34  182.16   67.64  182.47   69.94  182.91   71.52  183.07   74.84  183.28
#Mann= 3 , 0 , 0
       0    .057       0   37.37    .037       0   42.46    .057       0
Bank Sta=37.37,42.46
XS Rating Curve= 0 ,0
Exp/Cntr=0.3,0.1

Type RM Length L Ch R = 1 ,4702.24 ,16.74,19.76,23.42
XS GIS Cut Line= 3
342405.385681152 5421433.7454834342427.5565185555421436.28552246
342479.7224731455421420.07269287
#Sta/Elev= 26
       0  184.64     .14  184.64    6.11  184.07   17.04  183.14   17.44   183.1
   18.41  182.89   22.32  180.69    23.2  180.19   23.51     180   25.32  179.87
   31.43  179.52   32.12  179.47   32.25  179.47   32.66  179.41   33.13  179.29
   36.37  177.95   36.94  177.71   40.39  177.97   41.34  177.99   52.12  178.24
   54.39  179.44   69.79  182.11   72.26  182.82   74.72  182.94   75.35  182.95
   76.94  183.01
#Mann= 3 , 0 , 0
       0    .057       0   36.37    .037       0   40.39    .057       0
Bank Sta=36.37,40.39
XS Rating Curve= 0 ,0
Exp/Cntr=0.3,0.1

Type RM Length L Ch R = 1 ,4682.48 ,24.78,23.69,17.54
XS GIS Cut Line= 3
342384.6652832035421449.13708496342462.1015014655421451.67608643
342490.3955078135421431.71368408
#Sta/Elev= 21
       0  184.23    6.08  183.17    7.27  183.08    27.1  183.85   40.25  182.68
   40.66  182.59   42.69  181.43   45.75  179.52   49.09  179.24   49.65  179.13
   55.24 176.766   55.42  176.68   59.29  176.91   67.95  177.33   77.48   178.4
   83.28  178.87   88.85  180.58   90.14  180.79   92.25   181.5   97.37  181.89
  112.11  182.74
#Mann= 3 , 0 , 0
       0    .057       0   55.24    .037       0   59.29    .057       0
Bank Sta=55.24,59.29
XS Rating Curve= 0 ,0
Exp/Cntr=0.3,0.1

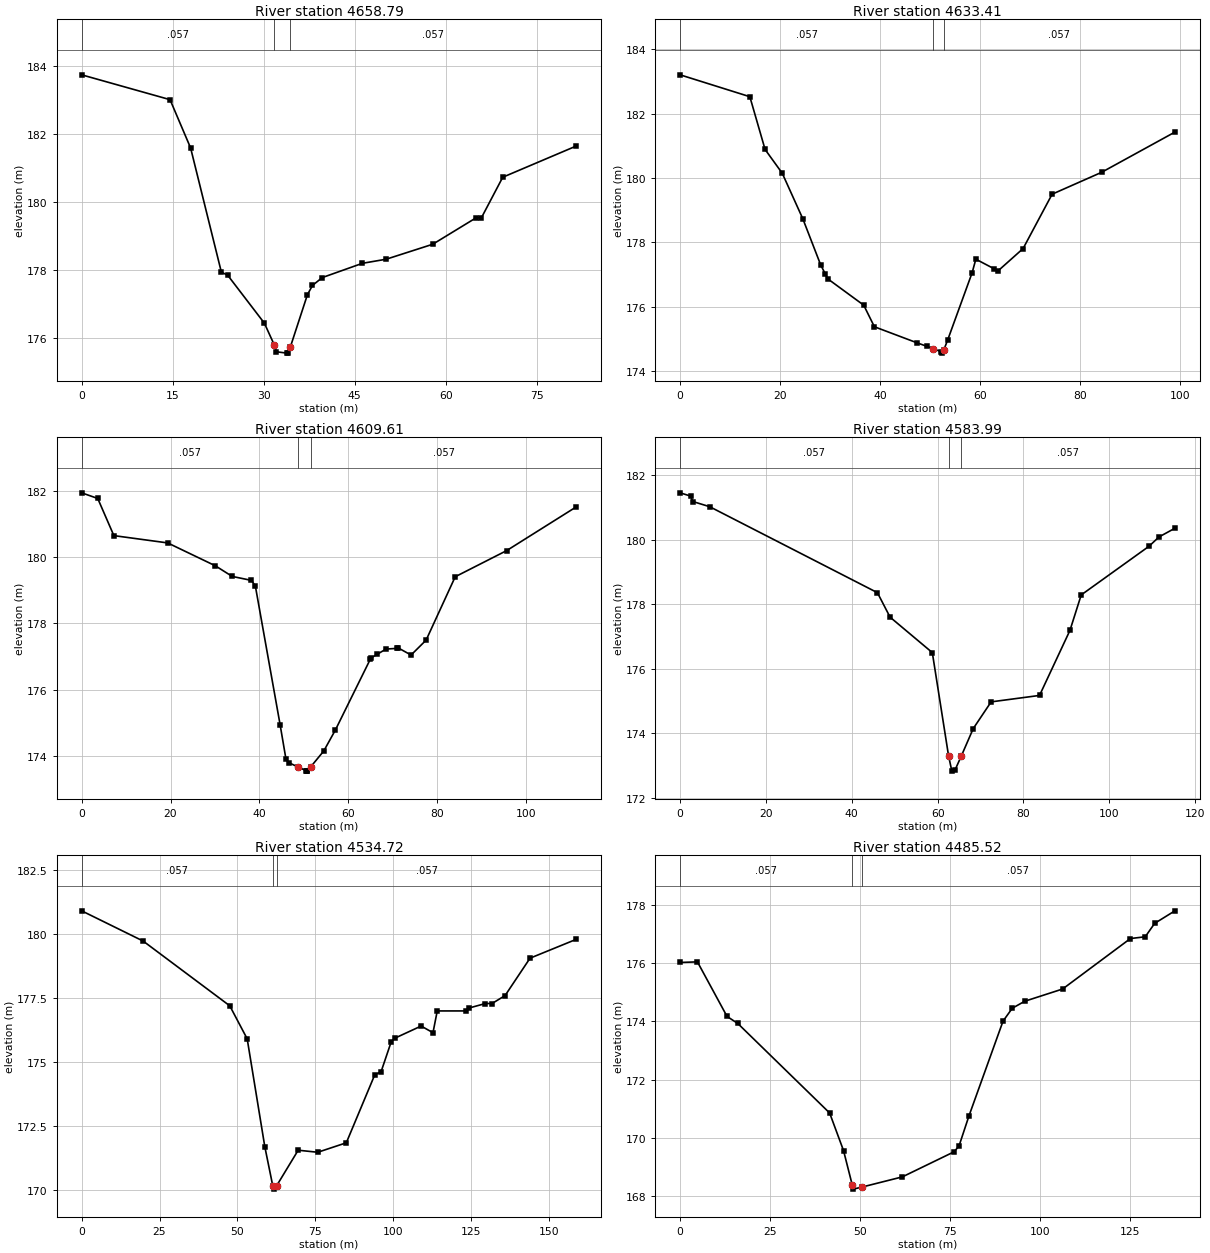
Type RM Length L Ch R = 1 ,4658.79 ,20.47,25.37,24.27
XS GIS Cut Line= 4
342413.6375122075421476.55328369342443.7119140635421474.82592773
 342454.427917485421468.95349121342486.5764770515421446.49951172
#Sta/Elev= 21
       0  183.73   14.57     183   17.96  181.58   23.03  177.93   24.07  177.84
   30.12  176.43   31.78  175.78   32.09  175.59   33.83  175.55   34.06  175.55
    34.4  175.73   37.22  177.27   38.05  177.54   39.65  177.77   46.28  178.19
   50.19  178.31   57.87  178.75   65.04  179.53    65.9  179.53   69.41  180.72
   81.56  181.64
#Mann= 3 , 0 , 0
       0    .057       0   31.78    .037       0    34.4    .057       0
Bank Sta=31.78,34.4
XS Rating Curve= 0 ,0
Exp/Cntr=0.3,0.1

Type RM Length L Ch R = 1 ,4633.41 ,27.81,23.8,18.32
XS GIS Cut Line= 4
342416.7960815435421491.53570557342437.1434936525421493.58789063
342478.5769042975421484.43591309342504.669311523 5421459.3939209
#Sta/Elev= 25
       0  183.21   13.96  182.53   17.01  180.89   20.45  180.15   24.58  178.73
   28.12  177.31   29.03  177.03   29.55  176.87   36.76  176.05   38.89  175.38
   47.43  174.88   49.43  174.77   50.68 174.697   52.17  174.61   52.47  174.56
   52.79  174.66   53.59  174.98   58.46  177.06    59.2  177.48   62.88  177.18
   63.67  177.12   68.66  177.81   74.47   179.5   84.38  180.18   99.05  181.43
#Mann= 3 , 0 , 0
       0    .057       0   50.68    .037       0   52.79    .057       0
Bank Sta=50.68,52.79
XS Rating Curve= 0 ,0
Exp/Cntr=0.3,0.1

Type RM Length L Ch R = 1 ,4609.61 ,24.92,25.62,25.97
XS GIS Cut Line= 5
342429.1931152345421518.69750977342463.0698852545421519.04290771
342476.8972778325421500.38891602342476.5516967775421488.98931885
342508.7000732425421460.66271973
#Sta/Elev= 29
       0  181.93    3.62  181.76    7.25  180.64   19.36  180.42   30.09  179.73
   33.88  179.41   38.21  179.29   39.09  179.12   44.66  174.94   45.98   173.9
   46.55   173.8   48.75  173.66   50.58  173.55   50.77  173.54   50.82  173.55
   51.53 173.666    54.5  174.15    57.1  174.78   64.98  176.92   65.12  176.95
   66.47  177.06    68.5  177.22   70.92  177.24    71.3  177.25   74.13  177.04
   77.52  177.49   84.07   179.4   95.67  180.19  111.35  181.51
#Mann= 3 , 0 , 0
       0    .057       0   48.75    .037       0   51.53    .057       0
Bank Sta=48.75,51.53
XS Rating Curve= 0 ,0
Exp/Cntr=0.3,0.1

Type RM Length L Ch R = 1 ,4583.99 ,44.18,49.27,61.24
XS GIS Cut Line= 3
342431.0048828135421538.47949219342482.4049072275421532.46948242
342524.3275146485421484.73327637
#Sta/Elev= 19
       0  181.46    2.43  181.36    2.96  181.19    6.88  181.03   45.97  178.36
   48.92   177.6   58.76   176.5   62.54   173.3   63.31  172.82      64  172.84
   65.52  173.29   68.29  174.14   72.46  174.97   83.74  175.17   90.83  177.19
   93.45  178.29  109.24   179.8  111.57  180.09  115.28  180.36
#Mann= 3 , 0 , 0
       0    .057       0   62.54    .037       0   65.52    .057       0
Bank Sta=62.54,65.52
XS Rating Curve= 0 ,0
Exp/Cntr=0.3,0.1

Type RM Length L Ch R = 1 ,4534.72 ,52.34,49.2,34.25
XS GIS Cut Line= 6
342436.604125977 5421544.3560791  342456.17968755421542.00231934
342507.2526855475421565.09869385342533.8956909185421539.60070801
342533.8956909185421523.66491699342551.0834960945421500.07147217
#Sta/Elev= 25
       0  180.92   19.72  179.74   47.53  177.21   53.12  175.92   58.77  171.71
   61.31  170.19   61.87  170.05   62.56  170.18   69.48  171.57   75.77  171.49
   84.93  171.86   94.04  174.51    96.1  174.64   99.35  175.81  100.58  175.95
  108.94  176.42  112.74  176.16  114.11  177.01  123.21  177.01  124.19  177.12
  129.59   177.3   131.7   177.3  135.88  177.61  143.88  179.07  158.78  179.81
#Mann= 3 , 0 , 0
       0    .057       0   61.31    .037       0   62.56    .057       0
Bank Sta=61.31,62.56
XS Rating Curve= 0 ,0
Exp/Cntr=0.3,0.1

Type RM Length L Ch R = 1 ,4485.52 ,46.5,49.24,52.08
XS GIS Cut Line= 4
342476.4520874025421609.90167236342512.644287109 5421605.4152832
342558.8079223635421563.58587646 342569.720886235421526.56231689
#Sta/Elev= 21
       0  176.02    4.81  176.04   13.03  174.17      16  173.93   41.51  170.86
   45.37  169.57   47.78 168.396   48.08  168.25   50.46  168.32    61.7  168.67
   76.06  169.53   77.43  169.73   80.16  170.75   89.65  174.01   92.21  174.45
   95.66  174.69  106.19  175.11  125.01  176.84  129.12   176.9  131.74  177.36
  137.36  177.79
#Mann= 3 , 0 , 0
       0    .057       0   47.78    .037       0   50.46    .057       0
Bank Sta=47.78,50.46
XS Rating Curve= 0 ,0
Exp/Cntr=0.3,0.1

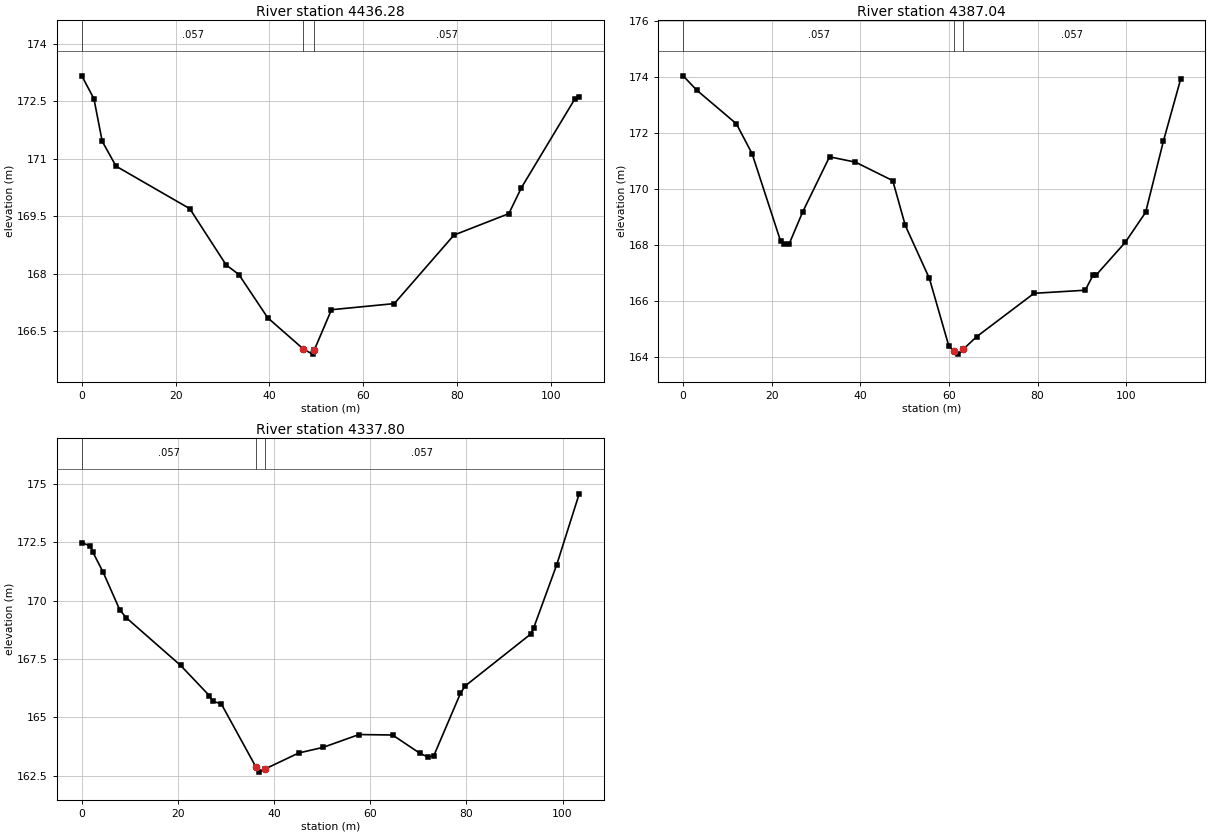
Type RM Length L Ch R = 1 ,4436.28 ,49.6,49.24,49.91
XS GIS Cut Line= 2
342514.9763183595421651.73468018342609.2982788095421603.30792236
#Sta/Elev= 18
       0  173.17    2.59  172.57    4.35  171.46     7.3  170.81   23.01   169.7
   30.77  168.23   33.48  167.98   39.63  166.85   47.26  166.03   49.18   165.9
   49.54 166.001   53.22  167.06   66.62  167.22   79.33  169.01   91.03  169.57
   93.72  170.25  105.12  172.57  106.03  172.61
#Mann= 3 , 0 , 0
       0    .057       0   47.26    .037       0   49.54    .057       0
Bank Sta=47.26,49.54
XS Rating Curve= 0 ,0
Exp/Cntr=0.3,0.1

Type RM Length L Ch R = 1 ,4387.04 ,46.3,49.24,50.07
XS GIS Cut Line= 5
342529.6284790045421685.46728516342563.0474853525421672.84527588
342570.367919922 5421677.3192749342608.3071289065421658.34008789
342632.8118896485421651.14147949
#Sta/Elev= 26
       0  174.04    3.06  173.53   12.01  172.33   15.57  171.26      22  168.14
   22.75  168.03    23.9  168.03   26.97  169.18   33.04  171.15    38.9  170.96
   47.31   170.3   50.14   168.7   55.58  166.81   59.96   164.4   61.19  164.21
   62.09  164.11   63.19  164.28   66.23  164.73    79.2  166.28   90.75  166.39
   92.49  166.92    93.2  166.93   99.79   168.1  104.38  169.17  108.41  171.72
  112.26  173.91
#Mann= 3 , 0 , 0
       0    .057       0   61.19    .037       0   63.19    .057       0
Bank Sta=61.19,63.19
XS Rating Curve= 0 ,0
Exp/Cntr=0.3,0.1

Type RM Length L Ch R = 1 ,4337.80 ,50.62,49.24,33.92
XS GIS Cut Line= 3
342552.150695801 5421724.3861084342620.3140869145421706.85028076
342649.2227172855421690.75970459
#Sta/Elev= 26
       0  172.48    1.81  172.33     2.3  172.07    4.45  171.21     7.9   169.6
    9.21  169.27   20.56  167.22   26.56  165.92   27.28  165.68      29  165.58
   36.17  162.89   36.78  162.65   38.17  162.79   45.13  163.47   50.19  163.71
   57.67  164.26   64.65  164.24   70.38  163.45   72.09  163.29   73.24  163.36
   78.76  166.02   79.74  166.34   93.36  168.56   93.97  168.81   98.79  171.53
  103.47  174.57
#Mann= 3 , 0 , 0
       0    .057       0   36.17    .037       0   38.17    .057       0
Bank Sta=36.17,38.17
XS Rating Curve= 0 ,0
Exp/Cntr=0.3,0.1