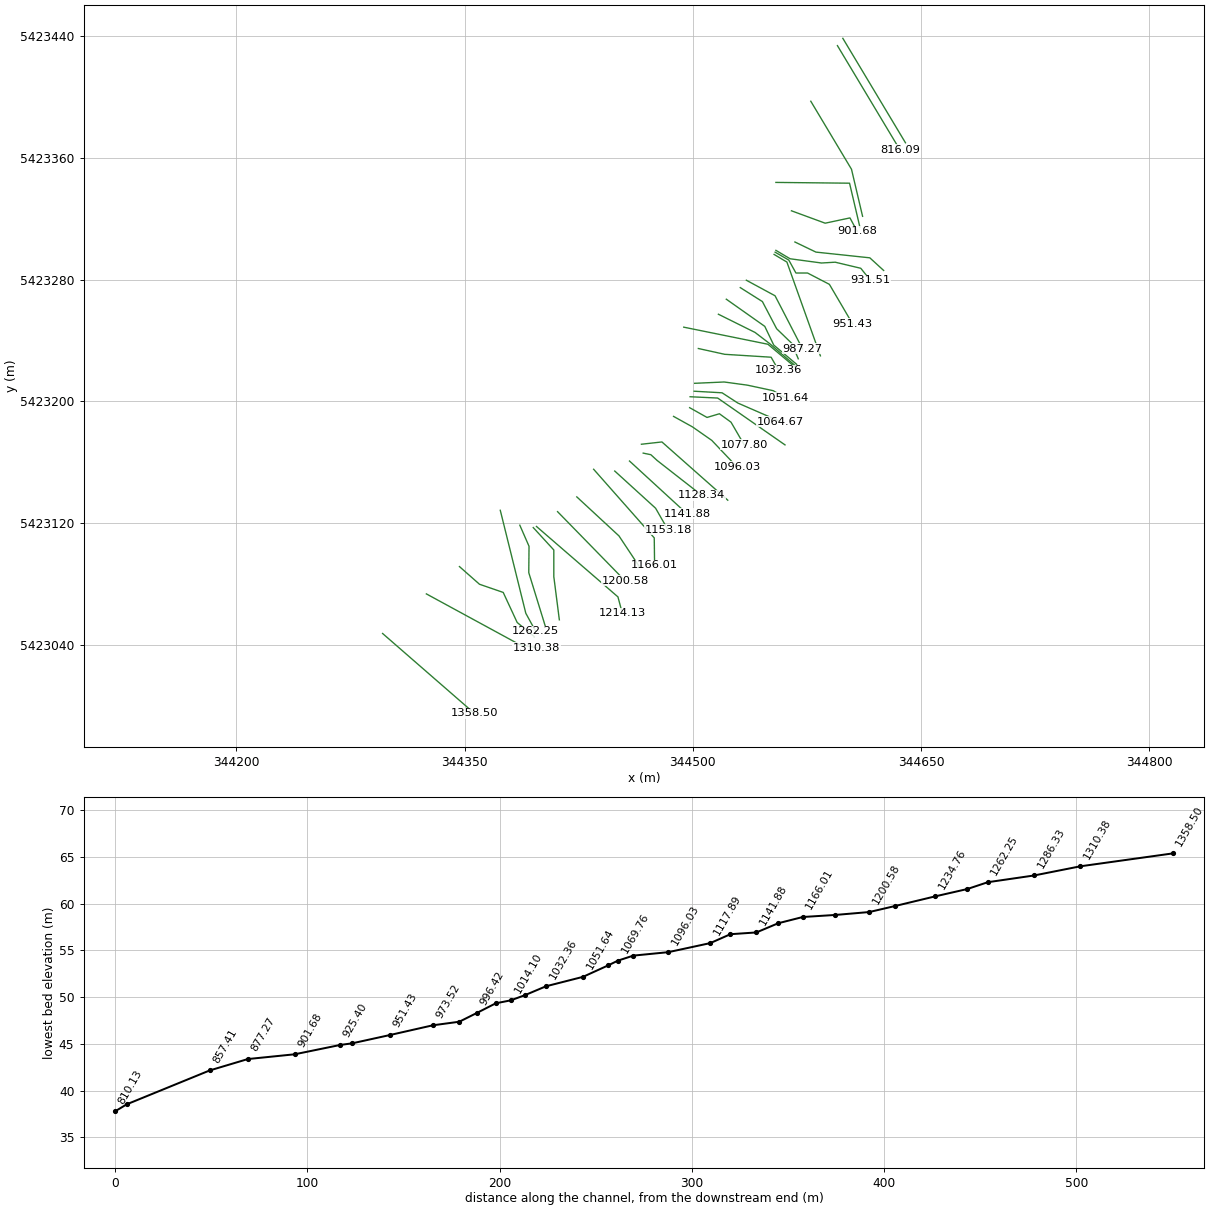
HEC-RAS study Corner_Brook2.prj: Corner_Brook2

--- Corner_Brook2.g01 (geometry) --- (continued)

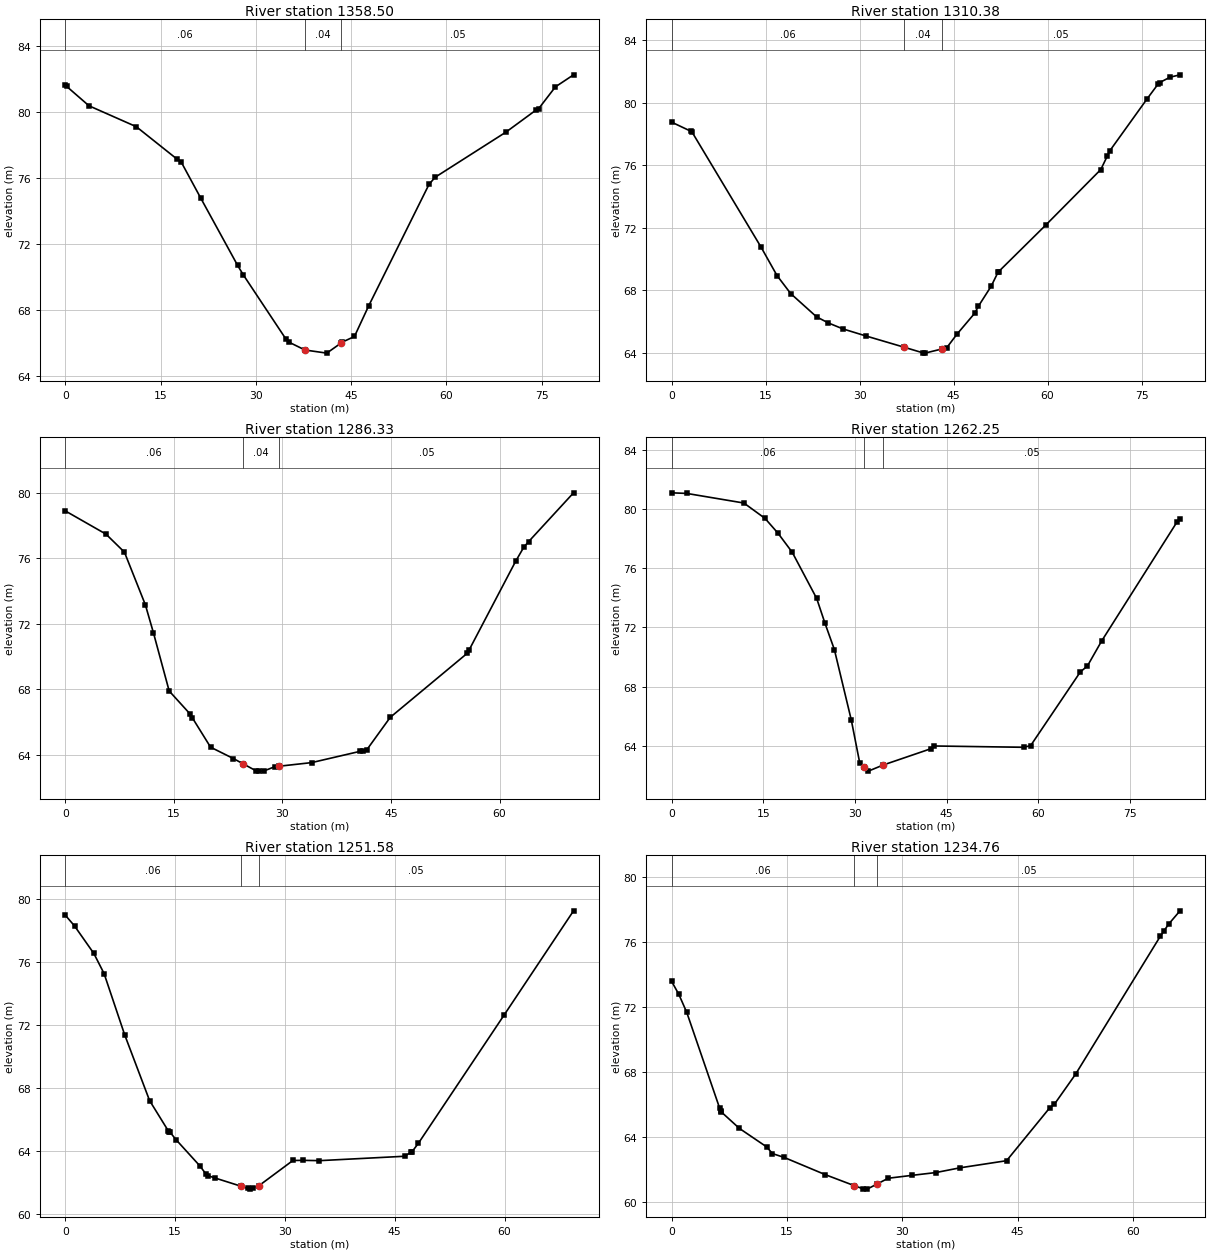
Type RM Length L Ch R = 1 ,1358.50 ,45.41,48.12,49.91
XS GIS Cut Line= 2
344296.0416870125423047.56292725344356.4254760745422995.08648682
#Sta/Elev= 24
       0   81.66     .22   81.57    3.74   80.39   11.19   79.12   17.57   77.16
   18.22      77   21.35   74.77   27.13    70.7      28   70.14   34.76   66.21
   35.19   66.04   37.73   65.56   41.17   65.37   43.44   65.99   43.61   66.04
   45.52   66.38   47.76   68.24   57.26   75.62   58.22   76.05   69.36   78.79
   74.13   80.14    74.5   80.21   77.15   81.54      80   82.27
#Mann= 3 , 0 , 0
       0     .06       0   37.73     .04       0   43.44     .05       0
Bank Sta=37.73,43.44
XS Rating Curve= 0 ,0
Exp/Cntr=0.3,0.1

Type RM Length L Ch R = 1 ,1310.38 ,22.48,24.05,23.98
XS GIS Cut Line= 3
344324.8247070315423073.56048584344385.9348754885423040.35491943
344397.3156738285423038.21850586
#Sta/Elev= 30
       0   78.77    3.06   78.19    3.29   78.11   14.27   70.77   16.82   68.95
      19    67.8   23.13   66.31   25.02   65.92   27.33   65.54   30.99   65.09
      37   64.38   40.17      64   40.42   63.99   43.07   64.25   43.87   64.32
   45.53    65.2   48.38   66.55   48.95   66.99   50.99   68.27   52.08   69.16
   52.17    69.2   59.67   72.17   68.49   75.74   69.55   76.62   69.93   76.94
   75.91   80.28   77.69   81.24   77.86    81.3   79.55   81.65   81.13    81.8
#Mann= 3 , 0 , 0
       0     .06       0      37     .04       0   43.07     .05       0
Bank Sta=37,43.07
XS Rating Curve= 0 ,0
Exp/Cntr=0.3,0.1

Type RM Length L Ch R = 1 ,1286.33 ,28.88,24.08,12.48
XS GIS Cut Line= 5
344346.5858764655423091.49310303344359.7540893555423079.89208984
344375.348327637 5423074.5244751344384.5314941415423054.78552246
344395.6204833985423045.60870361
#Sta/Elev= 27
       0   78.89    5.63   77.47    8.18   76.37   11.07   73.16   12.18   71.46
   14.36    67.9   17.24    66.5   17.55   66.27   20.08   64.47   23.22   63.78
   24.56   63.46   26.31   63.04    26.8   63.01   27.39   63.01   28.94   63.28
   29.56   63.31   34.04   63.53   40.75   64.22   41.07   64.26   41.67   64.32
   44.89   66.29   55.53    70.2   55.81   70.42   62.21   75.81   63.35   76.68
      64   77.01   70.21   79.99
#Mann= 3 , 0 , 0
       0     .06       0   24.56     .04       0   29.56     .05       0
Bank Sta=24.56,29.56
XS Rating Curve= 0 ,0
Exp/Cntr=0.3,0.1

Type RM Length L Ch R = 1 ,1262.25 ,11.71,10.67,8.64
XS GIS Cut Line= 3
344373.4210815435423128.46972656344390.2106933595423060.81689453
344396.6876831055423048.99932861
#Sta/Elev= 23
       0    81.1    2.46   81.06   11.82   80.41   15.28   79.37    17.4   78.37
   19.73   77.08   23.73   73.96   25.09   72.28   26.62   70.51   29.39   65.75
   30.78   62.83   31.42    62.6   32.18   62.29   34.59    62.7   42.46   63.81
   42.98   63.99   57.64    63.9   58.75   64.02   66.88      69   68.02   69.39
   70.35   71.08   82.66   79.11   83.18   79.34
#Mann= 3 , 0 , 0
       0     .06       0   31.42     .04       0   34.59     .05       0
Bank Sta=31.42,34.59
XS Rating Curve= 0 ,0
Exp/Cntr=0.3,0.1

Type RM Length L Ch R = 1 ,1251.58 ,16.36,16.82,15.21
XS GIS Cut Line= 4
344386.2640991215423118.67730713344392.3284912115423104.82550049
344392.1552734385423087.51068115344403.0711059575423052.18829346
#Sta/Elev= 28
       0   78.98    1.27   78.29    3.91   76.54    5.31   75.26    8.12   71.37
   11.52   67.19   14.08   65.26   14.19   65.21   14.33   65.17   15.12   64.71
   18.38   63.04   19.27   62.49   19.53   62.41   20.51   62.26   24.03  61.741
   24.92   61.61   25.18   61.56   25.71   61.65   26.46   61.78   31.09   63.38
   32.44   63.39   34.72   63.37   46.38   63.65   47.27   63.93   47.36   63.94
   48.22   64.47   59.95   72.64   69.41   79.25
#Mann= 3 , 0 , 0
       0     .06       0   24.03     .04       0   26.46     .05       0
Bank Sta=24.03,26.46
XS Rating Curve= 0 ,0
Exp/Cntr=0.3,0.1

Type RM Length L Ch R = 1 ,1234.76 ,6.86,20.63,23.19
XS GIS Cut Line= 4
344395.1008911135423117.11907959344408.6157226565423102.40148926
344408.6157226565423084.91333008344412.2542724615423056.51708984
#Sta/Elev= 27
       0   73.55     .92   72.77    1.96   71.65    6.24   65.75    6.41   65.55
    6.43   65.53     8.8   64.51   12.38   63.36   13.09   62.96   14.63   62.72
   19.98   61.66   23.71   60.99   24.93   60.78   25.42   60.77   26.76  61.098
   28.16   61.44   31.29   61.62   34.35   61.79   37.47   62.08   43.55   62.52
   49.17   65.78   49.76   65.99   52.53   67.85   63.56   76.35   64.04   76.68
   64.62   77.08    66.1    77.9
#Mann= 3 , 0 , 0
       0     .06       0   23.71     .04       0   26.76     .05       0
Bank Sta=23.71,26.76
XS Rating Curve= 0 ,0
Exp/Cntr=0.3,0.1

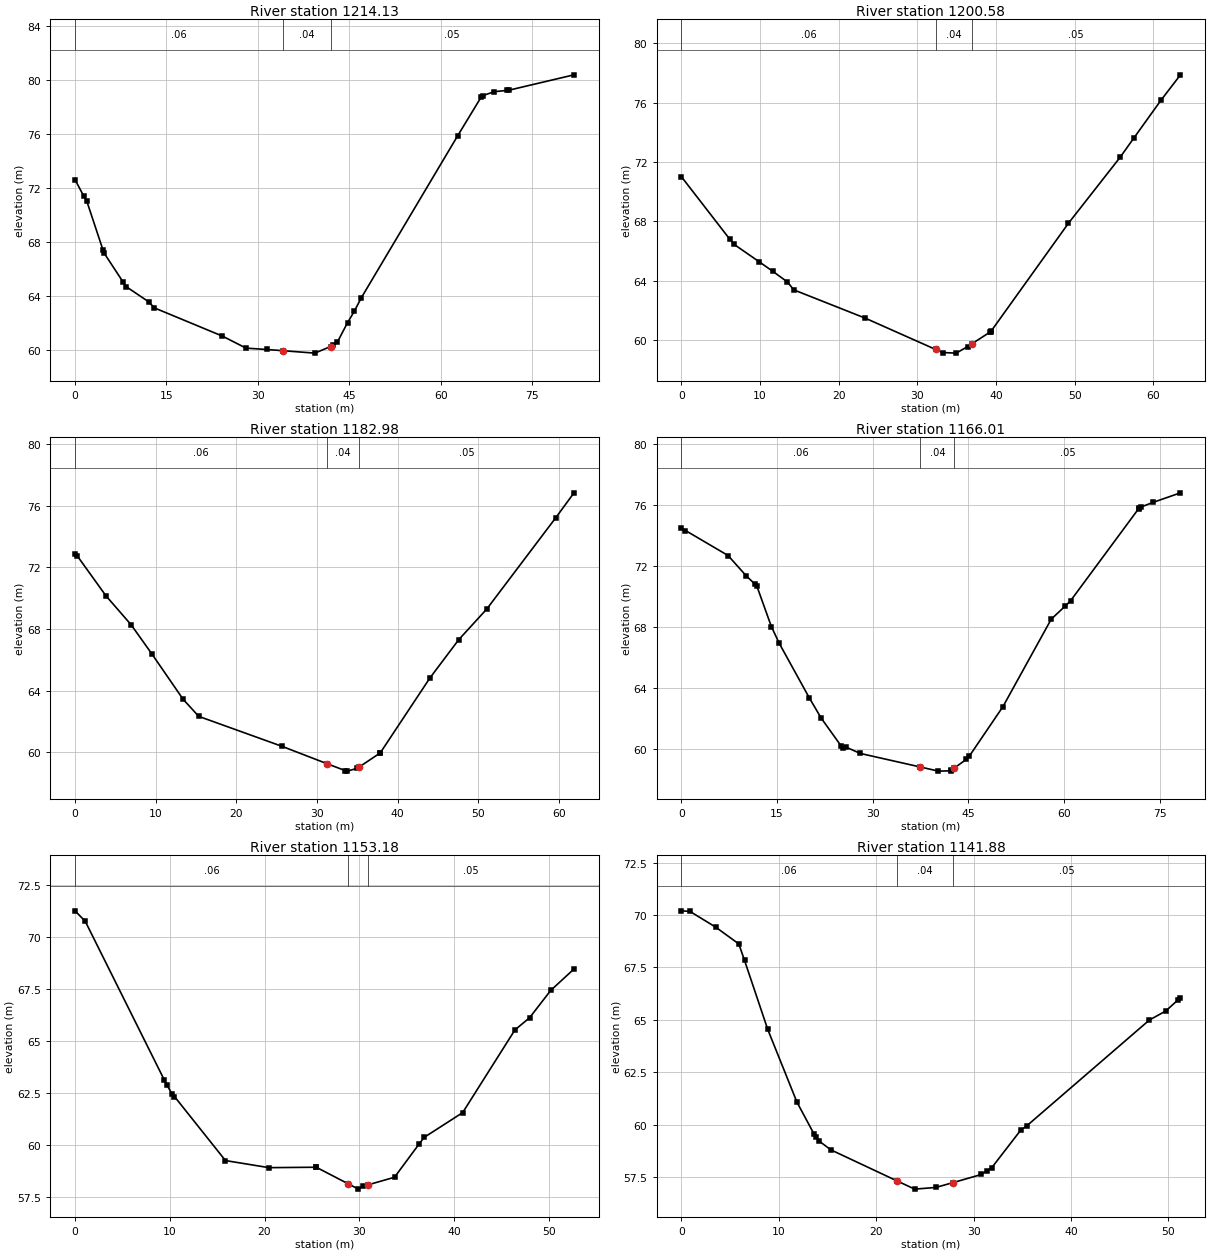
Type RM Length L Ch R = 1 ,1214.13 ,15.14,13.55,13.08
XS GIS Cut Line= 3
344397.2103271485423117.85131836344450.7780761725423071.59112549
344453.648925781 5423060.8928833
#Sta/Elev= 27
       0   72.62    1.41   71.41    1.91   71.05    4.58   67.41     4.8   67.15
    7.92      65    8.39   64.68   12.07   63.56   13.04    63.1   24.19   61.01
   28.06   60.12   31.45   60.02   34.11   59.93   39.34   59.75   41.92   60.24
   42.35   60.32   43.05   60.58   44.72   62.02    45.8   62.84   46.96   63.85
   62.78   75.87   66.65   78.75   66.92   78.84   68.74   79.13   70.78   79.22
   71.26   79.25   81.85   80.38
#Mann= 3 , 0 , 0
       0     .06       0   34.11     .04       0   41.92     .05       0
Bank Sta=34.11,41.92
XS Rating Curve= 0 ,0
Exp/Cntr=0.3,0.1

Type RM Length L Ch R = 1 ,1200.58 ,17.09,17.6,17.74
XS GIS Cut Line= 2
344411.0806884775423127.57507324344455.4373168955423082.21032715
#Sta/Elev= 21
       0      71    6.14   66.79    6.66   66.45    9.87   65.27   11.64   64.61
   13.48    63.9   14.28   63.37   23.37   61.46   32.31   59.35    33.2   59.14
   34.93    59.1   36.39   59.54    36.9   59.72   39.18    60.5    39.3   60.53
   39.37   60.58    49.2   67.86   55.77   72.31   57.53   73.62   61.02    76.2
   63.45   77.88
#Mann= 3 , 0 , 0
       0     .06       0   32.31     .04       0    36.9     .05       0
Bank Sta=32.31,36.9
XS Rating Curve= 0 ,0
Exp/Cntr=0.3,0.1

Type RM Length L Ch R = 1 ,1182.98 ,17.91,16.97,16.65
XS GIS Cut Line= 3
344423.7293090825423137.27148438344451.4520874025423111.64550781
344464.7937011725423091.56030273
#Sta/Elev= 20
       0   72.88     .27   72.75    3.83   70.16    6.97   68.27    9.54   66.38
    13.4   63.45   15.34   62.34   25.65    60.4   31.25   59.27   33.47   58.83
   33.78   58.79   35.02   58.98   35.24   59.06   37.75   59.94   37.84   59.97
      44   64.83   47.57   67.31   51.05    69.3   59.62   75.23   61.86   76.83
#Mann= 3 , 0 , 0
       0     .06       0   31.25     .04       0   35.24     .05       0
Bank Sta=31.25,35.24
XS Rating Curve= 0 ,0
Exp/Cntr=0.3,0.1

Type RM Length L Ch R = 1 ,1166.01 ,11.83,12.83,13.49
XS GIS Cut Line= 3
344434.7974853525423155.41571045344474.6513061525423110.34112549
344474.8782958985423092.27392578
#Sta/Elev= 30
       0   74.51     .63   74.34    7.31    72.7   10.15   71.37   11.57   70.81
   11.82    70.7   14.11   68.03   15.34   66.94   20.02   63.39    21.9   62.05
      25   60.24   25.33   60.08   25.77   60.15   28.03   59.73   37.46   58.84
   40.29   58.57   42.21   58.59   42.28   58.62   42.81   58.78   44.66   59.34
    45.1   59.53   50.41    62.8   57.98   68.53   60.17   69.39      61   69.73
   71.68   75.77   71.77   75.79   72.05   75.88   73.99   76.19   78.24   76.81
#Mann= 3 , 0 , 0
       0     .06       0   37.46     .04       0   42.81     .05       0
Bank Sta=37.46,42.81
XS Rating Curve= 0 ,0
Exp/Cntr=0.3,0.1

Type RM Length L Ch R = 1 ,1153.18 ,11.32,11.3,11.26
XS GIS Cut Line= 3
344448.679870605 5423154.2401123344475.5363159185423129.82611084
344483.6798706055423115.62792969
#Sta/Elev= 22
       0   71.25    1.08   70.75    9.42   63.14     9.7   62.89   10.27   62.45
    10.5   62.34   15.88   59.27   20.47   58.93   25.39   58.95   25.46   58.95
   28.81   58.16   29.91    57.9   30.37   58.04   30.96   58.11   33.72   58.47
   36.29   60.05   36.84   60.38   40.91   61.57   46.43   65.54   47.97   66.12
    50.2   67.43   52.66   68.46
#Mann= 3 , 0 , 0
       0     .06       0   28.81     .04       0   30.96     .05       0
Bank Sta=28.81,30.96
XS Rating Curve= 0 ,0
Exp/Cntr=0.3,0.1

Type RM Length L Ch R = 1 ,1141.88 ,13.01,13.54,14.12
XS GIS Cut Line= 2
344458.3828735355423160.81970215344496.1552734385423126.18988037
#Sta/Elev= 24
       0    70.2     .88   70.17    3.52   69.42    5.89   68.62    6.48   67.83
    8.86   64.54   11.86   61.07    13.6   59.56   13.81   59.43   14.11   59.22
   15.36   58.79    22.1   57.32   23.95   56.92   26.11      57   27.88   57.23
    30.8   57.62   31.36    57.8   31.84   57.93   34.83   59.73   35.46   59.94
   48.05   64.99   49.73   65.42   50.94   65.93   51.24   66.04
#Mann= 3 , 0 , 0
       0     .06       0    22.1     .04       0   27.88     .05       0
Bank Sta=22.1,27.88
XS Rating Curve= 0 ,0
Exp/Cntr=0.3,0.1

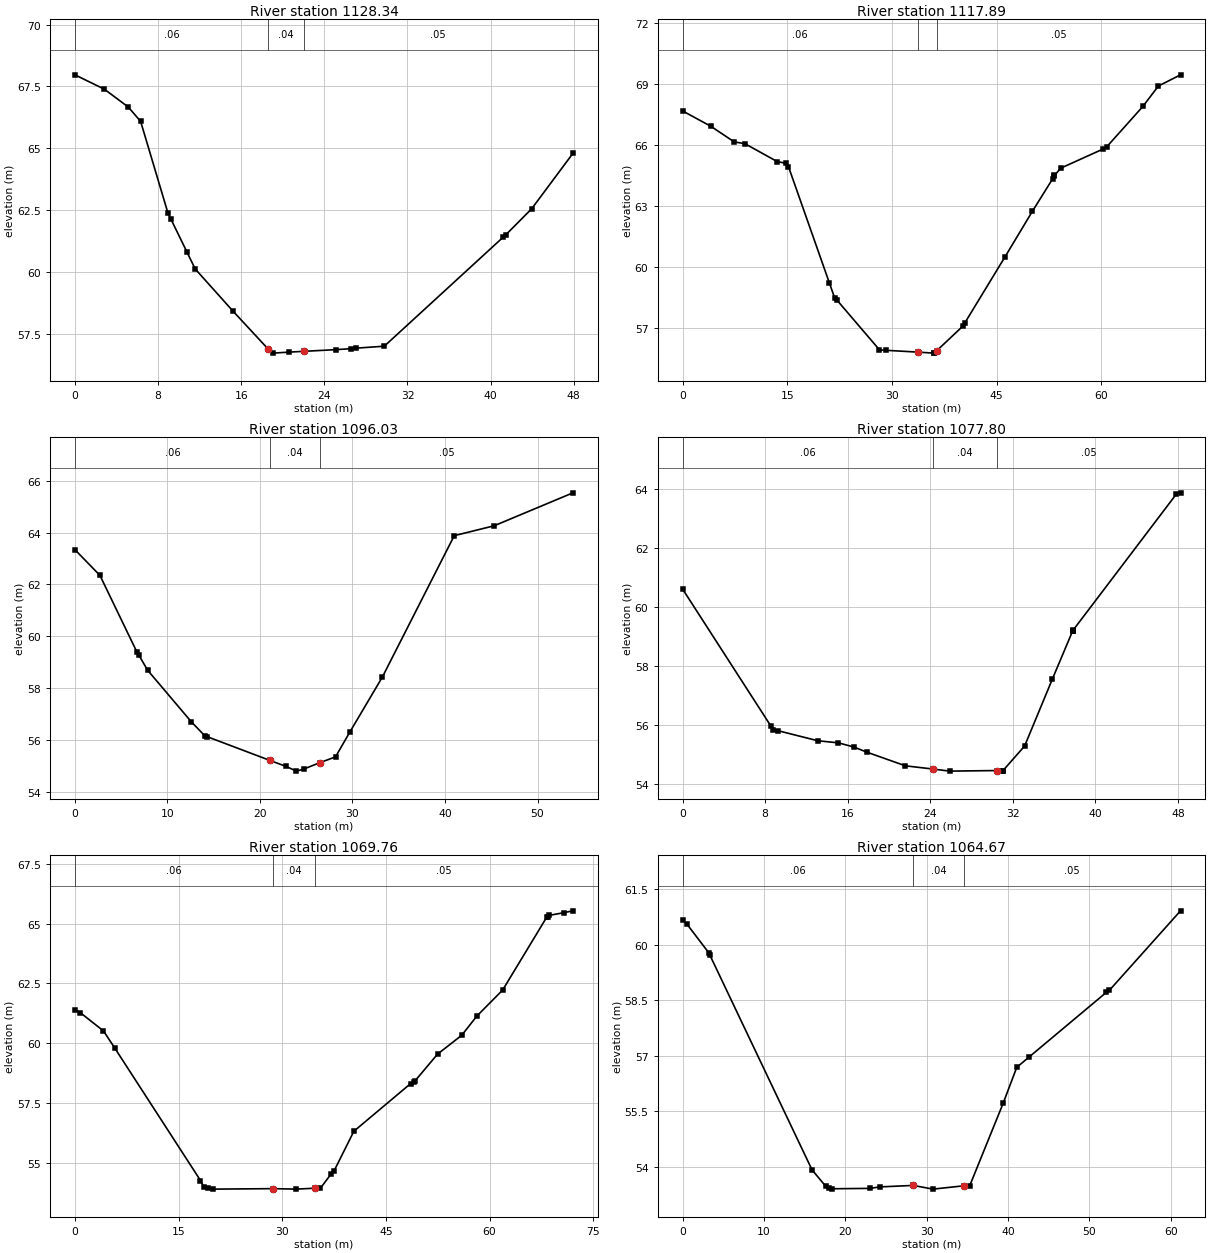
Type RM Length L Ch R = 1 ,1128.34 ,10.91,10.45,10
XS GIS Cut Line= 4
344467.3927001955423166.01409912344472.4174804695423164.97528076
344476.5759277345423161.16607666344505.8582763675423138.31048584
#Sta/Elev= 21
       0   67.97    2.83   67.39    5.13   66.67    6.32   66.09    8.94    62.4
    9.25   62.13   10.77   60.82   11.57   60.13    15.2   58.43   18.58    56.9
   19.08   56.73   20.57   56.77   22.01  56.802   25.08   56.87   26.58   56.91
   27.02   56.93   29.77   57.01    41.2   61.41   41.44    61.5   43.95   62.56
   47.92    64.8
#Mann= 3 , 0 , 0
       0     .06       0   18.58     .04       0   22.01     .05       0
Bank Sta=18.58,22.01
XS Rating Curve= 0 ,0
Exp/Cntr=0.3,0.1

Type RM Length L Ch R = 1 ,1117.89 ,21.15,21.85,22.43
XS GIS Cut Line= 3
344466.2083129885423171.84667969344479.6917114265423173.35028076
344522.9801025395423135.09832764
#Sta/Elev= 29
       0   67.67    4.08   66.91    7.39   66.15    8.94   66.06   13.57   65.18
    14.8    65.1   15.17   64.94   21.02   59.24   21.77   58.51    22.1   58.39
   28.21   55.94   29.08   55.92    33.7   55.83   36.03   55.78   36.05   55.78
   36.43  55.903   40.23   57.13   40.43   57.26    46.2   60.51   50.11   62.74
   53.02   64.34    53.2   64.46   53.27    64.5   54.18   64.86   60.25    65.8
    60.8   65.92   65.94   67.89   68.16   68.89   71.33   69.44
#Mann= 3 , 0 , 0
       0     .06       0    33.7     .04       0   36.43     .05       0
Bank Sta=33.7,36.43
XS Rating Curve= 0 ,0
Exp/Cntr=0.3,0.1

Type RM Length L Ch R = 1 ,1096.03 ,13.27,18.23,17.07
XS GIS Cut Line= 4
344487.350524902 5423190.1350708344499.8256835945423183.20928955
344512.4743041995423174.37872314344529.1080932625423156.89068604
#Sta/Elev= 19
       0   63.34     2.7   62.35    6.71   59.39    6.89   59.29    7.85    58.7
   12.58   56.71   14.04   56.17   14.27   56.14   21.09   55.22   22.83   54.99
   23.94   54.81   24.73   54.89   26.51   55.14   28.17   55.36   29.69    56.3
   33.24   58.44      41   63.88   45.31   64.26   53.83   65.53
#Mann= 3 , 0 , 0
       0     .06       0   21.09     .04       0   26.51     .05       0
Bank Sta=21.09,26.51
XS Rating Curve= 0 ,0
Exp/Cntr=0.3,0.1

Type RM Length L Ch R = 1 ,1077.80 ,12.22,8.04,9.07
XS GIS Cut Line= 5
344497.9199218755423195.84912109344509.3555297855423189.44268799
344517.4990844735423191.86669922344525.1229248055423186.32592773
344533.7863159185423171.43511963
#Sta/Elev= 22
       0   60.62    8.56   55.97     8.8   55.84    9.27   55.81   13.11   55.47
   15.09    55.4   16.59   55.26   17.89   55.08    21.6   54.62   24.29   54.51
   25.89   54.44   30.49   54.46   31.03   54.46   31.06   54.46   33.15   55.29
   35.85   57.57    37.8   59.19   37.81    59.2   37.83   59.21   37.85   59.22
   47.84   63.83   48.26   63.88
#Mann= 3 , 0 , 0
       0     .06       0   24.29     .04       0   30.49     .05       0
Bank Sta=24.29,30.49
XS Rating Curve= 0 ,0
Exp/Cntr=0.3,0.1

Type RM Length L Ch R = 1 ,1069.76 ,4.65,5.09,6.22
XS GIS Cut Line= 3
344498.2136840825423203.04608154 344516.359497075423202.18109131
344560.6187133795423171.40948486
#Sta/Elev= 27
       0    61.4     .75   61.28    4.13   60.51    5.73   59.81   18.17   54.26
    18.7   53.97   19.25   53.93      20    53.9   28.68   53.92   32.03    53.9
    34.8   53.94   35.53   53.94   37.09   54.54    37.5   54.66   40.37   56.32
   48.58   58.31   49.02   58.39   49.24   58.43   52.47   59.54   55.98   60.33
   58.16   61.13    61.9   62.22   68.33   65.29    68.4   65.29   68.63   65.34
   70.71   65.45   72.07   65.53
#Mann= 3 , 0 , 0
       0     .06       0   28.68     .04       0    34.8     .05       0
Bank Sta=28.68,34.8
XS Rating Curve= 0 ,0
Exp/Cntr=0.3,0.1

Type RM Length L Ch R = 1 ,1064.67 ,7.87,13.03,14.53
XS GIS Cut Line= 4
344500.8823242195423206.66711426344519.248718262 5423205.6282959
344529.6447143555423198.87548828344557.5408935555423186.75512695
#Sta/Elev= 20
       0   60.67     .51   60.56    3.25   59.77    3.37   59.71   15.92   53.91
   17.59   53.47   18.05   53.42    18.4    53.4   23.02   53.41   24.25   53.45
   28.36   53.49   30.79   53.39   34.57   53.48   35.28   53.47   39.41   55.71
   41.08   56.68    42.6   56.96   52.11   58.71   52.46   58.76   61.21   60.91
#Mann= 3 , 0 , 0
       0     .06       0   28.36     .04       0   34.57     .05       0
Bank Sta=28.36,34.57
XS Rating Curve= 0 ,0
Exp/Cntr=0.3,0.1

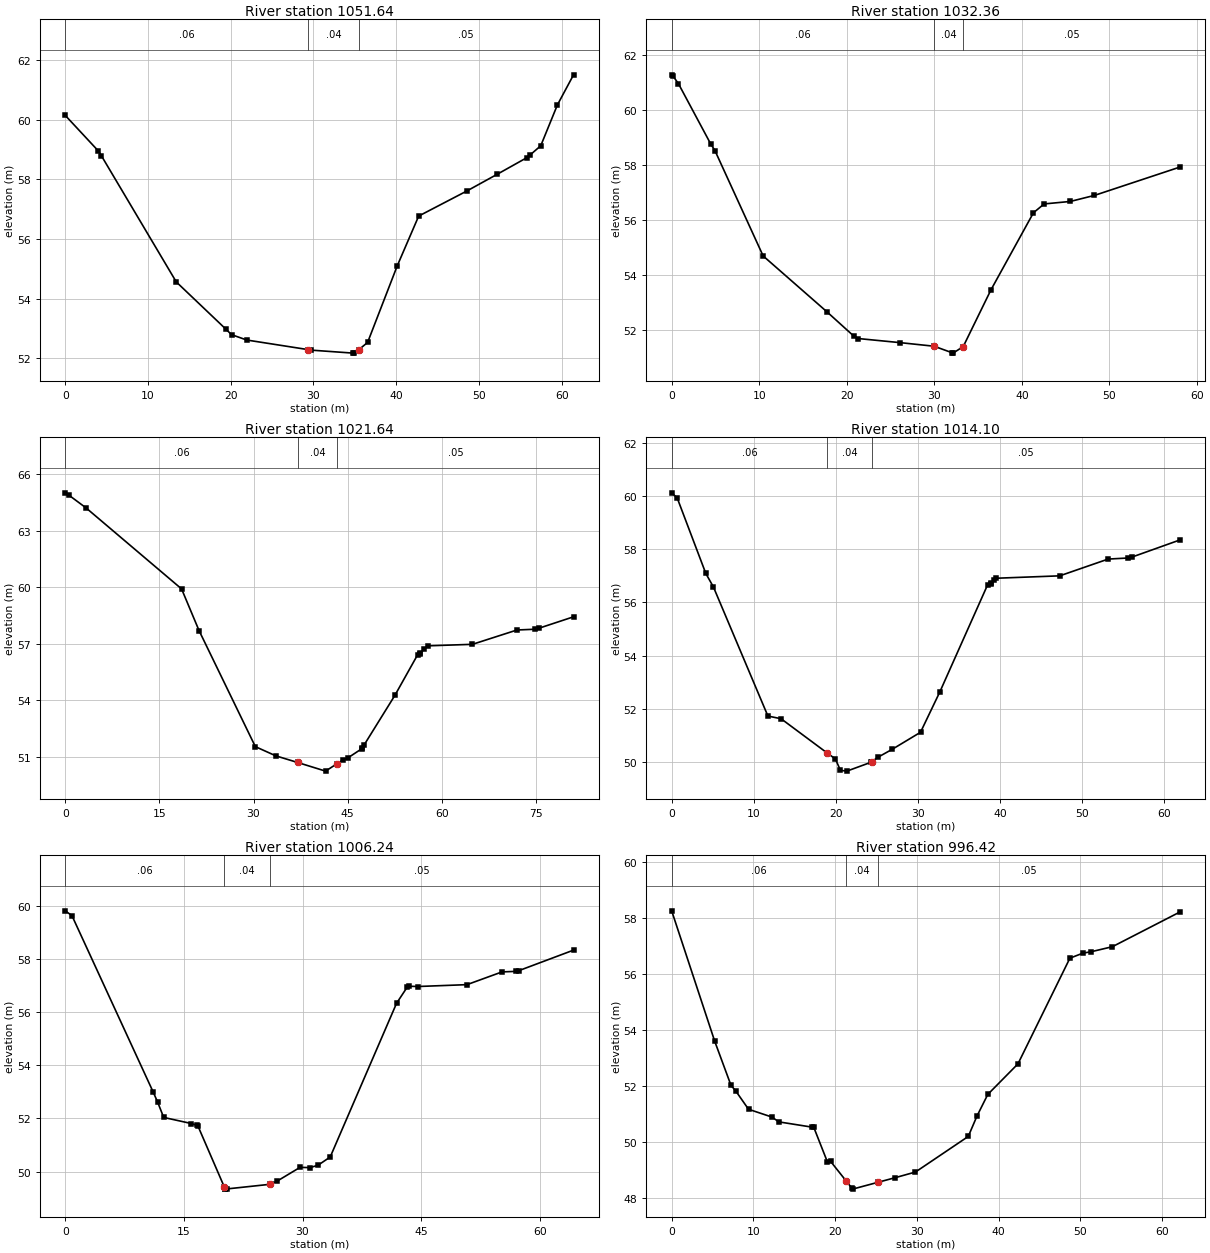
Type RM Length L Ch R = 1 ,1051.64 ,18.34,19.28,20.15
XS GIS Cut Line= 5
344501.2288818365423211.86169434344520.6348876955423212.72729492
344535.882324219 5423210.6494751344552.8624877935423207.01348877
344560.8328857425423202.33850098
#Sta/Elev= 22
       0   60.15    4.02   58.95    4.36    58.8   13.42   54.56   19.43   52.97
    20.1   52.79   21.93   52.61    29.3   52.29   29.74   52.27   34.81   52.17
   34.94   52.17    35.5   52.29   36.54   52.53   40.12    55.1   42.71   56.77
   48.52   57.61   52.18   58.17   55.78   58.73   56.13   58.81   57.46   59.13
   59.47    60.5   61.42   61.51
#Mann= 3 , 0 , 0
       0     .06       0    29.3     .04       0    35.5     .05       0
Bank Sta=29.3,35.5
XS Rating Curve= 0 ,0
Exp/Cntr=0.3,0.1

Type RM Length L Ch R = 1 ,1032.36 ,11.78,10.72,9.73
XS GIS Cut Line= 4
 344503.654479985423234.71728516344520.9813232425423230.90789795
344551.476501465 5423229.0032959344556.327880859  5423220.519104
#Sta/Elev= 20
       0   61.27     .12   61.24     .77   60.95    4.44   58.77    4.94   58.52
   10.45   54.69   17.74   52.66    20.8   51.78   21.31   51.69   26.13   51.54
   29.99   51.41   32.07   51.17   32.15   51.16   33.31    51.4   36.46   53.45
   41.33   56.26   42.55   56.58   45.54   56.67    48.3   56.89   58.07   57.92
#Mann= 3 , 0 , 0
       0     .06       0   29.99     .04       0   33.31     .05       0
Bank Sta=29.99,33.31
XS Rating Curve= 0 ,0
Exp/Cntr=0.3,0.1

Type RM Length L Ch R = 1 ,1021.64 ,9.54,7.54,5.22
XS GIS Cut Line= 3
344494.0515136725423248.73413086344549.3900756845423237.51171875
344568.1500854495423221.73791504
#Sta/Elev= 26
       0      65     .65   64.86    3.32    64.2   18.54    59.9   21.32   57.69
   30.29   51.53   33.56   51.04   37.02   50.69   41.48   50.23   43.33   50.63
   44.28   50.83   45.02   50.93    47.3   51.43   47.35   51.45   47.64   51.63
   52.52   54.25   56.15   56.41   56.47   56.47    56.6   56.48   57.16    56.7
   57.78   56.88   64.88   56.96   71.97   57.72   74.79   57.76   75.43   57.81
   80.98   58.42
#Mann= 3 , 0 , 0
       0     .06       0   37.02     .04       0   43.33     .05       0
Bank Sta=37.02,43.33
XS Rating Curve= 0 ,0
Exp/Cntr=0.3,0.1

Type RM Length L Ch R = 1 ,1014.10 ,8.95,7.86,6.39
XS GIS Cut Line= 4
344516.8228759775423257.22650146344540.9071044925423245.27929688
344550.4368896485423238.00708008344567.9368896485423222.94311523
#Sta/Elev= 26
       0   60.12     .67   59.93    4.16   57.09    5.09   56.58   11.73   51.73
   13.33   51.63   18.96   50.34   19.95   50.12   20.57   49.69   21.35   49.66
   24.27   49.99   24.42   50.02   25.13   50.18   26.88   50.48   30.33   51.12
   32.69   52.64   38.52   56.67   38.87   56.71   38.98   56.72   39.25   56.83
   39.56   56.91    47.3      57    53.2   57.63   55.61   57.67   56.15   57.71
   61.96   58.35
#Mann= 3 , 0 , 0
       0     .06       0   18.96     .04       0   24.42     .05       0
Bank Sta=18.96,24.42
XS Rating Curve= 0 ,0
Exp/Cntr=0.3,0.1

Type RM Length L Ch R = 1 ,1006.24 ,12.82,9.82,6.31
XS GIS Cut Line= 4
344522.0208740235423267.09588623344547.3181152345423249.26171875
344553.2091064455423236.96807861344568.2835083015423224.32830811
#Sta/Elev= 28
       0   59.82     .85   59.64    11.1   53.01   11.68   52.62   12.45   52.04
   15.95   51.81   16.66   51.74   16.76   51.73    20.1   49.43   20.18   49.36
   20.21   49.34   20.51   49.35   25.84   49.52   25.97   49.53   26.78   49.64
   29.69   50.16   30.95   50.15   31.96   50.24    33.5   50.55   41.89   56.34
   43.22   56.94   43.49   56.98   44.58   56.97   50.79   57.04   55.22   57.52
   56.97   57.54   57.37   57.57   64.26   58.34
#Mann= 3 , 0 , 0
       0     .06       0    20.1     .04       0   25.84     .05       0
Bank Sta=20.1,25.84
XS Rating Curve= 0 ,0
Exp/Cntr=0.3,0.1

Type RM Length L Ch R = 1 ,996.42  ,8.2,9.15,9.17
XS GIS Cut Line= 5
344531.2041015635423274.71447754344545.7587280275423265.53771973
344555.1151123055423247.70330811344565.1646728525423238.00708008
344569.3231201175423227.96447754
#Sta/Elev= 26
       0   58.24    5.26   53.59    7.26   52.01    7.82   51.82     9.4   51.16
   12.28   50.88    13.1   50.71   17.21   50.52   17.39   50.51   19.05   49.28
   19.44    49.3   21.36  48.595      22   48.36   22.12   48.31   25.24  48.554
   27.36   48.72   29.82   48.92   36.28   50.19   37.35   50.92   38.67   51.69
   42.36   52.78   48.71   56.55    50.3   56.73   51.31   56.78   53.91   56.96
   62.18    58.2
#Mann= 3 , 0 , 0
       0     .06       0   21.36     .04       0   25.24     .05       0
Bank Sta=21.36,25.24
XS Rating Curve= 0 ,0
Exp/Cntr=0.3,0.1

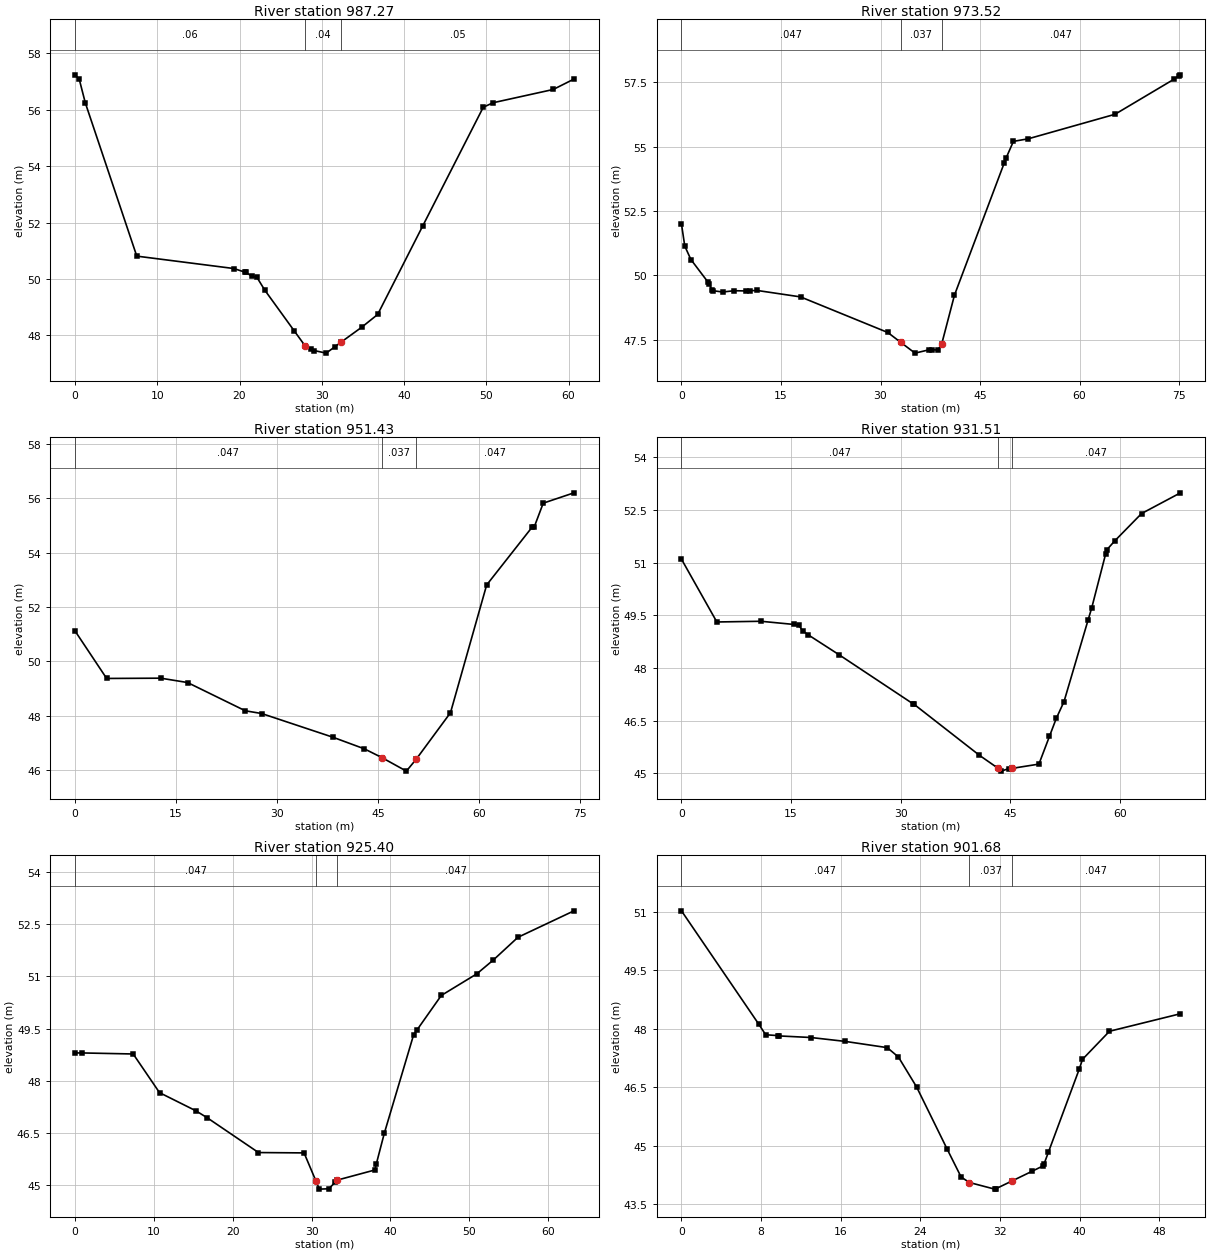
Type RM Length L Ch R = 1 ,987.27  ,17.06,13.75,13.19
XS GIS Cut Line= 4
 344535.189270025423279.56268311344554.0755004885423269.34692383
344558.7537231455423260.34307861344572.0952758795423234.54412842
#Sta/Elev= 24
       0   57.24     .52   57.08    1.25   56.25    7.51   50.81   19.32   50.37
   20.67   50.24   20.76   50.24   21.47    50.1   22.11   50.06   23.08    49.6
   26.65   48.16   27.99   47.62   28.63   47.51    29.1   47.46   30.53   47.37
   31.62    47.6   32.35   47.76   34.86   48.29   36.79   48.74   42.27   51.88
   49.63   56.09   50.82   56.25   58.13   56.72   60.66   57.09
#Mann= 3 , 0 , 0
       0     .06       0   27.99     .04       0   32.35     .05       0
Bank Sta=27.99,32.35
XS Rating Curve= 0 ,0
Exp/Cntr=0.3,0.1

Type RM Length L Ch R = 1 ,973.52  ,11.18,22.09,23.3
XS GIS Cut Line= 3
344553.4329223635423296.50427246344561.8582763675423291.50048828
344583.8804931645423229.90710449
#Sta/Elev= 29
       0      52      .5   51.14    1.42   50.62    4.04   49.73    4.18   49.68
    4.59   49.44    4.75   49.41    6.22   49.36    7.96   49.41     9.8    49.4
   10.28   49.41    11.4   49.42   17.95   49.17    31.1   47.79   33.04   47.41
    35.2   46.99   37.33   47.12   37.82   47.12   38.63   47.11   39.22   47.34
   41.15   49.24   48.66   54.37   48.94   54.56   50.03    55.2   52.27    55.3
   65.34   56.25   74.17    57.6   74.98   57.75   75.21   57.78
#Mann= 3 , 0 , 0
       0    .047       0   33.04    .037       0   39.22    .047       0
Bank Sta=33.04,39.22
XS Rating Curve= 0 ,0
Exp/Cntr=0.3,0.1

Type RM Length L Ch R = 1 ,951.43  ,14.71,19.93,24.34
XS GIS Cut Line= 6
344554.1068725595423297.98010254344563.1168823245423292.78552246
 344567.795104985423284.30133057344575.4188842775423284.30133057
344589.800109863  5423276.855896344605.0477294925423250.88372803
#Sta/Elev= 17
       0   51.12     4.7   49.37   12.74   49.38   16.71   49.22   25.29   48.18
   27.71   48.08   38.27   47.21   42.97   46.78   45.56   46.46   49.21   45.96
   50.68  46.402   55.76   48.11   61.13   52.81   67.89   54.94   68.22   54.96
   69.53   55.82    74.1    56.2
#Mann= 3 , 0 , 0
       0    .047       0   45.56    .037       0   50.68    .047       0
Bank Sta=45.56,50.68
XS Rating Curve= 0 ,0
Exp/Cntr=0.3,0.1

Type RM Length L Ch R = 1 ,931.51  ,6.29,6.11,6.81
XS GIS Cut Line= 6
344554.6267089845423299.19207764344563.9832763675423293.65130615
344584.6021118165423290.88092041344593.6121215825423291.40032959
344610.4188842775423287.41790771 344616.82989502  5423279.453125
#Sta/Elev= 26
       0    51.1    4.84   49.31   10.87   49.33   15.36   49.24   16.04   49.22
   16.57   49.06   17.29   48.95   21.53   48.38   31.73   46.97   31.84   46.96
   40.76   45.51   43.31   45.14   43.75   45.06   44.73   45.13   45.26   45.14
   48.89   45.26   50.33   46.05   51.26   46.56   52.32   47.04   55.62   49.37
   56.11   49.71   58.03   51.26   58.19   51.37   59.26   51.62   62.93    52.4
   68.25   52.99
#Mann= 3 , 0 , 0
       0    .047       0   43.31    .037       0   45.26    .047       0
Bank Sta=43.31,45.26
XS Rating Curve= 0 ,0
Exp/Cntr=0.3,0.1

Type RM Length L Ch R = 1 ,925.40  ,20.85,23.72,25.32
XS GIS Cut Line= 4
 344567.13067627 5423304.6663208344580.9411010745423298.03607178
344616.3770751955423294.27911377344625.477478027 5423285.9730835
#Sta/Elev= 23
       0    48.8     .89    48.8    7.38   48.77   10.72   47.66   15.32   47.14
   16.76   46.94   23.27   45.94   29.05   45.93   30.57  45.115   30.99   44.89
   32.18    44.9   33.01   45.09   33.27   45.15   38.03   45.44   38.22   45.62
   39.22   46.49   42.94   49.32   43.34   49.45   46.45   50.45   50.95   51.07
   53.06   51.47   56.17   52.12   63.28   52.88
#Mann= 3 , 0 , 0
       0    .047       0   30.57    .037       0   33.27    .047       0
Bank Sta=30.57,33.27
XS Rating Curve= 0 ,0
Exp/Cntr=0.3,0.1

Type RM Length L Ch R = 1 ,901.68  ,25.83,24.41,23.27
XS GIS Cut Line= 4
344564.8494873055423325.16430664344587.0278930665423317.02648926
344603.3148803715423320.48931885344607.9932861335423311.83190918
#Sta/Elev= 24
       0   51.03    7.77   48.12    8.46   47.85    9.65   47.83    9.84   47.82
      13   47.78   16.45   47.68   20.67   47.52   21.79   47.28   23.62   46.51
   26.66   44.93   28.09    44.2   28.92   44.06   31.46   43.89   31.58    43.9
   33.23  44.103   35.23   44.35   36.35   44.49   36.41   44.53   36.86   44.84
   39.97   46.98   40.28   47.22   42.99   47.94   50.12   48.39
#Mann= 3 , 0 , 0
       0    .047       0   28.92    .037       0   33.23    .047       0
Bank Sta=28.92,33.23
XS Rating Curve= 0 ,0
Exp/Cntr=0.3,0.1

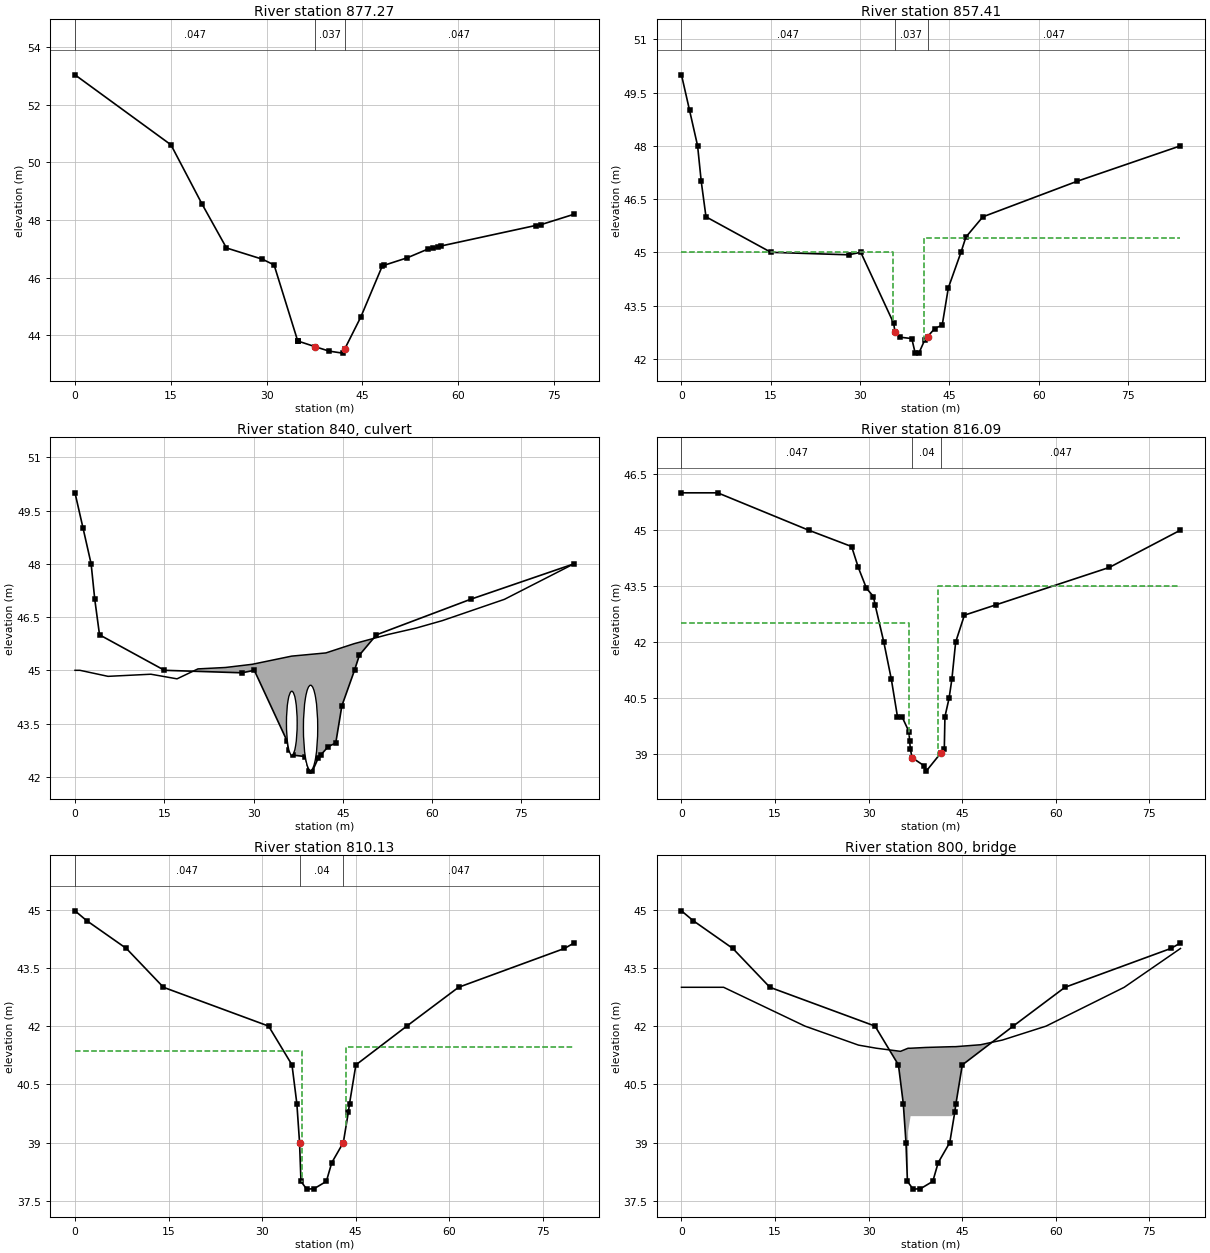
Type RM Length L Ch R = 1 ,877.27  ,29.64,19.87,13.78
Node Photo=..\..\..\Corner Brook\Windshield Survey\CB photos\Google\2119 US.jpg
XS GIS Cut Line= 3
344554.6296997075423343.80212402344603.0496826175423343.29449463
344609.8696899415423314.36651611
#Sta/Elev= 24
       0   53.04   15.03   50.61   19.88   48.56   23.72   47.03   29.35   46.64
   31.18   46.44   34.88    43.8   34.89    43.8    34.9    43.8   37.51   43.61
   39.79   43.45   41.89   43.38   42.23   43.52   44.77   44.64   48.11    46.4
   48.42   46.43   52.04   46.69   55.35      47   56.08   47.02   56.85   47.06
   57.34    47.1   72.12   47.81   72.97   47.84   78.14    48.2
#Mann= 3 , 0 , 0
       0    .047       0   37.51    .037       0   42.23    .047       0
Bank Sta=37.51,42.23
XS Rating Curve= 0 ,0
Exp/Cntr=0.3,0.1

Type RM Length L Ch R = 1 ,857.41  ,43,43.13,43.22
Node Photo=..\..\..\Corner Brook\Windshield Survey\CB photos\P1000700.JPG
XS GIS Cut Line= 4
      344577.572      5423397.11      344604.327     5423352.442
      344604.327     5423352.442      344611.617      5423321.54
#Sta/Elev= 24
       0      50    1.36      49    2.71      48    3.32      47    4.12      46
   15.03      45   28.06   44.93   30.12      45   35.65      43   35.87   42.75
   36.66   42.61   38.69   42.57   39.26   42.16   39.88   42.16   40.89   42.54
   41.35  42.627   42.55  42.853    43.8   42.95   44.83      44   46.95      45
   47.78   45.43   50.63      46   66.44      47   83.82      48
#Mann= 3 , 0 , 0
       0    .047       0   35.87    .037       0   41.35    .047       0
#XS Ineff= 2 , 0
       0   35.52      45   40.77       0    45.4
Permanent Ineff=
       F       F
Bank Sta=35.87,41.35
XS Rating Curve= 0 ,0
Exp/Cntr=0.5,0.3

Type RM Length L Ch R = 2 ,840     ,,,
Node Photo=..\..\..\Corner Brook\Windshield Survey\CB photos\P1000697.JPG
BEGIN DESCRIPTION:
Wellington Street (Structure #2119)
END DESCRIPTION:
Bridge Culvert--1,0,-1,-1, 0
Deck Dist Width WeirC Skew NumUp NumDn MinLoCord MaxHiCord MaxSubmerge Is_Ogee
8.7,16,1.67,0, 16, 16, 44.76, , 0.98, 0, 1,0.3,,
       0     .83    5.55   12.75   17.14   20.65   25.29   29.78    36.4   42.14
   46.88   52.62    57.3   61.71   72.14   83.81
      45      45   44.83   44.89   44.76   45.04   45.08   45.17    45.4   45.49
   45.75   46.01   46.19    46.4      47      48
                                                                                
                                                
       0    8.83   13.32   17.31   22.94   27.33   30.84   35.48   39.97   46.59
   52.32   57.07   62.81   67.49    71.9      80
      45      45   44.82   44.69   44.89   44.76   45.04   45.08   45.17    45.4
   45.49   45.75   46.01   46.19    46.4      47
                                                                                
                                                
BR Coef=-1 , 0 , 0 ,, 0 ,,,0.8,-1,,0,
WSPro=,,,, 1 ,,,, 0 ,,,, 0 ,,,,-1 ,-1 ,-1 , 0 , 0 , 0 , 0 , 0
Culvert=1,1.8,,40,0.03,0.5,1,1,1,42.61,36.42,38.79,37.42,Culvert #2  , 0 ,2
Culvert Bottom n=0.03
Culvert=1,2.4,,35.7,0.03,0.5,1,1,1,42.18,39.57,39.94,39.88,Culvert #1  , 0 ,4.75
Culvert Bottom n=0.03
BC Design=,, 0 ,, 0 ,,,,,,
BC Use User HTab Curves=0
BC User HTab FreeFlow(D)= 0

Type RM Length L Ch R = 1 ,816.09  ,5.75,5.97,5.64
Node Photo=..\..\..\Corner Brook\Windshield Survey\CB photos\Google\2119 DS.jpg
XS GIS Cut Line= 2
 344595.072082525423433.64447021344636.2438964845423365.05230713
#Sta/Elev= 28
       0      46    5.81      46   20.37      45   27.28   44.56   28.35      44
   29.66   43.44   30.78   43.22   31.04      43   32.44      42   33.65      41
   34.63      40   35.38   39.99   36.47    39.6   36.58   39.34   36.71   39.12
   36.97    38.9   38.85   38.69   39.24   38.54   41.55  39.018   42.14   39.14
   42.24      40    42.9   40.49   43.35      41   43.96      42   45.36   42.72
   50.46      43   68.59      44      80      45
#Mann= 3 , 0 , 0
       0    .047       0   36.97     .04       0   41.55    .047       0
#XS Ineff= 2 , 0
       0   36.52    42.5   41.07       0    43.5
Permanent Ineff=
       F       F
Bank Sta=36.97,41.55
XS Rating Curve= 0 ,0
Exp/Cntr=0.5,0.3

Type RM Length L Ch R = 1 ,810.13  ,13.89,13.76,13.13
Node Photo=..\..\..\Corner Brook\Windshield Survey\CB photos\Google\2118 US.jpg
XS GIS Cut Line= 2
 344598.634704595423438.42871094 344639.806701665423369.83648682
#Sta/Elev= 21
       0   44.97    1.85   44.72    8.24      44   14.18      43   31.04      42
   34.79      41   35.57      40      36      39   36.23      38   37.14    37.8
   38.32   37.81    40.3      38   41.16   38.48   43.02      39   43.82   39.78
   44.01      40   45.03      41   53.19      42   61.49      43   78.46      44
      80   44.14
#Mann= 3 , 0 , 0
       0    .047       0      36     .04       0   43.02    .047       0
#XS Ineff= 2 , 0
       0   36.33   41.35   43.45       0   41.47
Permanent Ineff=
       F       F
Bank Sta=36,43.02
XS Rating Curve= 0 ,0
Exp/Cntr=0.5,0.3

Type RM Length L Ch R = 3 ,800     ,,,
Node Photo=..\..\..\Corner Brook\Windshield Survey\CB photos\P1000695.JPG
BEGIN DESCRIPTION:
Blackwood's Hill Road (Structure #2118)
END DESCRIPTION:
Bridge Culvert--1,0,-1,-1, 0
Deck Dist Width WeirC Skew NumUp NumDn MinLoCord MaxHiCord MaxSubmerge Is_Ogee
1.3,6.5,1.67,0, 19, 19, 40.3, , 0.98, 0, 0,0,,
       0    6.76    19.8   28.39   31.26   35.12   36.33   36.34   36.74   39.15
   43.44   43.84   43.85   43.92   47.96   51.45   58.47   70.99   80.01
      43      43      42   41.51   41.43   41.35   41.43   41.43   41.43   41.45
   41.47   41.47   41.47   41.47   41.52   41.64      42      43      44
                                                      35   39.28   39.68   39.68
   39.68   39.28      35
       0    4.96   18.86   30.87   33.96   37.05   37.06   37.46   38.61   43.43
   44.23   44.56   44.57   47.15   50.75    56.9   68.35   76.01      80
      43      43      42   41.73   41.43   41.43   41.43   41.43   41.43   41.45
   41.47   41.47   41.47   41.52   41.64      42      43      43   43.09
                                              35   39.28   39.68   39.68   39.68
   39.68   39.28      35
BR Coef=-1 , 0 , 0 ,, 0 ,,,0.8,-1,,0,
WSPro=,,,, 1 ,,,, 0 ,,,, 0 ,,,,-1 ,-1 ,-1 , 0 , 0 , 0 , 0 , 0
BC Design=,, 0 ,, 0 ,,,,,,
BC Use User HTab Curves=0
BC User HTab FreeFlow(D)= 0