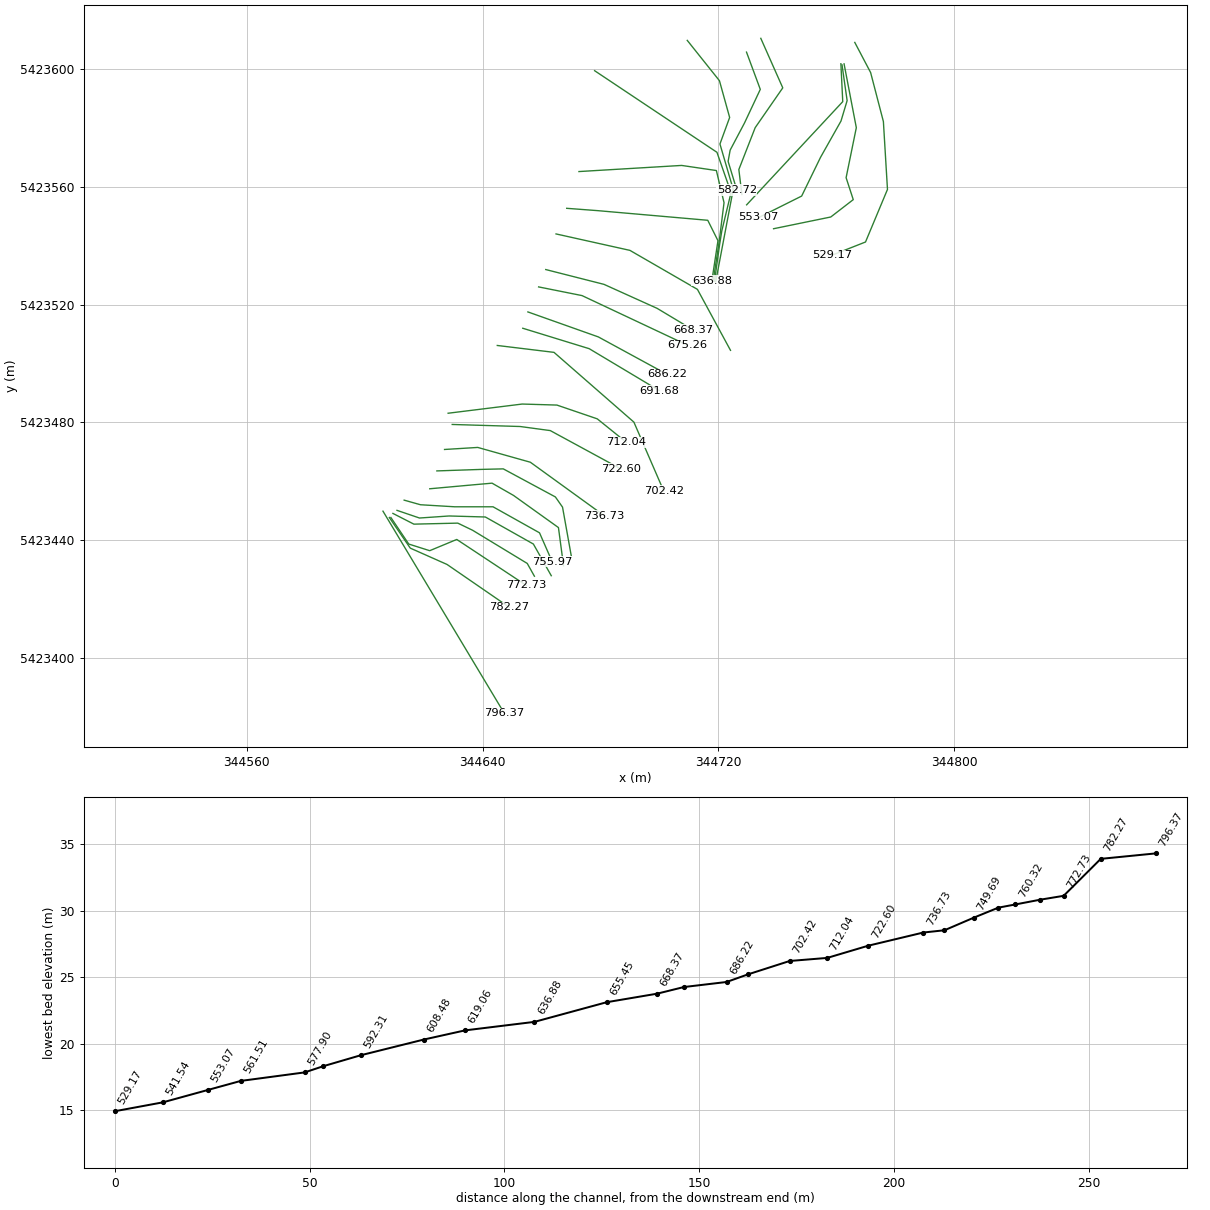
HEC-RAS study Corner_Brook2.prj: Corner_Brook2

--- Corner_Brook2.g01 (geometry) --- (continued)

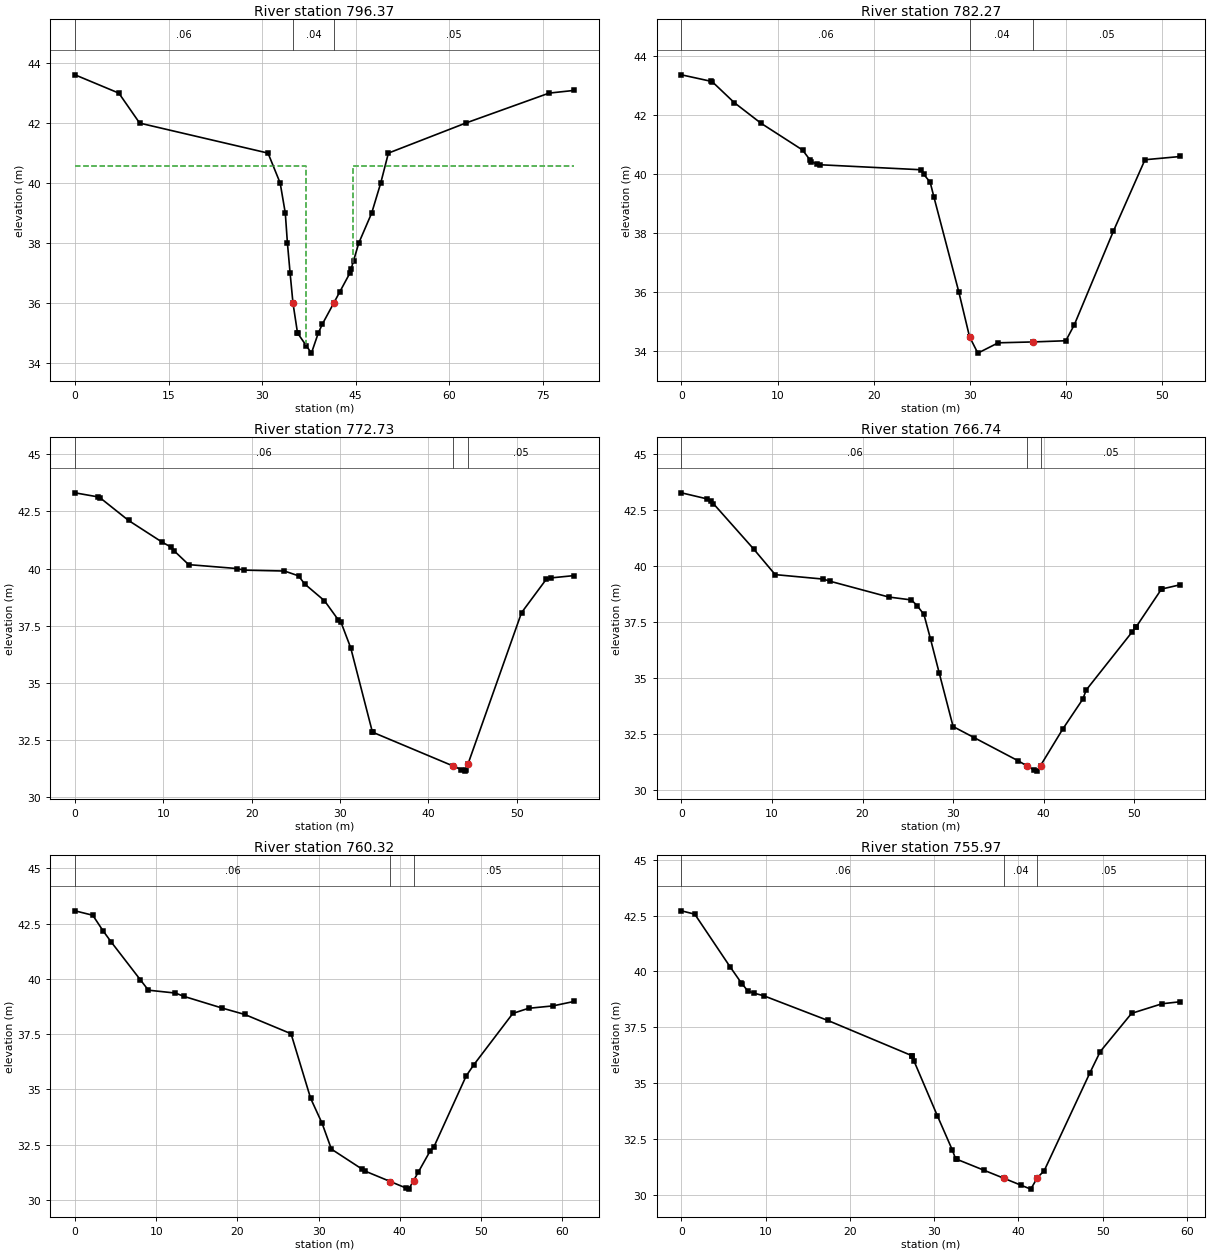
Type RM Length L Ch R = 1 ,796.37  ,12.75,14.1,16.38
Node Photo=..\..\..\Corner Brook\Windshield Survey\CB photos\Google\2118 DS.jpg
XS GIS Cut Line= 2
344606.2000732425423449.90393066344647.3718872075423381.31170654
#Sta/Elev= 27
       0   43.61    7.03      43   10.37      42   30.95      41    32.9      40
   33.72      39   34.06      38   34.49      37   34.95      36   35.67  35.014
   35.68      35   37.11   34.57   37.91   34.33   39.01      35   39.67    35.3
   41.49      36   42.44  36.367   44.08      37   44.26  37.127   44.66  37.408
    45.5      38   47.57      39   49.02      40   50.25      41   62.63      42
   76.01      43   80.01   43.09
#Mann= 3 , 0 , 0
       0     .06       0   34.95     .04       0   41.49     .05       0
#XS Ineff= 2 , 0
       0   37.05   40.56   44.57       0   40.56
Permanent Ineff=
       F       F
Bank Sta=34.95,41.49
XS Rating Curve= 0 ,0
Exp/Cntr=0.5,0.3

Type RM Length L Ch R = 1 ,782.27  ,8.97,9.53,9.31
XS GIS Cut Line= 4
 344608.363281255423447.75390625344615.467102051 5423437.3651123
344627.9425048835423431.82427979344649.0811157235423417.27990723
#Sta/Elev= 25
       0   43.36    3.08   43.14    3.22   43.12    5.48   42.42    8.26   41.72
   12.59   40.81    13.4   40.46   13.46   40.42   14.12   40.33   14.38   40.31
   24.92   40.14   25.18   39.99   25.86   39.72   26.24   39.23   28.83   36.01
   29.96   34.47   29.98   34.46   30.82   33.92   32.94   34.27   36.58    34.3
   39.97   34.34   40.85   34.88   44.92   38.06    48.2   40.48   51.89   40.59
#Mann= 3 , 0 , 0
       0     .06       0   29.98     .04       0   36.58     .05       0
Bank Sta=29.98,36.58
XS Rating Curve= 0 ,0
Exp/Cntr=0.3,0.1

Type RM Length L Ch R = 1 ,772.73  ,5.73,5.99,6.14
XS GIS Cut Line= 5
344608.8828735355423447.75390625 344614.947326665423438.75030518
344622.0513305665423436.49932861 344631.234497075423440.30847168
 344654.798889165423424.72528076
#Sta/Elev= 28
       0   43.31    2.64   43.13    2.85   43.09    6.07    42.1    9.88   41.15
   10.86   40.94   11.26   40.76   12.87   40.17   18.31      40   19.11   39.93
   23.72   39.89   25.31   39.68   25.99   39.33   28.25   38.59   29.82   37.75
   30.09   37.68   31.22   36.53   33.68   32.84   33.71   32.84   42.78   31.37
   43.72   31.21   44.19   31.14   44.25   31.18   44.48  31.431   50.56   38.07
   53.38   39.54    53.9   39.59    56.5   39.69
#Mann= 3 , 0 , 0
       0     .06       0   42.78     .04       0   44.48     .05       0
Bank Sta=42.78,44.48
XS Rating Curve= 0 ,0
Exp/Cntr=0.3,0.1

Type RM Length L Ch R = 1 ,766.74  ,6.37,6.42,6.54
XS GIS Cut Line= 6
 344609.576110845423449.13909912344616.6801147465423445.50311279
344631.581115723 5423445.8493042344636.6058959965423443.42529297
344655.1455078135423432.17071533344657.5712890635423427.84191895
#Sta/Elev= 30
       0   43.27    2.82      43    3.31   42.89    3.52   42.79    7.98   40.76
   10.35   39.62   15.66   39.42   16.45   39.32   22.89   38.62   25.39   38.49
   26.02   38.24   26.78   37.84   27.51   36.74   28.46   35.24      30   32.84
    32.3   32.35   37.19   31.31   38.19  31.075   38.89   30.91   39.28   30.85
   39.66    31.1   42.13   32.74   44.32   34.06    44.7   34.47   49.79   37.07
   50.15   37.26   50.22   37.29   52.99   38.96   53.08   38.98   55.11   39.17
#Mann= 3 , 0 , 0
       0     .06       0   38.19     .04       0   39.66     .05       0
Bank Sta=38.19,39.66
XS Rating Curve= 0 ,0
Exp/Cntr=0.3,0.1

Type RM Length L Ch R = 1 ,760.32  ,4.45,4.35,4.33
XS GIS Cut Line= 6
344610.9622802735423450.17810059344618.5858764655423447.58087158
344628.6354980475423448.27349854     344640.93755423447.92712402
 344657.224670415423438.75030518344663.2891235355423428.01507568
#Sta/Elev= 29
       0   43.08    2.19   42.88    3.43   42.19    4.42   41.69    8.05   39.96
    9.04   39.49   12.37   39.36   13.42   39.21   18.13   38.68   20.92   38.39
   26.61   37.52   29.02    34.6   30.43   33.47   31.58    32.3   35.38   31.39
    35.7   31.31   38.83  30.835   40.77   30.54   41.11   30.49    41.7  30.877
   42.28  31.257   43.72    32.2   44.18   32.38   48.18   35.61   49.13   36.12
   53.93   38.44   55.86   38.67   58.88   38.78   61.46   38.98
#Mann= 3 , 0 , 0
       0     .06       0   38.83     .04       0    41.7     .05       0
Bank Sta=38.83,41.7
XS Rating Curve= 0 ,0
Exp/Cntr=0.3,0.1

Type RM Length L Ch R = 1 ,755.97  ,6.93,6.28,5.82
XS GIS Cut Line= 6
344613.3878784185423453.64111328344618.9324951175423452.08270264
344630.5415039065423451.39007568344643.5364990235423451.39007568
344659.3038940435423442.55950928344663.6356811525423432.69012451
#Sta/Elev= 27
       0   42.71    1.58   42.56    5.76   40.21    7.11   39.48    7.19   39.45
    7.87   39.12    8.64   39.02    9.75   38.91   17.39    37.8   27.32   36.23
   27.35   36.19   27.62   35.97   30.38   33.53   32.14   32.01   32.53   31.62
   32.66   31.59   35.88    31.1   38.27  30.736   40.34   30.42   41.46   30.25
   42.26   30.77   43.05   31.07   48.46   35.44   49.71   36.41   53.43   38.12
   57.05   38.55   59.23   38.64
#Mann= 3 , 0 , 0
       0     .06       0   38.27     .04       0   42.26     .05       0
Bank Sta=38.27,42.26
XS Rating Curve= 0 ,0
Exp/Cntr=0.3,0.1

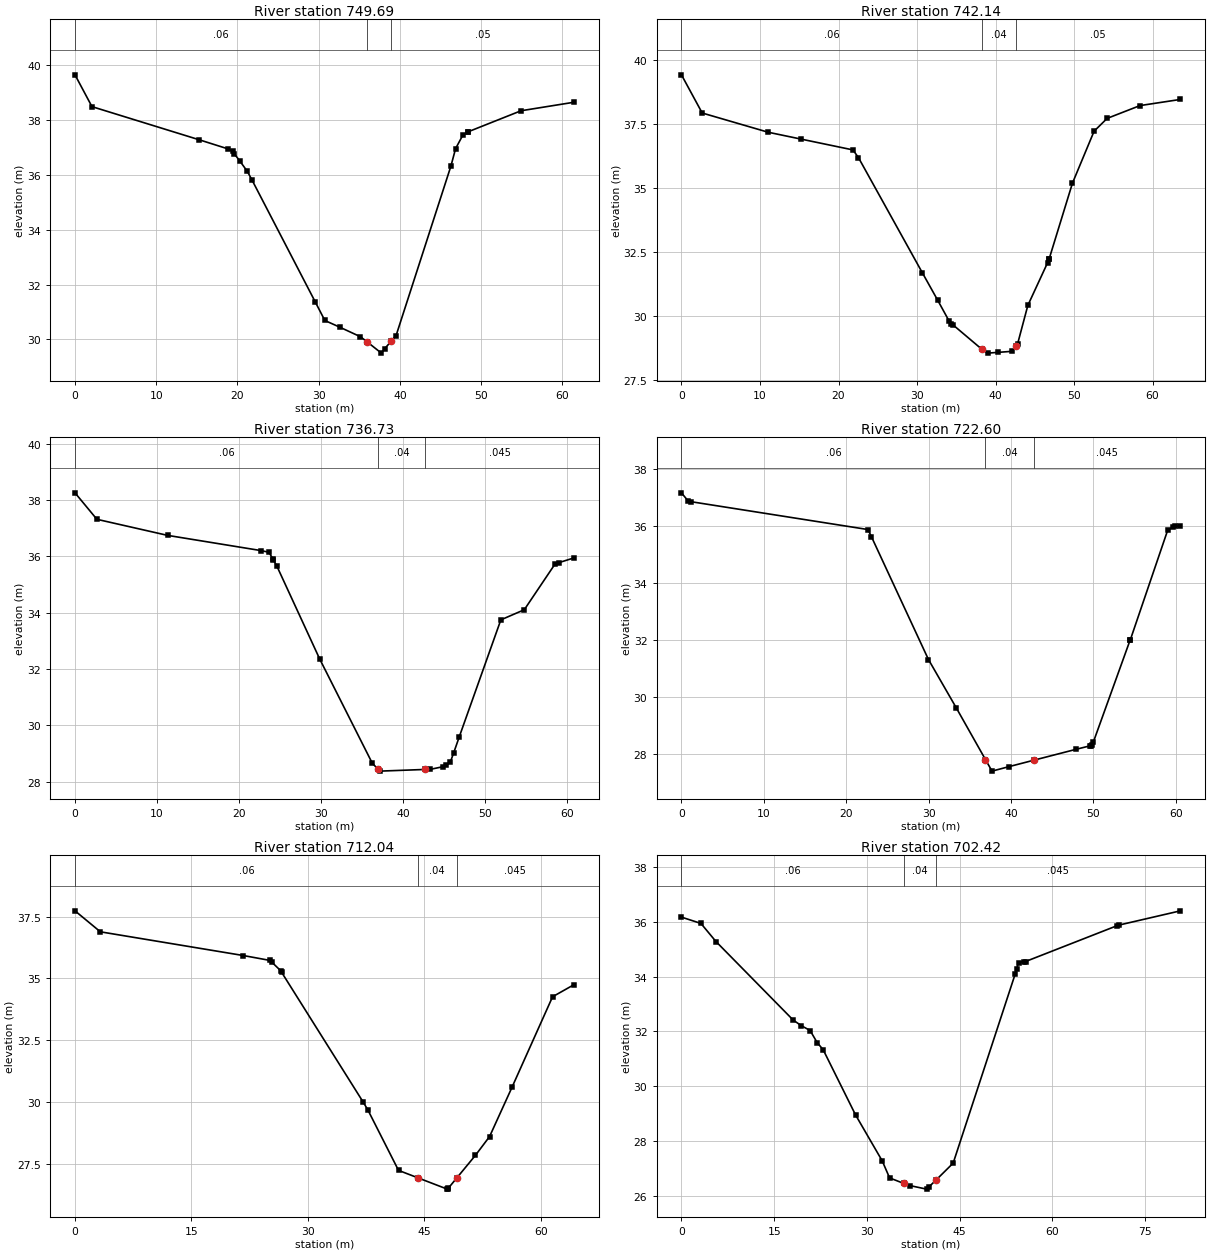
Type RM Length L Ch R = 1 ,749.69  ,6.48,7.55,8.4
XS GIS Cut Line= 6
344622.0639038095423457.50012207344637.3115234385423458.88531494
344643.2026977545423459.40472412344650.4799194345423455.24908447
344665.7274780275423444.34069824344667.4600830085423431.35467529
#Sta/Elev= 25
       0   39.65    2.09   38.49   15.31   37.28   18.83   36.95   19.51   36.86
   19.62   36.77   20.34   36.49   21.22   36.13   21.77   35.83    29.6   31.36
   30.77   30.69   32.58   30.45   35.14    30.1   35.94   29.92   37.73    29.5
   38.13   29.66   38.92  29.929   39.54   30.14   46.29   36.32   46.87   36.96
   47.76   37.45   48.35   37.56   48.39   37.57   54.93   38.34   61.45   38.65
#Mann= 3 , 0 , 0
       0     .06       0   35.94     .04       0   38.92     .05       0
Bank Sta=35.94,38.92
XS Rating Curve= 0 ,0
Exp/Cntr=0.3,0.1

Type RM Length L Ch R = 1 ,742.14  ,6.02,5.42,4.95
XS GIS Cut Line= 6
344624.4896850595423463.56030273344639.7373046885423464.07971191
344647.0145263675423464.25292969344664.6879272465423454.72967529
344667.1135253915423451.26672363344670.0590820315423434.81750488
#Sta/Elev= 26
       0   39.41    2.64   37.92   11.04   37.17   15.26    36.9   21.84   36.48
   22.54   36.18   30.67   31.69   32.64   30.61   34.09    29.8   34.39    29.7
   34.63   29.64   38.26    28.7   39.01   28.55   40.32   28.58   42.08   28.62
   42.61   28.81    42.8    28.9   44.11   30.41   46.63   32.08    46.8   32.21
   46.84   32.24   49.79   35.18   52.55   37.21   54.21   37.71    58.4   38.21
   63.55   38.45
#Mann= 3 , 0 , 0
       0     .06       0   38.26     .04       0   42.61     .05       0
Bank Sta=38.26,42.61
XS Rating Curve= 0 ,0
Exp/Cntr=0.3,0.1

Type RM Length L Ch R = 1 ,736.73  ,13.29,14.13,15.08
XS GIS Cut Line= 4
344627.0886840825423470.83251953344638.3510742195423471.52508545
344656.1976928715423466.50372314344681.3214721685423448.32312012
#Sta/Elev= 24
       0   38.26    2.67   37.32   11.28   36.75   22.67   36.21   23.65   36.15
   24.11   35.92   24.18   35.88   24.61   35.66   29.82   32.37   36.23   28.67
   36.93   28.45   37.15   28.38   42.73   28.44   43.27   28.44   44.91   28.54
   45.28   28.58   45.76    28.7   46.16   29.02   46.83   29.58   51.92   33.75
   54.78   34.11   58.52   35.73   58.98   35.78   60.84   35.95
#Mann= 3 , 0 , 0
       0     .06       0   36.93     .04       0   42.73    .045       0
Bank Sta=36.93,42.73
XS Rating Curve= 0 ,0
Exp/Cntr=0.3,0.1

Type RM Length L Ch R = 1 ,722.60  ,9.42,10.56,11.32
XS GIS Cut Line= 4
344629.6876831055423479.31671143344652.7322998055423478.62408447
344662.9550781255423477.23907471344686.8660888675423464.25292969
#Sta/Elev= 22
       0   37.17     .82   36.88    1.12   36.86   22.64   35.88   23.06   35.63
   29.99   31.31   33.37   29.61   36.91  27.795    37.7   27.39   39.79   27.55
   42.78  27.774   47.95   28.16   49.62   28.28   49.74   28.29   49.88    28.3
   49.99    28.4   54.46   31.99    54.5   32.01   59.02   35.85   59.69   35.98
   59.87   35.99   60.58   36.01
#Mann= 3 , 0 , 0
       0     .06       0   36.91     .04       0   42.78    .045       0
Bank Sta=36.91,42.78
XS Rating Curve= 0 ,0
Exp/Cntr=0.3,0.1

Type RM Length L Ch R = 1 ,712.04  ,12.16,9.62,7.82
XS GIS Cut Line= 5
344628.3016967775423483.12609863344653.4254760745423486.24267578
344665.2077026375423485.89648438344678.8958740235423481.22149658
344688.7720947275423473.25653076
#Sta/Elev= 20
       0   37.74    3.27   36.89   21.67   35.93   25.14   35.73   25.32   35.67
   26.47   35.32   26.61   35.25    37.1      30   37.71   29.68   41.66   27.23
   44.14   26.93   47.94   26.47      48   26.47   48.08   26.51   49.16   26.92
   51.57   27.84   53.39    28.6   56.27   30.59    61.5   34.26   64.26   34.75
#Mann= 3 , 0 , 0
       0     .06       0   44.14     .04       0   49.16    .045       0
Bank Sta=44.14,49.16
XS Rating Curve= 0 ,0
Exp/Cntr=0.3,0.1

Type RM Length L Ch R = 1 ,702.42  ,9.35,10.74,11.82
XS GIS Cut Line= 4
344644.978088379 5423506.1138916344664.2185058595423503.77630615
344691.3189086915423480.11047363344701.4177246095423456.81347656
#Sta/Elev= 25
       0   36.17    3.15   35.94    5.58   35.28   18.09   32.41   19.38   32.21
   20.82   32.03   21.96   31.59   22.93   31.33   28.17   28.95   32.49   27.27
   33.68   26.65   35.95   26.45   36.96   26.37   39.66   26.24   39.99   26.31
   41.19   26.57   43.97   27.19      54   34.09   54.22   34.26   54.55   34.51
   55.36   34.55   55.69   34.55   70.52   35.86    70.8   35.88   80.75    36.4
#Mann= 3 , 0 , 0
       0     .06       0   35.95     .04       0   41.19    .045       0
Bank Sta=35.95,41.19
XS Rating Curve= 0 ,0
Exp/Cntr=0.3,0.1

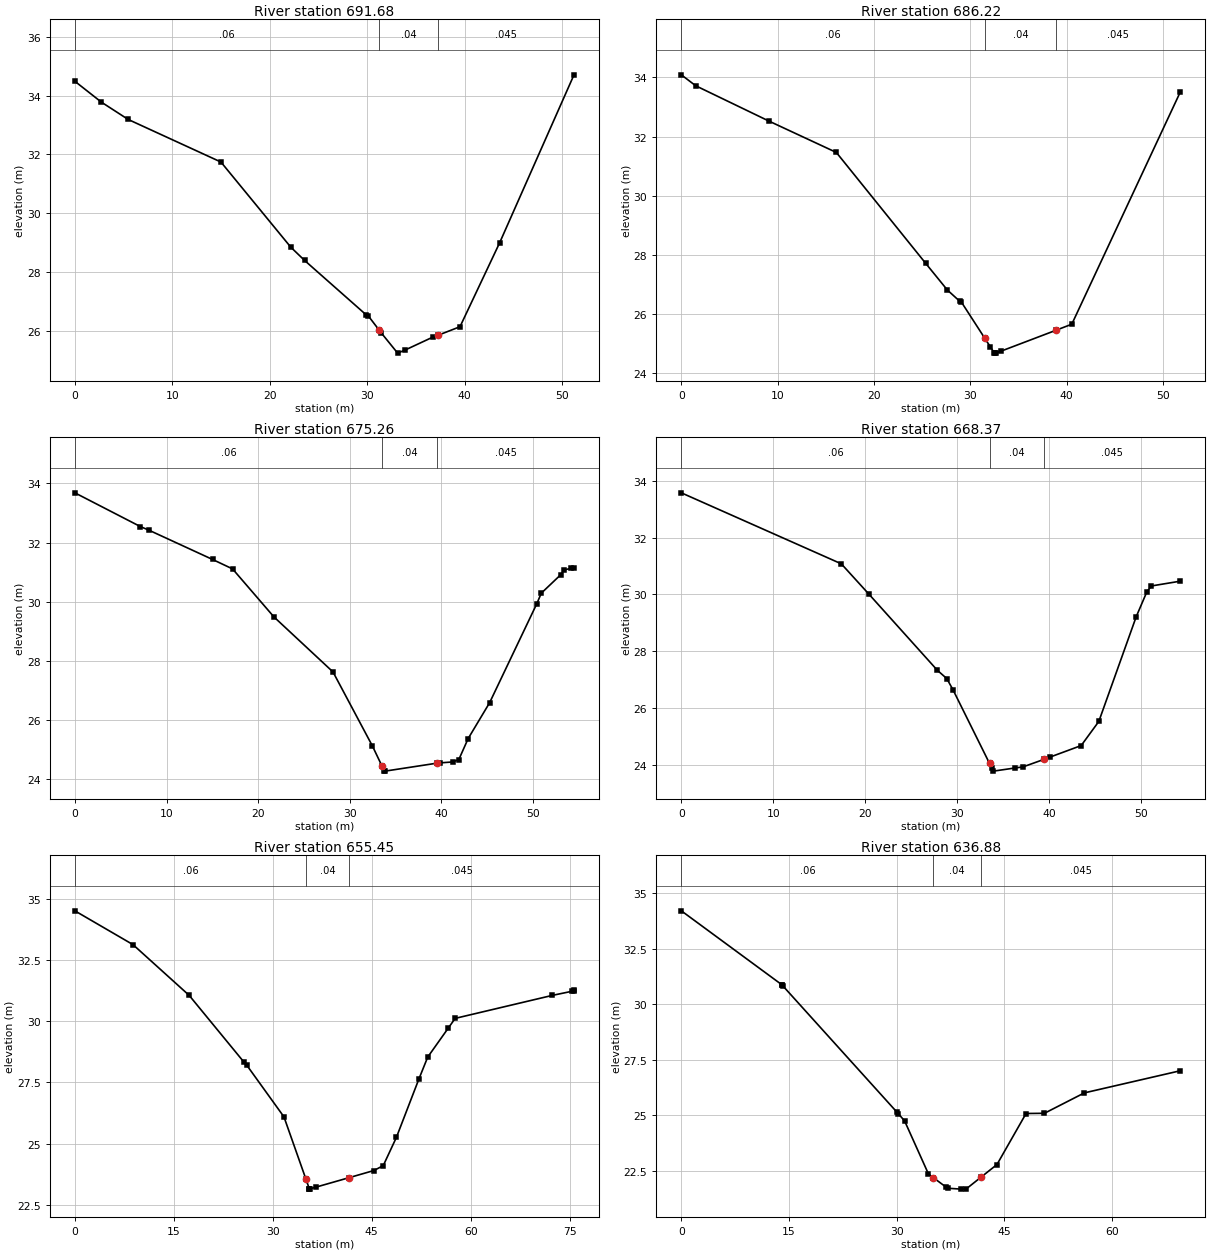
Type RM Length L Ch R = 1 ,691.68  ,5.19,5.46,5.76
XS GIS Cut Line= 3
344653.627319336 5423511.9519043344676.1520996095423505.02587891
344699.8898925785423490.82788086
#Sta/Elev= 17
       0   34.49    2.72   33.78    5.47   33.19   14.99   31.74   22.16   28.84
   23.57   28.39   29.88   26.54   30.09   26.51   31.24   26.01   31.47   25.91
   33.13   25.23   33.86   25.33   36.77   25.78   37.29   25.84   39.53   26.13
    43.6   28.99   51.23   34.71
#Mann= 3 , 0 , 0
       0     .06       0   31.24     .04       0   37.29    .045       0
Bank Sta=31.24,37.29
XS Rating Curve= 0 ,0
Exp/Cntr=0.3,0.1

Type RM Length L Ch R = 1 ,686.22  ,10.65,10.96,11.43
XS GIS Cut Line= 3
344655.3601074225423517.49267578344679.2708740235423509.00848389
344702.4888916025423496.36853027
#Sta/Elev= 17
       0   34.09    1.49   33.72    9.11   32.52   16.09   31.46   25.37    27.7
   27.61    26.8   28.89   26.42   29.07   26.39   31.47  25.178   32.08   24.87
   32.49   24.66   32.57   24.66   32.66   24.66   33.13   24.72   38.93   25.44
   40.53   25.64   51.81   33.52
#Mann= 3 , 0 , 0
       0     .06       0   31.47     .04       0   38.93    .045       0
Bank Sta=31.47,38.93
XS Rating Curve= 0 ,0
Exp/Cntr=0.3,0.1

Type RM Length L Ch R = 1 ,675.26  ,6.79,6.88,6.51
XS GIS Cut Line= 3
344658.9987182625423525.97692871344673.726501465 5423523.0335083
344709.4196777345423506.23809814
#Sta/Elev= 23
       0   33.68    7.15   32.54    8.07   32.42   15.02   31.43   17.21   31.11
   21.72   29.49   28.17   27.63   32.47   25.13    33.5  24.462   33.78   24.28
   33.85   24.28   39.54   24.55    39.9   24.56   41.24   24.59    41.9   24.67
   42.92   25.38   45.26   26.59   50.42   29.94    50.9   30.29   53.01   30.91
   53.42   31.08   54.18   31.13   54.47   31.14
#Mann= 3 , 0 , 0
       0     .06       0    33.5     .04       0   39.54    .045       0
Bank Sta=33.5,39.54
XS Rating Curve= 0 ,0
Exp/Cntr=0.3,0.1

Type RM Length L Ch R = 1 ,668.37  ,13.39,12.92,12.63
XS GIS Cut Line= 4
344661.4244995125423531.86407471344681.176879883 5423526.8427124
344699.1967163095423518.70471191344711.3255004885423511.43249512
#Sta/Elev= 19
       0   33.58    17.4   31.08   20.38   30.02   27.85   27.33   28.87   27.04
   29.54   26.65   33.52  24.053   33.77   23.89   33.94   23.78   36.28   23.89
   37.17   23.93   39.41   24.19   40.15   24.28   43.49   24.68   45.41   25.53
   49.48   29.22   50.63   30.09   51.12    30.3   54.29   30.47
#Mann= 3 , 0 , 0
       0     .06       0   33.52     .04       0   39.41    .045       0
Bank Sta=33.52,39.41
XS Rating Curve= 0 ,0
Exp/Cntr=0.3,0.1

Type RM Length L Ch R = 1 ,655.45  ,16.35,18.57,21.74
XS GIS Cut Line= 4
344664.9114990235423543.94927979344689.9675292975423538.37432861
344712.8703002935423525.14770508344724.0916748055423504.46069336
#Sta/Elev= 23
       0    34.5    8.81   33.12   17.32   31.05   25.67   28.31   26.05    28.2
   31.69   26.09   35.02  23.547   35.54   23.15   35.54   23.14   35.58   23.15
   36.52   23.22   41.59   23.61   45.33    23.9   46.74    24.1   48.73   25.25
   52.12   27.62   53.48   28.53   56.56    29.7   57.64   30.11   72.39   31.05
   75.42   31.22   75.61   31.24   75.65   31.25
#Mann= 3 , 0 , 0
       0     .06       0   35.02     .04       0   41.59    .045       0
Bank Sta=35.02,41.59
XS Rating Curve= 0 ,0
Exp/Cntr=0.3,0.1

Type RM Length L Ch R = 1 ,636.88  ,17.22,17.82,17.39
XS GIS Cut Line= 5
      344668.528     5423552.642      344679.042     5423551.849
      344716.376      5423548.58      344719.838     5423541.659
       344717.77     5423528.044
#Sta/Elev= 19
       0   34.21   14.03   30.87   14.04   30.86   14.13   30.83   29.98   25.15
   30.24   25.06   31.11   24.73   34.43   22.34   35.11  22.176   36.84   21.76
   37.08    21.7   39.02   21.66   39.69   21.67   41.75    22.2   43.97   22.77
   48.02   25.07   50.58   25.08   56.14      26   69.53      27
#Mann= 3 , 0 , 0
       0     .06       0   35.11     .04       0   41.75    .045       0
Bank Sta=35.11,41.75
XS Rating Curve= 0 ,0
Exp/Cntr=0.3,0.1

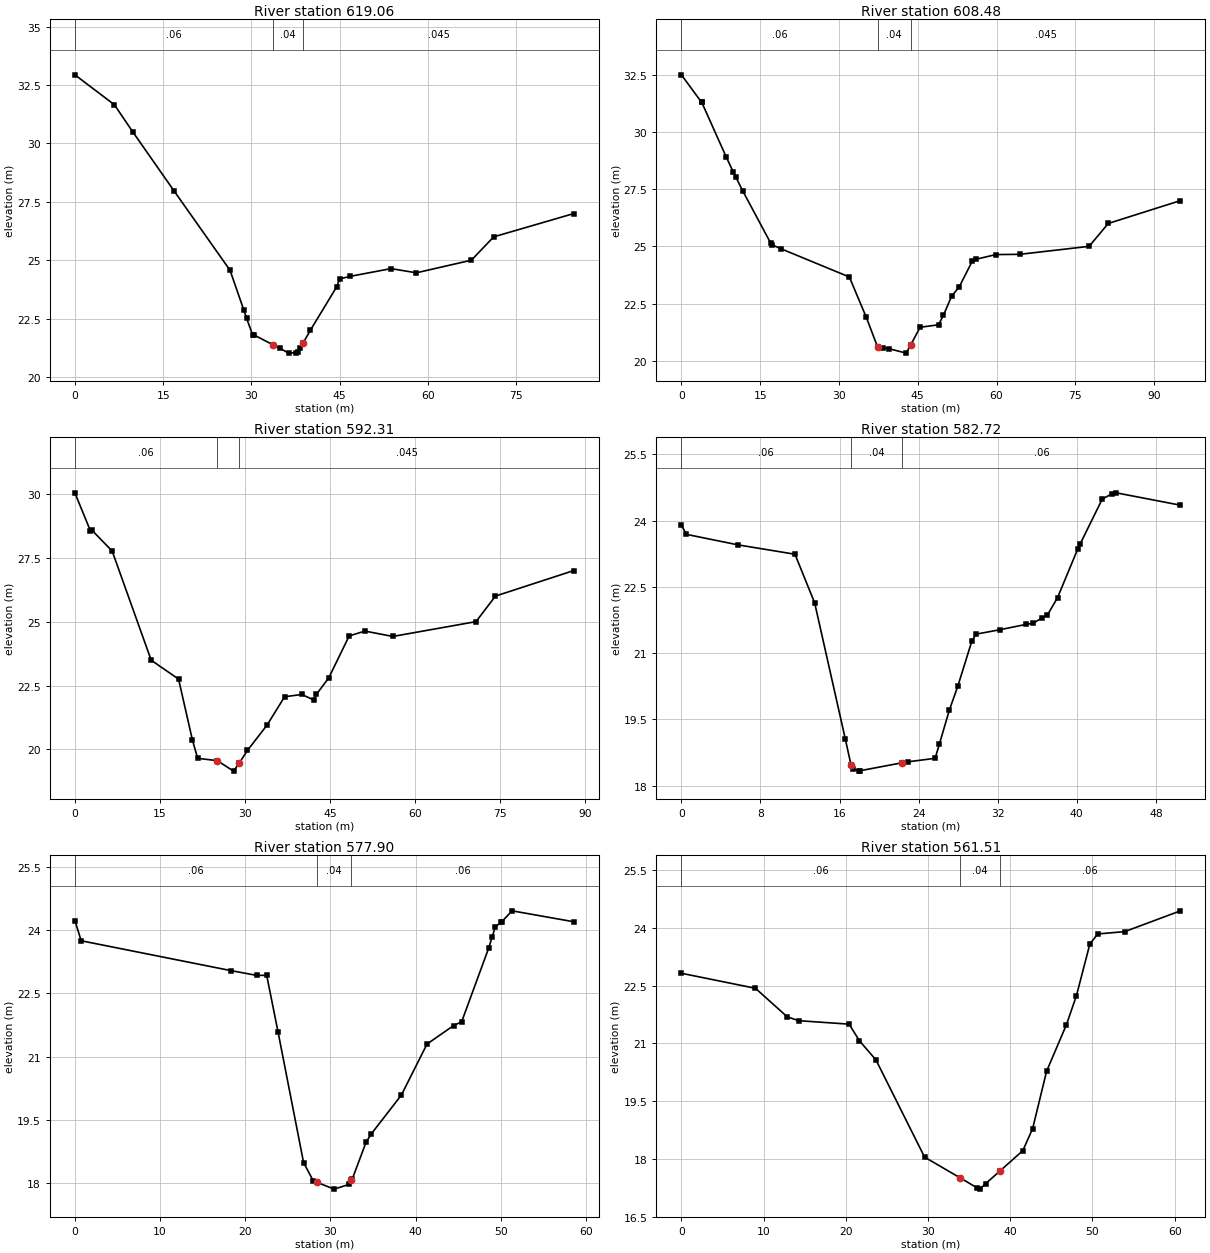
Type RM Length L Ch R = 1 ,619.06  ,13.53,10.59,7.5
XS GIS Cut Line= 6
      344672.687     5423565.109      344707.514     5423567.186
      344719.296     5423565.455      344721.895     5423554.547
      344720.211     5423541.042      344718.217     5423528.029
#Sta/Elev= 25
       0   32.94    6.71   31.66    9.83    30.5    16.9   27.95   26.36   24.57
   28.71   22.86   29.18   22.51   30.19   21.81   30.49   21.79   33.64   21.38
   34.89   21.22   36.33   21.02   37.57   21.04   37.93   21.07   38.28   21.23
   38.83  21.475   40.01      22   44.46   23.85      45    24.2    46.8   24.31
   53.72   24.64   58.01   24.46   67.36      25   71.16      26   84.79      27
#Mann= 3 , 0 , 0
       0     .06       0   33.64     .04       0   38.83    .045       0
Bank Sta=33.64,38.83
XS Rating Curve= 0 ,0
Exp/Cntr=0.3,0.1

Type RM Length L Ch R = 1 ,608.48  ,19.38,16.17,7
XS GIS Cut Line= 6
      344677.992     5423599.323      344719.493     5423571.641
      344724.268     5423557.956      344721.134     5423544.957
      344720.396     5423540.345       344718.66     5423527.883
#Sta/Elev= 29
       0    32.5    3.84    31.3    3.87    31.3    8.51   28.92    9.86   28.26
   10.31   28.05   11.64   27.44   17.02   25.13   17.23   25.07      19   24.89
   31.97   23.66   35.17   21.91   37.38   20.58   38.42   20.55   39.59   20.52
   42.79   20.33   43.65   20.69   45.44   21.46   48.95   21.57   49.89   21.99
   51.44   22.82   52.89   23.23   55.39   24.36      56   24.43   59.87   24.64
   64.38   24.65   77.62      25   81.25      26      95      27
#Mann= 3 , 0 , 0
       0     .06       0   37.38     .04       0   43.65    .045       0
Bank Sta=37.38,43.65
XS Rating Curve= 0 ,0
Exp/Cntr=0.3,0.1

Type RM Length L Ch R = 1 ,592.31  ,13.08,9.58,7.18
XS GIS Cut Line= 6
       344709.42     5423609.608      344720.336     5423595.929
      344723.801     5423583.462      344720.509     5423574.459
      344725.014     5423559.048      344719.064     5423527.701
#Sta/Elev= 24
       0   30.04    2.73   28.56    3.04   28.57    6.58   27.76   13.46   23.49
   18.29   22.75   20.72   20.38   21.66   19.65   25.12   19.56   27.98   19.15
   29.03  19.476   30.44   19.96   33.89   20.95   36.99   22.06   40.02   22.15
   42.17   21.93   42.59   22.15   44.78    22.8   48.38   24.44   51.15   24.63
   56.08   24.42   70.75      25   74.18      26   88.02      27
#Mann= 3 , 0 , 0
       0     .06       0   25.12     .04       0   29.03    .045       0
Bank Sta=25.12,29.03
XS Rating Curve= 0 ,0
Exp/Cntr=0.3,0.1

Type RM Length L Ch R = 1 ,582.72  ,5.75,4.83,4.18
XS GIS Cut Line= 6
344729.5186767585423605.62530518344734.1968994145423592.98547363
344728.8255004885423581.55767822344723.9741210945423572.38067627
344723.2808837895423568.57147217344726.2265014655423558.87530518
#Sta/Elev= 30
       0    23.9      .5   23.69    5.77   23.45   11.49   23.24   13.48   22.14
   16.59   19.05   17.16   18.47    17.4   18.38   17.97   18.33    18.1   18.34
   22.35   18.52   22.89   18.54   25.67   18.62   26.11   18.95   27.12   19.72
   27.96   20.25   29.38   21.27    29.8   21.43    32.2   21.53   34.84   21.65
   35.61   21.68   36.49    21.8   37.02   21.86   38.06   22.26    40.1   23.36
   40.36   23.48   42.58   24.49   43.58   24.61   43.99   24.63   50.49   24.35
#Mann= 3 , 0 , 0
       0     .06       0   17.16     .04       0   22.35     .06       0
Bank Sta=17.16,22.35
XS Rating Curve= 0 ,0
Exp/Cntr=0.3,0.1

Type RM Length L Ch R = 1 ,577.90  ,17.27,16.39,15.08
XS GIS Cut Line= 5
344734.3701171885423610.30029297344741.8206787115423593.50488281
344732.4641113285423579.99932861344726.9196777345423565.80108643
344727.9592895515423557.31689453
#Sta/Elev= 26
       0   24.23     .74   23.75   18.37   23.04   21.33   22.93   22.52   22.93
   23.85   21.59   26.85   18.49   27.98   18.06   28.43   18.02   30.44   17.86
   32.15   17.97   32.47   18.07   32.55   18.09   34.18   18.97    34.8   19.17
   38.33   20.09   41.34    21.3   44.47   21.74   45.41   21.83   48.57   23.57
   48.99   23.84   49.36   24.08   50.05   24.19   50.11    24.2   51.33   24.46
   58.59    24.2
#Mann= 3 , 0 , 0
       0     .06       0   28.43     .04       0   32.47     .06       0
Bank Sta=28.43,32.47
XS Rating Curve= 0 ,0
Exp/Cntr=0.3,0.1

Type RM Length L Ch R = 1 ,561.51  ,6.39,8.44,10.26
XS GIS Cut Line= 3
344761.5350952155423601.67852783344762.1672973635423588.82788086
344729.5651245125423553.82312012
#Sta/Elev= 22
       0   22.82    9.01   22.43   12.87   21.69   14.26   21.59    20.4    21.5
   21.65   21.07   23.67   20.57   29.58   18.05   33.84   17.52   35.99   17.25
   36.28   17.22   36.99   17.36   38.69   17.68   41.53   18.22   42.72   18.79
   44.42   20.28   46.82   21.48   48.05   22.24   49.68   23.58   50.64   23.84
   53.91    23.9    60.7   24.44
#Mann= 3 , 0 , 0
       0     .06       0   33.84     .04       0   38.69     .06       0
Bank Sta=33.84,38.69
XS Rating Curve= 0 ,0
Exp/Cntr=0.3,0.1

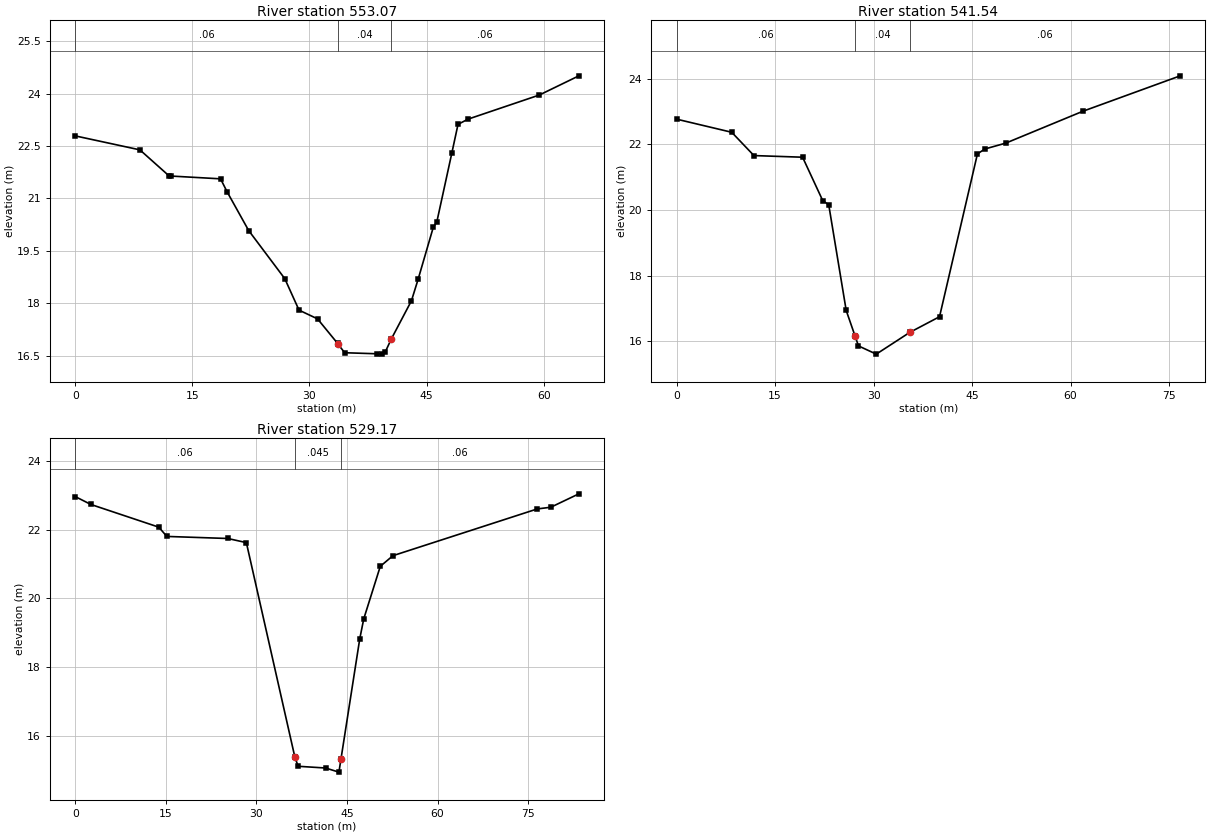
Type RM Length L Ch R = 1 ,553.07  ,8.06,11.53,13.46
XS GIS Cut Line= 6
344761.9196777345423601.29669189344763.6522827155423589.17608643
344761.5731201175423582.25030518 344754.642517095423569.95672607
344748.2315063485423556.79748535344733.6771240235423549.52508545
#Sta/Elev= 26
       0   22.79    8.28   22.39   12.04   21.64   12.24   21.64   18.61   21.56
   19.47   21.18   22.21   20.08   26.84    18.7   28.66    17.8   31.03   17.55
   33.59   16.85    33.6   16.84   34.51   16.58   38.61   16.55   39.25   16.54
   39.72   16.61   40.47   16.97   43.06   18.07   43.92   18.69   45.85   20.17
   46.31   20.33   48.23    22.3   49.02   23.12   50.31   23.27   59.43   23.96
    64.5   24.51
#Mann= 3 , 0 , 0
       0     .06       0    33.6     .04       0   40.47     .06       0
Bank Sta=33.6,40.47
XS Rating Curve= 0 ,0
Exp/Cntr=0.3,0.1

Type RM Length L Ch R = 1 ,541.54  ,10.36,12.37,14.02
XS GIS Cut Line= 6
344762.612670898 5423601.6428833 344766.771301275423579.99932861
344763.3059082035423563.03088379344765.7316894535423555.58532715
344758.1079101565423549.69830322344738.7019042975423545.71588135
#Sta/Elev= 17
       0   22.77     8.4   22.37   11.78   21.66   19.19   21.61   22.25   20.29
   23.17   20.16   25.83   16.94   27.17  16.166    27.7   15.86   30.41   15.61
   35.49   16.27   40.04   16.75   45.81   21.71   46.93   21.86   50.13   22.04
   61.86   23.01   76.69   24.09
#Mann= 3 , 0 , 0
       0     .06       0   27.17     .04       0   35.49     .06       0
Bank Sta=27.17,35.49
XS Rating Curve= 0 ,0
Exp/Cntr=0.3,0.1

Type RM Length L Ch R = 1 ,529.17  ,14.76,14.64,14.39
XS GIS Cut Line= 6
344766.251281738 5423608.9151001344771.6226806645423598.69927979
344775.954284668 5423582.0770874344777.3405151375423559.04827881
344769.8900756845423541.21411133344758.4542846685423536.71228027
#Sta/Elev= 18
       0   22.96     2.6   22.73   13.84   22.07   15.17    21.8   25.26   21.74
   28.34   21.62   36.37   15.38   36.92   15.11   41.45   15.06   43.67   14.94
   44.01  15.322   47.12   18.82   47.78    19.4   50.52   20.93   52.62   21.24
   76.51    22.6   78.76   22.65   83.41   23.04
#Mann= 3 , 0 , 0
       0     .06       0   36.37    .045       0   44.01     .06       0
Bank Sta=36.37,44.01
XS Rating Curve= 0 ,0
Exp/Cntr=0.3,0.1