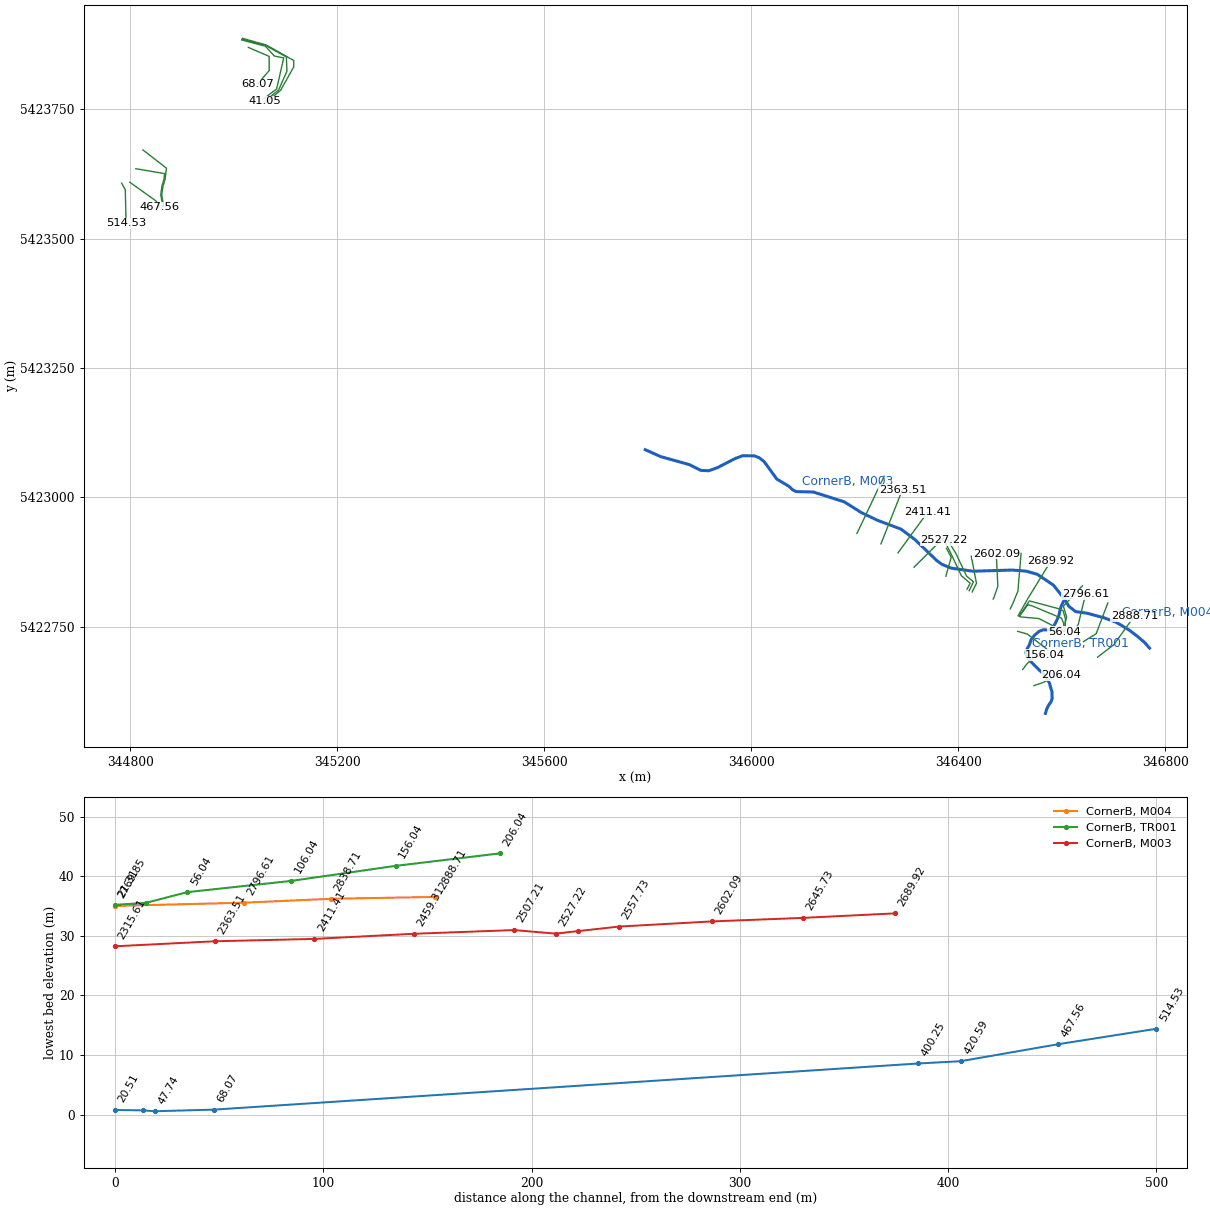
HEC-RAS study Corner_Brook2.prj: Corner_Brook2

--- Corner_Brook2.g01 (geometry) --- (continued)

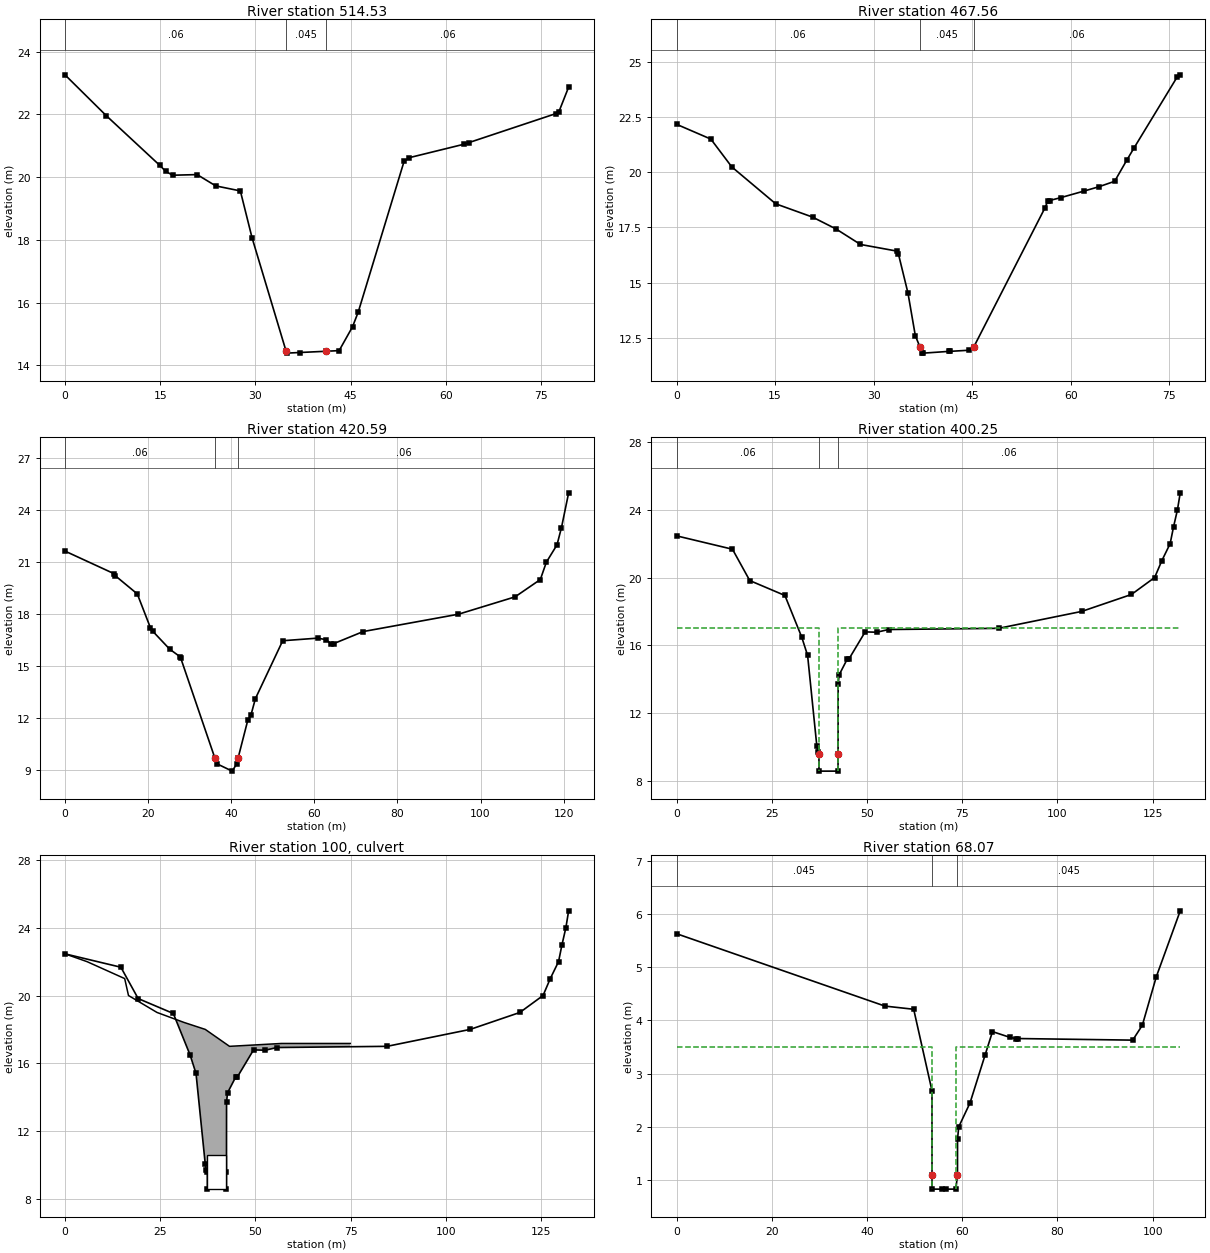
Type RM Length L Ch R = 1 ,514.53  ,42.9,46.97,53.68
XS GIS Cut Line= 3
344783.4863281255423607.42108154344790.5899047855423594.30987549
344792.0429077155423529.85552979
#Sta/Elev= 23
       0   23.26     6.5   21.96   14.91   20.38   15.85   20.19   16.95   20.06
   20.83   20.08   23.76   19.72   27.64   19.56   29.48   18.07   34.82  14.471
   34.94   14.39   37.02   14.41   41.21   14.45   43.21   14.47   45.32   15.23
   46.22    15.7   53.44    20.5   54.27   20.62   62.92   21.05   63.66    21.1
   77.31   22.02    77.8   22.06   79.38   22.87
#Mann= 3 , 0 , 0
       0     .06       0   34.82    .045       0   41.21     .06       0
Bank Sta=34.82,41.21
XS Rating Curve= 0 ,0
Exp/Cntr=0.3,0.1

Type RM Length L Ch R = 1 ,467.56  ,45.12,46.97,48.91
XS GIS Cut Line= 3
344799.2758789065423609.05450439344849.7756958015423573.01531982
344857.0006713875423560.30133057
#Sta/Elev= 29
       0   22.17    5.22    21.5    8.41   20.24   15.09   18.57   20.69   17.97
   24.28   17.43   27.99   16.73   33.52   16.43   33.76   16.31   35.22   14.53
   36.34    12.6   37.06  12.078   37.43   11.81   37.58   11.81    41.5   11.89
   41.59   11.89   44.46   11.94   45.22   12.08   56.06   18.38   56.53   18.71
   56.78   18.72   58.48   18.85   62.04   19.15   64.25   19.34   66.68   19.59
   68.53   20.55   69.65   21.11   76.21   24.32   76.66   24.41
#Mann= 3 , 0 , 0
       0     .06       0   37.06    .045       0   45.22     .06       0
Bank Sta=37.06,45.22
XS Rating Curve= 0 ,0
Exp/Cntr=0.3,0.1

Type RM Length L Ch R = 1 ,420.59  ,21.99,20.34,18.45
Node Photo=..\..\..\Corner Brook\Windshield Survey\CB photos\P1000693.JPG
XS GIS Cut Line= 6
      344810.865     5423635.201      344866.616     5423625.711
      344865.268     5423614.426      344861.458     5423602.301
      344859.051     5423584.465      344863.363      5423562.32
#Sta/Elev= 30
       0   21.64   11.87   20.33   12.15   20.21    17.4   19.17   20.54   17.23
   21.11   17.02   25.21   15.98   27.68   15.55   27.88   15.45    36.1   9.682
   36.59    9.37   40.23    8.95   41.28    9.35   41.68    9.73   43.97   11.87
   44.73   12.17   45.82   13.13   52.39   16.47   60.82   16.62   62.83   16.53
   64.03   16.29   64.63    16.3   71.77      17   94.68      18   108.3      19
  114.38      20  115.83      21  118.39      22  119.47      23  121.19      25
#Mann= 3 , 0 , 0
       0     .06       0    36.1    .045       0   41.68     .06       0
Bank Sta=36.1,41.68
XS Rating Curve= 0 ,0
Exp/Cntr=0.3,0.1

Type RM Length L Ch R = 1 ,400.25  ,338,338,338
Node Photo=..\..\..\Corner Brook\Windshield Survey\CB photos\P1000692.JPG
XS GIS Cut Line= 6
      344824.718     5423671.386      344870.066     5423636.305
      344867.443     5423614.785      344863.372     5423601.656
      344860.966     5423584.273      344864.667     5423562.637
#Sta/Elev= 28
       0   22.46   14.68   21.67   19.22   19.82   28.45   18.94   32.87   16.48
   34.41    15.4   36.82   10.08   37.05    9.72   37.39    9.56    37.4    8.57
    42.4    8.57   42.41    9.56   42.43    13.7   42.68   14.25   44.79   15.17
   45.21   15.17   49.52   16.79   52.58   16.77   55.66   16.93   84.57      17
  106.41      18  119.45      19  125.54      20  127.44      21  129.61      22
  130.51      23  131.53      24  132.26      25
#Mann= 3 , 0 , 0
       0     .06       0   37.39    .045       0   42.41     .06       0
#XS Ineff= 2 , 0
       0    37.4      17    42.4       0      17
Permanent Ineff=
       F       F
Bank Sta=37.39,42.41
XS Rating Curve= 0 ,0
Exp/Cntr=0.5,0.3

Type RM Length L Ch R = 2 ,100     ,,,
Node Photo=..\..\..\Corner Brook\Windshield Survey\CB photos\P1000645.JPG
BEGIN DESCRIPTION:
Valley Mall Culvert (Structure #2115)
END DESCRIPTION:
Bridge Culvert--1,0,-1,-1, 0
Deck Dist Width WeirC Skew NumUp NumDn MinLoCord MaxHiCord MaxSubmerge Is_Ogee
7,330,1.67,0, 10, 10, 17, , 0.98, 0, 0,0,,
       0    5.79   15.68   16.68   24.17   31.27   36.84   43.21   56.85   74.91
   22.46      22      21      20      19   18.41      18      17   17.17   17.17
                                                                                
       0     2.6   25.32   45.66   55.83   69.06   75.14    95.8   97.82  105.78
    5.63    5.63       5    4.15       4     3.7    3.63    3.63    3.91       6
                                                                                
BR Coef=-1 , 0 , 0 ,, 0 ,,,0.8,-1,,0,
WSPro=,,,, 1 ,,,, 0 ,,,, 0 ,,,,-1 ,-1 ,-1 , 0 , 0 , 0 , 0 , 0
Culvert=2,2,5,330,0.012,0.7,1,9,2,8.57,39.9,0.83,56.16,Culvert #1  , 0 ,6.7
Culvert Bottom n=0.012
BC Design=,, 0 ,, 0 ,,,,,,
BC Use User HTab Curves=0
BC User HTab FreeFlow(D)= 0

Type RM Length L Ch R = 1 ,68.07   ,27.5,28.4,28.6
Node Photo=..\..\..\Corner Brook\Windshield Survey\CB photos\P1000646.JPG
XS GIS Cut Line= 5
345028.2824707035423869.57769775345068.4484863285423852.24151611
345068.4484863285423831.15710449345068.4484863285423824.75372314
345046.0264892585423798.47808838
#Sta/Elev= 22
       0    5.63   43.75    4.27    49.8    4.21   53.64    2.68   53.65     1.1
   53.66     .83   55.65     .83   56.58     .83   58.66     .83      59     1.1
   59.01    1.77   59.26       2   61.63    2.45   64.83    3.36   66.35    3.79
   70.08    3.68   71.24    3.66   71.68    3.66    95.8    3.63   97.82    3.91
  100.75    4.82  105.78    6.06
#Mann= 3 , 0 , 0
       0    .045       0   53.65    .035       0      59    .045       0
#XS Ineff= 2 , 0
       0   53.66     3.5   58.66       0     3.5
Permanent Ineff=
       F       F
Bank Sta=53.65,59
XS Rating Curve= 0 ,0
Exp/Cntr=0.5,0.3

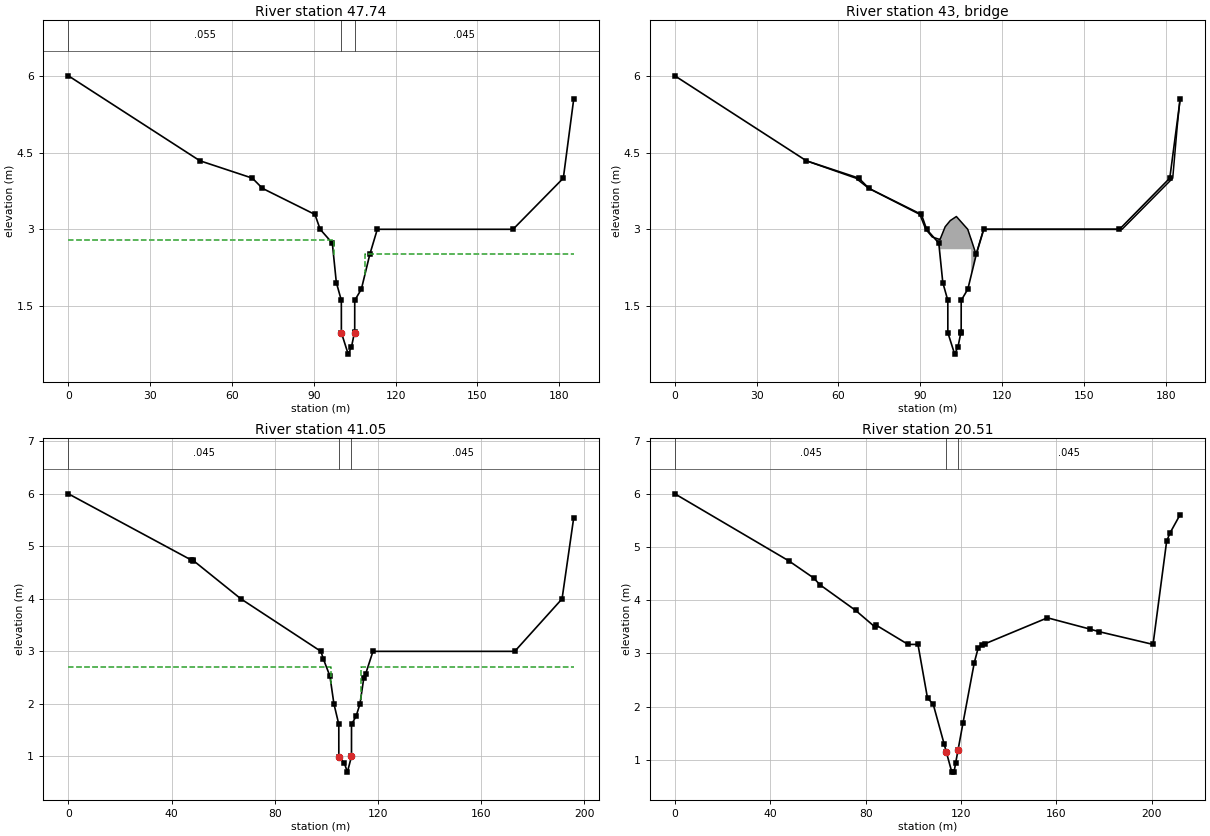
Type RM Length L Ch R = 1 ,47.74   ,5.2,5.5,5.7
Node Photo=..\..\..\Corner Brook\Windshield Survey\CB photos\P1000644.JPG
XS GIS Cut Line= 6
      345015.284        5423884.       345061.38     5423871.775
      345078.464     5423852.934      345096.641     5423849.292
      345082.981     5423789.378      345058.179     5423770.541
#Sta/Elev= 21
       0       6   48.19    4.34   67.45       4   71.17     3.8   90.41    3.29
   92.32       3   96.78    2.73   98.25    1.96  100.09    1.61   100.1     .98
   102.6     .56  103.81      .7  104.96       1  104.99     .98     105    1.61
  107.43    1.83  110.53    2.51  113.28       3  163.05       3   181.5       4
   185.3    5.54
#Mann= 3 , 0 , 0
       0    .055       0   100.1    .035       0  104.99    .045       0
#XS Ineff= 2 , 0
       0   97.23     2.8  108.67       0    2.51
Permanent Ineff=
       F       F
Bank Sta=100.1,104.99
XS Rating Curve= 0 ,0
Exp/Cntr=0.5,0.3

Type RM Length L Ch R = 3 ,43      ,,,
Node Photo=..\..\..\Corner Brook\Windshield Survey\CB photos\P1000643.JPG
BEGIN DESCRIPTION:
Pedestrian Bridge (Structure #2114)
END DESCRIPTION:
Bridge Culvert--1,0,-1,-1, 0
Deck Dist Width WeirC Skew NumUp NumDn MinLoCord MaxHiCord MaxSubmerge Is_Ogee
1.9,1.36,1.67,0, 23, 19, 2.51, , 0.98, 0, 0,0,,
   48.12   66.33    71.1   89.84   91.99   94.37   97.22   97.23   99.12  100.98
  103.23   107.4  108.66  108.67  110.45  113.21  119.18  124.55  143.04  163.99
  182.58  184.21  185.23
    4.34       4     3.8    3.29       3    2.85     2.8     2.8    3.05    3.17
    3.25       3     2.8     2.8    2.51       3       3       3       3       3
       4       5    5.54
                                                      .5    2.61    2.61    2.61
    2.61    2.61    2.61      .5
                        
   47.69   48.46   66.95   96.99  101.83  101.84  103.73  107.84  110.09  111.99
  113.28  113.29  115.07  118.09  130.09   152.1  173.15   191.5  196.01
    4.74    4.74       4       3     2.8     2.8    3.05    3.25    3.18       3
     2.8     2.8    3.01       3       3       3       3       4    5.54
                                      .5    2.61    2.61    2.61    2.61    2.61
    2.61      .5
BR Coef=-1 , 0 , 0 ,, 0 ,,,0.8,-1,,0,
WSPro=,,,, 1 ,,,, 0 ,,,, 0 ,,,,-1 ,-1 ,-1 , 0 , 0 , 0 , 0 , 0
BC Design=,, 0 ,, 0 ,,,,,,
BC Use User HTab Curves=0
BC User HTab FreeFlow(D)= 0

Type RM Length L Ch R = 1 ,41.05   ,7.95,13.7,10.9
Node Photo=..\..\..\Corner Brook\Windshield Survey\CB photos\P1000642.JPG
XS GIS Cut Line= 6
      345016.411     5423885.404      345062.372     5423872.953
      345101.758     5423851.043      345102.862     5423823.523
      345086.893     5423787.499       345060.13     5423765.541
#Sta/Elev= 23
       0       6   47.62    4.74   48.39    4.74   48.41    4.73   66.88       4
   97.91       3    98.9    2.85   101.4    2.53  102.96       2  104.85    1.61
  104.86     .98  106.94     .88  108.19      .7  109.77       1  109.78    1.61
  111.53    1.76  113.06       2  114.57     2.5  115.26    2.57   118.1       3
  173.08       3  191.43       4  195.94    5.54
#Mann= 3 , 0 , 0
       0    .045       0  104.86    .035       0  109.77    .045       0
#XS Ineff= 2 , 0
       0  101.83     2.7  113.29       0     2.7
Permanent Ineff=
       F       F
Bank Sta=104.86,109.77
XS Rating Curve= 0 ,0
Exp/Cntr=0.5,0.3

Type RM Length L Ch R = 1 ,20.51   ,17.7,20.51,20.51
XS GIS Cut Line= 6
      345017.135     5423887.085      345063.128     5423874.161
      345115.966     5423844.273      345115.966     5423831.778
      345090.668     5423786.743      345061.371     5423762.099
#Sta/Elev= 29
       0       6   47.77    4.74   58.14    4.42   60.85    4.29   75.76    3.81
   83.84     3.5   84.47    3.53   97.78    3.17  101.92    3.17  105.92    2.16
  108.29    2.05  112.89     1.3  113.84   1.144  116.11     .77  117.04     .77
  117.76     .95  118.75   1.192  120.79    1.69  125.55    2.83  127.16     3.1
  128.66    3.16  129.94    3.18  156.22    3.67  173.87    3.46  177.82    3.41
  200.49    3.17   206.2    5.11  207.56    5.26  211.86    5.61
#Mann= 3 , 0 , 0
       0    .045       0  113.84    .035       0  118.75    .045       0
Bank Sta=113.84,118.75
XS Rating Curve= 0 ,0
Exp/Cntr=0.3,0.1

River Reach=CornerB         ,M004
Reach XY= 11
346769.3977050785422708.92089844 346759.654479985422720.10650635
346747.0148925785422730.89752197346730.5571289065422743.53070068
346716.2058715825422752.34771729346704.0161132815422759.26751709
346682.6867065435422767.16333008346649.3760986335422776.24353027
346626.3350830085422779.66491699346613.3004760745422790.06109619
346606.1906738285422802.43127441

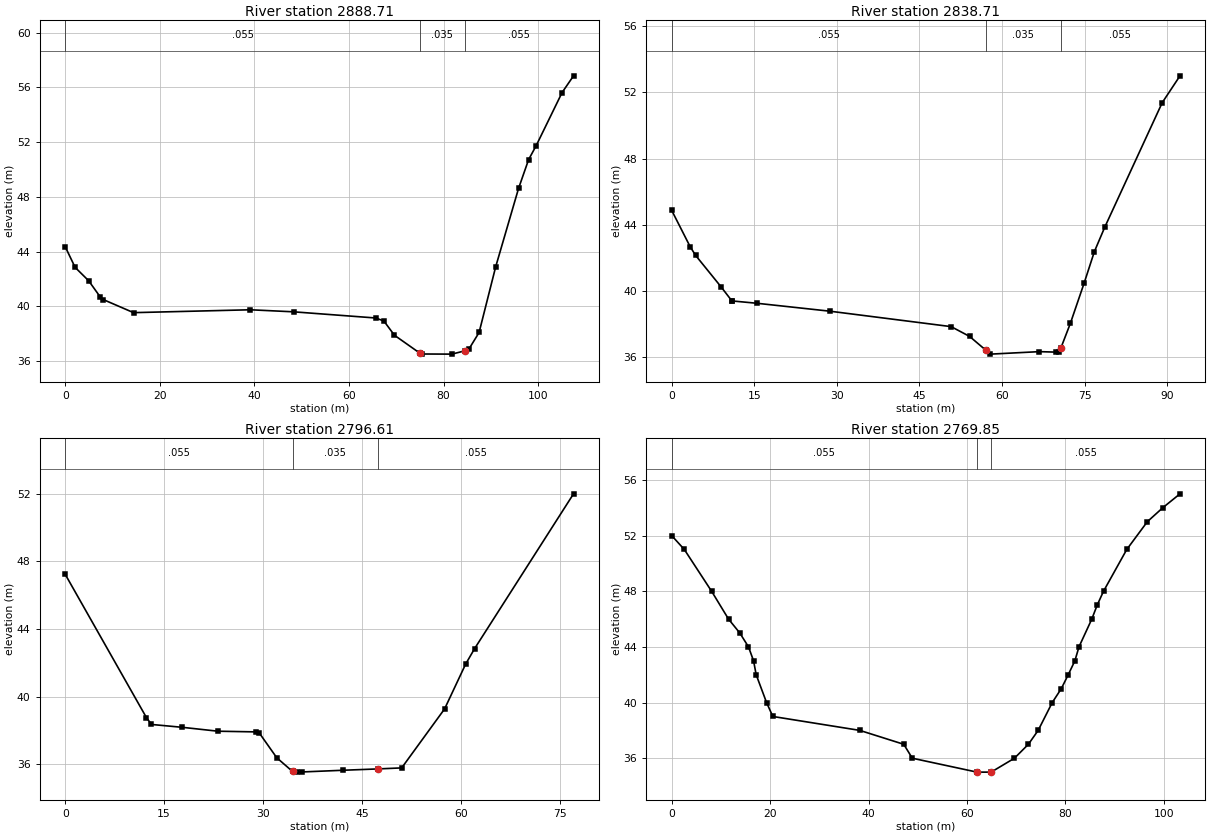
Type RM Length L Ch R = 1 ,2888.71 ,53.97,50,52.11
XS GIS Cut Line= 3
346669.0935058595422691.59967041346700.2282714845422715.34289551
 346740.142517095422770.79528809
#Sta/Elev= 23
       0   44.36    2.09   42.85    4.96   41.87     7.4   40.69    8.08   40.49
   14.45   39.54   39.16   39.75   48.31    39.6   65.65   39.15   67.38   38.93
   69.61   37.89   74.99   36.58   75.53   36.52   81.74   36.51   84.51   36.75
   85.36   36.88   87.51   38.09   91.02   42.89   95.85   48.61   97.98   50.72
   99.57   51.73  105.06   55.62  107.48   56.84
#Mann= 3 , 0 , 0
       0    .055       0   74.99    .035       0   84.51    .055       0
Bank Sta=74.99,84.51
XS Rating Curve= 0 ,0
Exp/Cntr=0.3,0.1

Type RM Length L Ch R = 1 ,2838.71 ,41.35,42.1,43.3
XS GIS Cut Line= 3
346641.8192749025422721.61871338346666.2966918955422736.76367188
346688.8312988285422796.17889404
#Sta/Elev= 22
       0   44.88    3.38   42.67    4.35   42.16    8.95   40.27   10.92   39.42
      11   39.41   15.49   39.27   28.78   38.79   50.76   37.86   54.11   37.27
   57.05   36.44    57.9    36.2    66.8   36.35   69.88   36.32    70.4   36.32
   70.66   36.54   72.42   38.06   74.94   40.51   76.78   42.39   78.66   43.86
    89.1   51.38   92.33      53
#Mann= 3 , 0 , 0
       0    .055       0   57.05    .035       0   70.66    .055       0
Bank Sta=57.05,70.66
XS Rating Curve= 0 ,0
Exp/Cntr=0.3,0.1

Type RM Length L Ch R = 1 ,2796.61 ,68.67,61.76,53.15
XS GIS Cut Line= 3
346623.3356933595422739.63427734346631.9049072275422755.19750977
346645.7158813485422812.87988281
#Sta/Elev= 18
       0   47.24   12.31   38.77   13.08   38.36   17.77   38.19   23.16   37.96
   28.87   37.92   29.42   37.86   32.08   36.39   34.47   35.58   35.08   35.54
   35.92   35.55    42.1   35.65   47.44   35.73   51.02   35.79   57.53   39.28
   60.72   41.93   62.07   42.84   77.08      52
#Mann= 3 , 0 , 0
       0    .055       0   34.47    .035       0   47.44    .055       0
Bank Sta=34.47,47.44
XS Rating Curve= 0 ,0
Exp/Cntr=0.3,0.1

Type RM Length L Ch R = 1 ,2769.85 ,72.21,71.38,82.76
XS GIS Cut Line= 5
       346606.19     5422741.889      346606.461     5422757.442
      346609.303     5422769.343      346602.942     5422789.899
      346639.752     5422829.388
#Sta/Elev= 30
       0      52    2.57      51    8.11      48   11.55      46   13.84      45
   15.61      44   16.64      43   17.17      42   19.28      40   20.55      39
   38.22      38   47.16      37   48.89      36   62.05      35   64.91      35
   69.65      36   72.48      37   74.47      38   77.33      40   79.17      41
   80.58      42   81.93      43   82.76      44   85.37      46   86.46      47
   87.75      48   92.47      51   96.66      53   99.79      54  103.29      55
#Mann= 3 , 0 , 0
       0    .055       0   62.05    .035       0   64.91    .055       0
Bank Sta=62.05,64.91
XS Rating Curve= 0 ,0
Exp/Cntr=0.3,0.1

River Reach=CornerB         ,TR001
Reach XY= 30
346568.2838745125422582.88391113346571.334899902 5422592.7097168
346575.1472778325422599.70007324346579.5540771485422606.05291748
346581.248901367 5422611.9822998346580.9946899415422616.38690186
346580.9100952155422624.68768311346577.8591308595422634.68292236
346576.0792846685422641.45928955346569.6270751955422652.43890381
346565.1353149415422658.36828613346555.3895263675422667.68572998
346545.982727051 5422677.0032959346539.5418701175422683.44067383
 346533.189514165422690.94488525346530.7321166995422700.17767334
346531.664123535 5422705.2598877346536.7489013675422713.98449707
346540.8168945315422725.58911133346547.4271240235422734.05950928
346556.3255004885422741.42871094346564.1223144535422744.30871582
346572.342529297 5422744.0546875346578.6138916025422745.40991211
346582.7664794925422748.20507813 346588.708923345422759.45751953
346593.7937011725422770.46911621 346598.031127935422788.17230225
 346603.031127935422799.01428223346606.1906738285422802.43127441

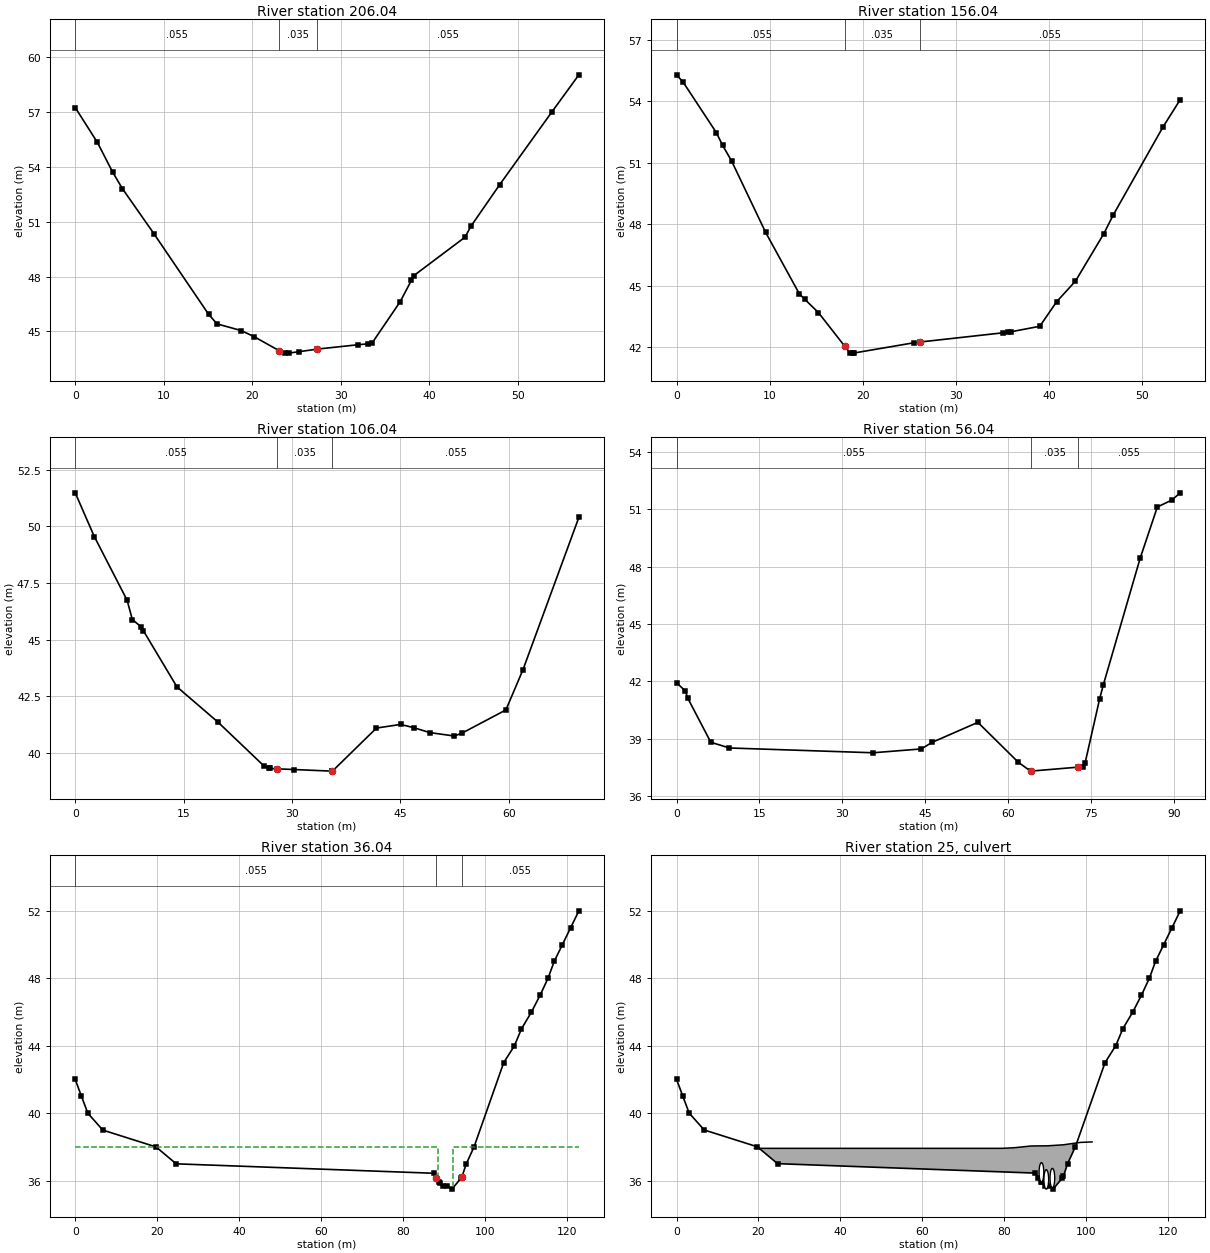
Type RM Length L Ch R = 1 ,206.04  ,48.54,50,51
XS GIS Cut Line= 4
346546.1453247075422636.54229736346565.2993164065422643.02368164
346580.6165161135422652.02508545346599.0537109385422656.33551025
#Sta/Elev= 25
       0   57.24    2.51   55.33    4.24    53.7    5.34    52.8    8.91   50.33
   15.08   45.93   16.02   45.41   18.78   45.04   20.22   44.71   23.02   43.95
   23.68   43.82   24.11   43.81   25.32   43.89   27.36   44.03   31.98   44.27
   33.14   44.32   33.56   44.37   36.72   46.62   37.99   47.79   38.27   48.05
   44.05   50.15   44.72   50.75   47.95   53.01   53.88   57.01   56.92   59.03
#Mann= 3 , 0 , 0
       0    .055       0   23.02    .035       0   27.36    .055       0
Bank Sta=23.02,27.36
XS Rating Curve= 0 ,0
Exp/Cntr=0.5,0.3

Type RM Length L Ch R = 1 ,156.04  ,60.89,50,30.28
XS GIS Cut Line= 4
346524.4650878915422667.72167969346532.7161254885422678.71990967
346549.3566894535422692.80627441346567.6198730475422695.73712158
#Sta/Elev= 25
       0    55.3     .71   54.94    4.27   52.48    4.94   51.86     5.9    51.1
    9.56   47.61   13.18   44.61   13.75   44.35   15.22    43.7   18.04   42.06
   18.63   41.72   18.91   41.73   19.09   41.73   25.53   42.23   26.08   42.26
      35   42.71   35.55   42.73   35.87   42.76   38.98   43.03   40.79   44.23
    42.8   45.23   45.84   47.54   46.86   48.46   52.18   52.74   54.05   54.09
#Mann= 3 , 0 , 0
       0    .055       0   18.04    .035       0   26.08    .055       0
Bank Sta=18.04,26.08
XS Rating Curve= 0 ,0
Exp/Cntr=0.3,0.1

Type RM Length L Ch R = 1 ,106.04  ,34.27,50,45.57
XS GIS Cut Line= 3
 346514.613281255422741.43011475346533.6350708015422736.08831787
346572.9965209965422705.37109375
#Sta/Elev= 25
       0   51.48    2.64   49.55    7.18   46.74     7.9   45.89    9.14   45.56
    9.42    45.4   14.07   42.92   19.76   41.36   26.11   39.43   26.85   39.33
   26.99   39.32   27.96    39.3   30.33   39.27   35.46    39.2   35.59   39.21
   35.62   39.21   41.68    41.1   45.02   41.26   46.82   41.12   49.06    40.9
   52.45   40.75   53.48   40.87   59.59    41.9   61.96   43.68   69.69    50.4
#Mann= 3 , 0 , 0
       0    .055       0   27.96    .035       0   35.59    .055       0
Bank Sta=27.96,35.59
XS Rating Curve= 0 ,0
Exp/Cntr=0.3,0.1

Type RM Length L Ch R = 1 ,56.04   ,20.84,20,20.51
XS GIS Cut Line= 3
346519.9874877935422769.26611328346555.3927001955422766.15808105
346604.9232788095422740.98547363
#Sta/Elev= 21
       0   41.93    1.59    41.5    1.98   41.15    6.19   38.82    9.56   38.52
   35.54   38.27   44.25   38.47   46.27   38.82    54.5   39.86   61.79   37.78
   64.02   37.31   64.07   37.31   72.69   37.52   73.54   37.55   73.88   37.72
   76.53    41.1   77.19   41.82   83.84   48.43   86.96   51.12   89.57   51.48
    91.1   51.86
#Mann= 3 , 0 , 0
       0    .055       0   64.07    .035       0   72.69    .055       0
Bank Sta=64.07,72.69
XS Rating Curve= 0 ,0
Exp/Cntr=0.3,0.1

Type RM Length L Ch R = 1 ,36.04   ,13.27,14.73,14.6
Node Photo=..\..\..\Corner Brook\Windshield Survey\CB photos\P1000691.JPG
XS GIS Cut Line= 6
      346518.119     5422770.428      346534.296      5422792.87
      346542.908     5422790.471      346599.331     5422766.789
       346603.22     5422757.398       346604.92       5422742.5
#Sta/Elev= 27
       0      42    1.53      41    3.08      40    6.74      39   19.74      38
   24.65      37   87.61   36.44   88.19   36.17   88.92   35.91   89.09   35.89
   89.82   35.69   90.68   35.69   91.95    35.5   94.21   36.16   94.41   36.24
   95.46      37   97.35      38   104.6      43  107.21      44  108.93      45
  111.37      46  113.49      47  115.41      48  116.92      49  118.93      50
  120.94      51  122.95      52
#Mann= 3 , 0 , 0
       0    .055       0   88.19    .035       0   94.41    .055       0
#XS Ineff= 2 , 0
       0    88.5      38   92.32       0      38
Permanent Ineff=
       F       F
Bank Sta=88.19,94.41
XS Rating Curve= 0 ,0
Exp/Cntr=0.5,0.3

Type RM Length L Ch R = 2 ,25      ,,,
Node Photo=..\..\..\Corner Brook\Windshield Survey\CB photos\P1000688.JPG
BEGIN DESCRIPTION:
Unnamed Access Road (Structure #2113)
END DESCRIPTION:
Bridge Culvert--1,0,-1,-1, 0
Deck Dist Width WeirC Skew NumUp NumDn MinLoCord MaxHiCord MaxSubmerge Is_Ogee
5.73,3.8,1.67,0, 9, 10, 37.91, , 0.98, 0, 0.35,0.35,,
      19   24.65   79.58   82.63   86.54   90.58   94.42   98.52  101.42
   37.91   37.91   37.91   37.95   38.05   38.06   38.12   38.26   38.29
                                                                        
      19   24.73   86.28   90.35    94.1   98.28  101.93  105.19  107.47  110.56
   37.84   37.84   37.84   37.93   37.95   38.08    38.1   38.21   38.26   38.29
                                                                                
BR Coef=-1 , 0 , 0 ,, 0 ,,,0.8,-1,,0,
WSPro=,,,, 1 ,,,, 0 ,,,, 0 ,,,,-1 ,-1 ,-1 , 0 , 0 , 0 , 0 , 0
Culvert=1,1.15,,11.55,0.032,0.9,1,2,3,35.91,89.07,35.78,96.2,Culvert #1  , 0 ,1.65
Culvert Bottom n=0.032
Culvert=1,1.15,,11.55,0.032,0.9,1,2,3,35.49,90.25,35.39,97.38,Culvert #2  , 0 ,1.65
Culvert Bottom n=0.04
Culvert Bottom Depth=0.3
Culvert Depth Blocked=0.2
Culvert=1,1.15,,11.55,0.032,0.9,1,2,3,35.57,91.74,35.41,98.87,Culvert #3  , 0 ,1.65
Culvert Bottom n=0.032
BC Design=,, 0 ,, 0 ,,,,,,
BC Use User HTab Curves=0
BC User HTab FreeFlow(D)= 0

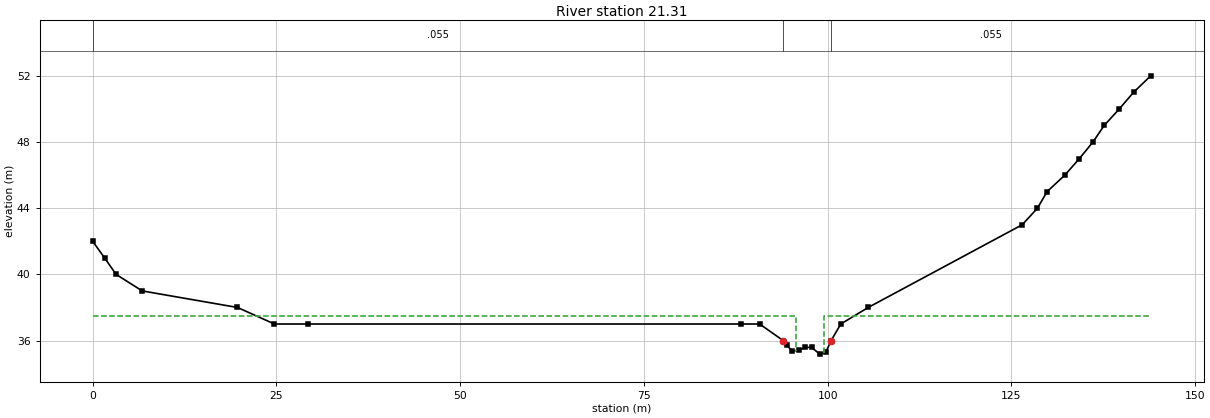
Type RM Length L Ch R = 1 ,21.31   ,13.55,21.32,0.89
Node Photo=..\..\..\Corner Brook\Windshield Survey\CB photos\P1000687.JPG
XS GIS Cut Line= 6
       346517.47      5422770.76      346537.409     5422800.173
      346591.998     5422785.617      346602.369     5422781.331
      346607.009     5422765.512       346605.64     5422742.166
#Sta/Elev= 30
       0      42    1.61      41    3.18      40    6.74      39    19.7      38
   24.73      37   29.26      37   88.19      37   90.75      37   93.95      36
   94.41   35.75   95.14   35.37   96.11   35.41   96.95   35.59   97.81   35.59
   98.93   35.18   99.77   35.31  100.48      36  101.79      37  105.52      38
  126.48      43  128.55      44  129.86      45  132.28      46  134.26      47
   136.1      48  137.63      49  139.69      50  141.62      51  143.96      52
#Mann= 3 , 0 , 0
       0    .055       0   93.95    .035       0  100.48    .055       0
#XS Ineff= 2 , 0
       0   95.63    37.5   99.45       0    37.5
Permanent Ineff=
       F       F
Bank Sta=93.95,100.48
XS Rating Curve= 0 ,0
Exp/Cntr=0.5,0.3

River Reach=CornerB         ,M003
Reach XY= 30
346606.1906738285422802.43127441346583.6029052735422830.79571533
346552.5402832035422851.61987305346531.3267211915422857.67791748
346503.7359008795422859.78729248346427.9735107425422857.51550293
346385.9251098635422863.57348633346368.4996948245422870.76727295
346358.8400878915422877.58251953346316.4130859385422918.47387695
346289.2086791995422938.84869385346243.5617065435422956.07611084
346212.8779296885422970.65307617346179.7316894535422991.47729492
346119.8792724615423010.59771729346086.7332763675423011.35491943
346079.9146728525423014.76269531346072.6348876955423021.69189453
346049.3378906255423035.51147461 346024.904479985423069.20910645
346015.2448730475423076.78149414346006.153320313  5423080.378479
345983.6140747075423080.75708008345968.8402709965423075.26708984
345934.7977294925423057.69189453345917.7510986335423051.63391113
345902.5985107425423052.39111328345880.0593261725423063.56048584
345824.5632934575423079.08410645 345795.121093755423092.33508301

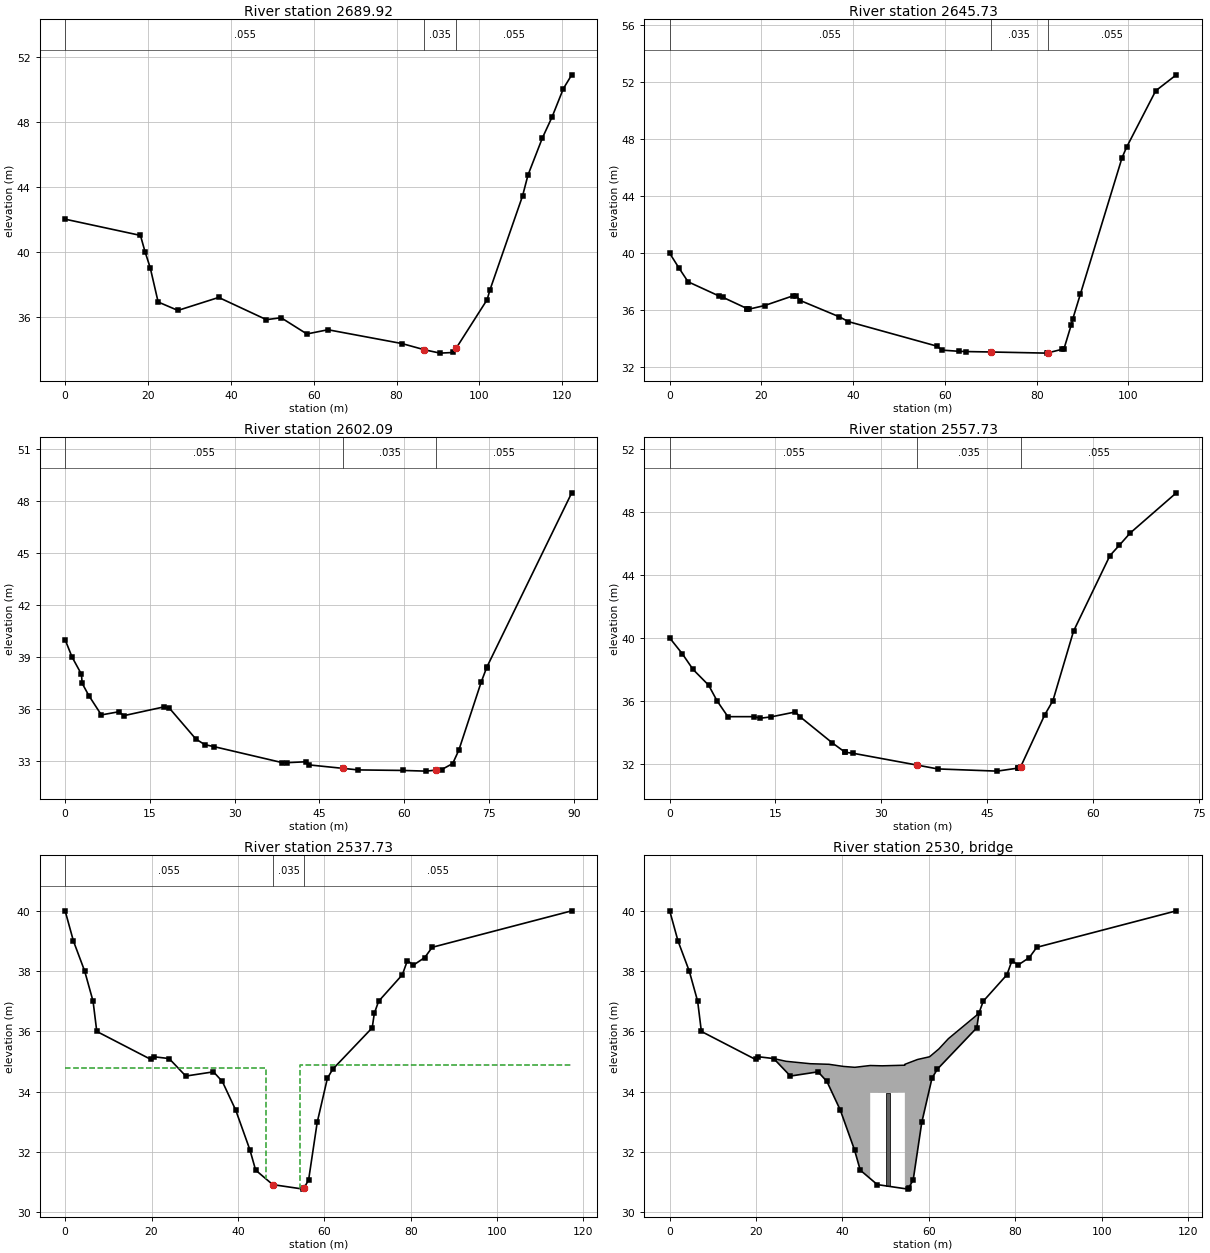
Type RM Length L Ch R = 1 ,2689.92 ,32.25,44.19,49.16
XS GIS Cut Line= 4
      346515.586      5422771.58      346526.609     5422791.136
      346535.579      5422806.78      346578.413     5422876.471
#Sta/Elev= 24
       0      42   18.18      41   19.28      40   20.55      39   22.45    36.9
   27.22   36.38   37.07   37.18   48.59   35.81   52.13   35.93   58.35   34.93
   63.44   35.19   81.29   34.34   86.68   33.96   90.48   33.75   93.72   33.79
   94.38   34.05  101.85   37.04  102.55   37.65  110.42   43.44  111.71   44.71
  115.19      47  117.51   48.28  120.26   50.04  122.28   50.89
#Mann= 3 , 0 , 0
       0    .055       0   86.68    .035       0   94.38    .055       0
Bank Sta=86.68,94.38
XS Rating Curve= 0 ,0
Exp/Cntr=0.3,0.1

Type RM Length L Ch R = 1 ,2645.73 ,40.6,43.64,45.07
XS GIS Cut Line= 4
      346500.489     5422784.788      346505.341     5422795.388
      346515.063     5422818.771      346521.292      5422891.95
#Sta/Elev= 30
       0      40    1.95      39       4      38   10.76      37   11.65    36.9
   16.85   36.12   16.95   36.11   17.18   36.07   20.68   36.33   26.85   37.01
   27.61   36.99   28.49   36.68   36.97   35.54   38.97    35.2   58.25   33.48
   59.35    33.2   63.02   33.12   64.63    33.1      70   33.07   82.21   32.99
   82.46   33.01   85.54   33.26   85.96   33.31   87.48   34.93   87.83   35.36
   89.54   37.16   98.61   46.72   99.58   47.44  105.94   51.41  110.43   52.53
#Mann= 3 , 0 , 0
       0    .055       0      70    .035       0   82.46    .055       0
Bank Sta=70,82.46
XS Rating Curve= 0 ,0
Exp/Cntr=0.3,0.1

Type RM Length L Ch R = 1 ,2602.09 ,43.5,44.36,45.77
XS GIS Cut Line= 4
      346467.292     5422803.732      346468.721     5422806.377
      346476.357     5422828.375      346473.353     5422891.646
#Sta/Elev= 29
       0      40    1.22      39    2.89      38    3.01   37.48    4.19   36.77
    6.41   35.65    9.47   35.83   10.44   35.61   17.44   36.11   18.45   36.04
   23.12   34.26   24.71   33.93    26.3   33.82   38.44   32.89   39.32   32.89
   42.54   32.94   43.17   32.76   49.15   32.56   51.87   32.47    59.7   32.44
   63.85    32.4   65.67   32.46   66.63   32.49   68.58   32.84   69.67   33.62
   73.63   37.56   74.57   38.37   74.66   38.44   89.64   48.49
#Mann= 3 , 0 , 0
       0    .055       0   49.15    .035       0   65.67    .055       0
Bank Sta=49.15,65.67
XS Rating Curve= 0 ,0
Exp/Cntr=0.3,0.1

Type RM Length L Ch R = 1 ,2557.73 ,20.72,20,21.87
XS GIS Cut Line= 4
      346426.875     5422817.542      346430.293     5422824.542
      346435.073     5422834.093      346425.021     5422886.513
#Sta/Elev= 28
       0      40    1.78      39    3.31      38    5.52      37    6.72      36
    8.25      35   12.02      35   12.81    34.9   14.31   34.98   17.83    35.3
   18.47      35   23.07   33.33   24.84   32.75   24.88   32.74   26.06   32.67
   35.13   31.92   38.01   31.68   46.44   31.54   49.37   31.73   49.41   31.74
   49.77   31.81   53.17    35.1   54.35   36.02   57.27   40.43   62.43   45.23
   63.79    45.9   65.29   46.66   71.85   49.22
#Mann= 3 , 0 , 0
       0    .055       0   35.13    .035       0   49.77    .055       0
Bank Sta=35.13,49.77
XS Rating Curve= 0 ,0
Exp/Cntr=0.3,0.1

Type RM Length L Ch R = 1 ,2537.73 ,11.04,10.51,9.54
Node Photo=..\..\..\Corner Brook\Windshield Survey\CB photos\P1000682.JPG
XS GIS Cut Line= 5
      346421.014     5422819.905      346429.358     5422837.089
      346415.976      5422848.06      346395.257     5422892.012
      346378.326     5422919.521
#Sta/Elev= 30
       0      40    1.92      39    4.53      38    6.47      37    7.33      36
   19.88   35.07   20.55   35.16   24.08    35.1   27.94   34.52   34.35   34.66
    36.4   34.34    39.5   33.39   42.79   32.07   44.11    31.4   48.07   30.92
   55.17   30.77   55.36   30.82   56.37   31.07   58.36   32.98   60.73   34.45
   61.98   34.75    71.1   36.12   71.59    36.6   72.58      37   78.08   37.88
   79.25   38.35   80.64    38.2   83.26   38.45   84.99   38.79   117.3      40
#Mann= 3 , 0 , 0
       0    .055       0   48.07    .035       0   55.36    .055       0
#XS Ineff= 2 , 0
       0   46.41    34.8   54.45       0   34.88
Permanent Ineff=
       F       F
Bank Sta=48.07,55.36
XS Rating Curve= 0 ,0
Exp/Cntr=0.5,0.3

Type RM Length L Ch R = 3 ,2530    ,,,
Node Photo=..\..\..\Corner Brook\Windshield Survey\CB photos\P1000683.JPG
BEGIN DESCRIPTION:
Unnamed Access Road (Structure #2112)
END DESCRIPTION:
Bridge Culvert--1,0,-1,-1, 0
Deck Dist Width WeirC Skew NumUp NumDn MinLoCord MaxHiCord MaxSubmerge Is_Ogee
2.5,4.8,1.67,0, 16, 14, 34.81, , 0.98, 0, 0,0,,
   24.08   26.92   32.53   36.88   40.22   42.85   46.41   46.42   49.19   54.44
   54.45   57.38   60.17   62.32   64.52   71.59
    35.1   35.01   34.93   34.91   34.84   34.81   34.87   34.87   34.86   34.88
   34.91   35.07   35.16   35.42   35.76    36.6
                                                      30   33.97   33.96   33.98
      30
   28.33   28.82   33.11   36.64   41.75   45.37   45.38   48.84    53.4   53.41
   56.27   58.83   61.25   74.92
   34.98      35   34.91   34.89   34.84   34.87   34.87   34.87   34.86   34.86
   35.09   35.24   35.47   36.93
                                              30   33.97   33.97   33.96      30
                                
Pier Skew, UpSta & Num, DnSta & Num=  ,50.45, 2 ,49.13, 2 , 0 , 0 , 0 ,,
      .9      .9
      30      35
      .9      .9
      30      35
BR Coef=-1 , 0 , 0 ,, 0 ,,,0.8,-1,,0,
WSPro=,,,, 1 ,,,, 0 ,,,, 0 ,,,,-1 ,-1 ,-1 , 0 , 0 , 0 , 0 , 0
BC Design=,, 0 ,, 0 ,,,,,,
BC Use User HTab Curves=0
BC User HTab FreeFlow(D)= 0

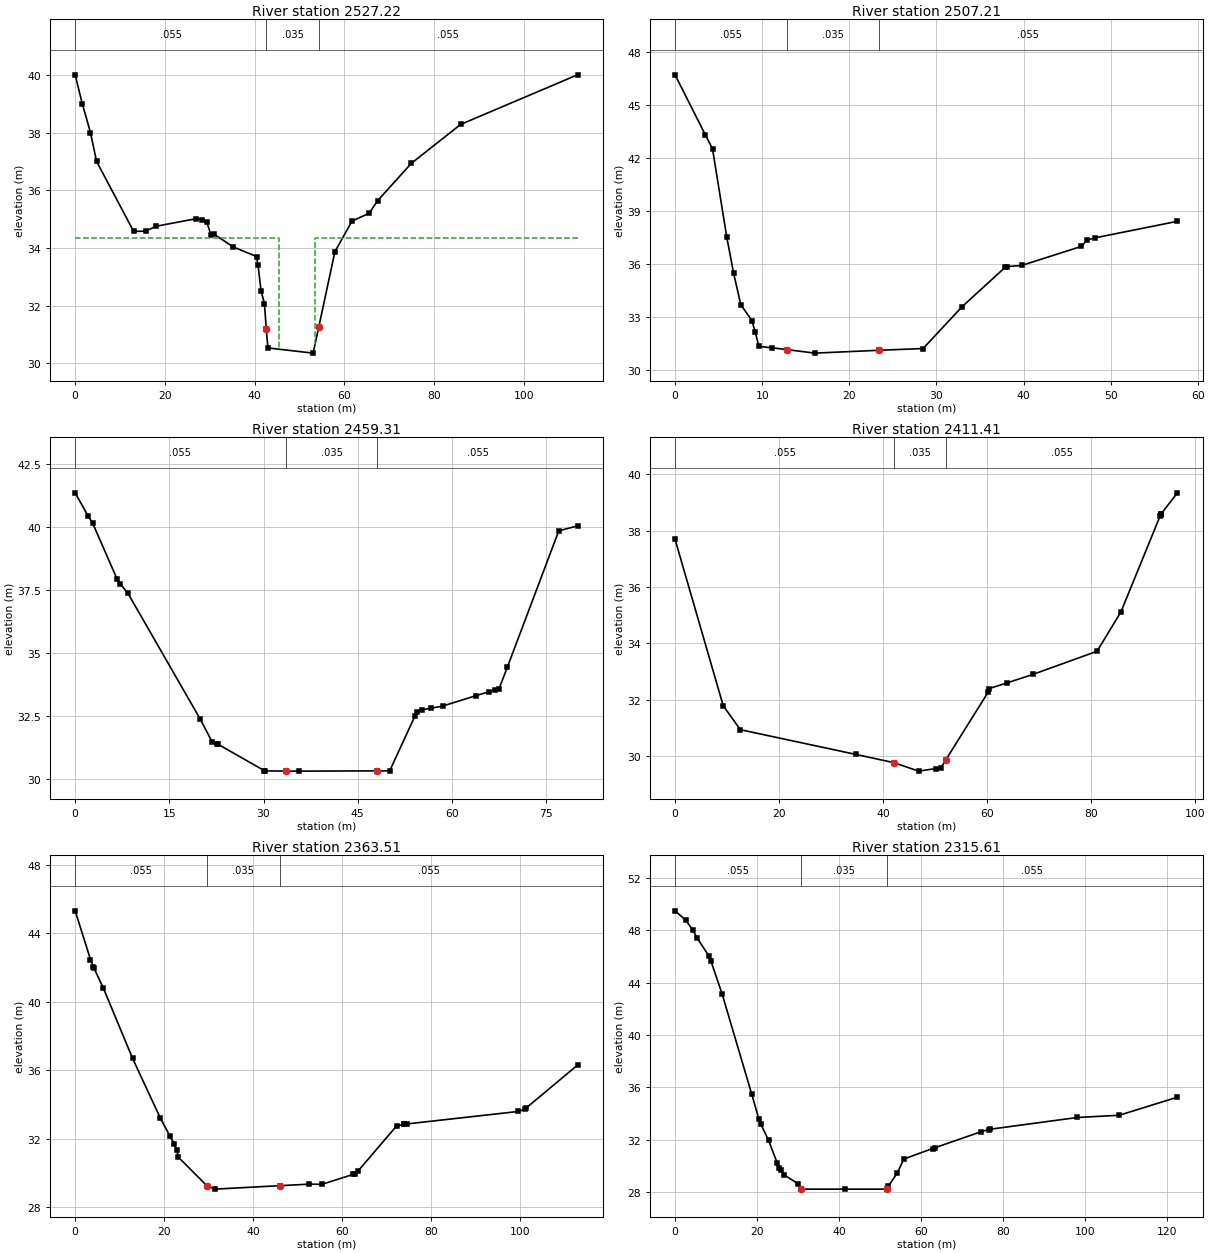
Type RM Length L Ch R = 1 ,2527.22 ,25.24,20,17.15
Node Photo=..\..\..\Corner Brook\Windshield Survey\CB photos\P1000681.JPG
XS GIS Cut Line= 5
      346416.801      5422822.79       346422.92     5422834.307
      346405.973     5422848.705      346384.378     5422894.516
      346372.314     5422917.599
#Sta/Elev= 28
       0      40    1.58      39    3.41      38    4.77      37   13.04   34.57
   15.69   34.58   18.08   34.75   26.92   35.01   28.33   34.98   29.31   34.91
   30.27   34.45   30.86   34.48   35.28   34.03   40.42    33.7   40.76    33.4
   41.43   32.52   42.19   32.06   42.61   31.17   42.96   30.53   53.03   30.35
   54.29   31.25    57.9   33.87   61.72   34.93   65.54    35.2   67.39   35.63
   74.92   36.93   85.92   38.28  111.97      40
#Mann= 3 , 0 , 0
       0    .055       0   42.61    .035       0   54.29    .055       0
#XS Ineff= 2 , 0
       0   45.37   34.35   53.41       0   34.35
Permanent Ineff=
       F       F
Bank Sta=42.61,54.29
XS Rating Curve= 0 ,0
Exp/Cntr=0.5,0.3

Type RM Length L Ch R = 1 ,2507.21 ,53.89,47.9,41.51
XS GIS Cut Line= 3
346375.898681641 5422847.8994751346386.2429199225422884.35992432
346377.0280761725422901.84527588
#Sta/Elev= 22
       0    46.7    3.47   43.31     4.3   42.51    5.94    37.5    6.73   35.46
    7.54    33.7    8.83   32.78    9.18   32.17    9.63   31.33   11.17   31.25
   12.84   31.15   16.03   30.95   23.36   31.11   28.47   31.21   32.95   33.58
    37.9   35.81   38.14   35.85   39.77   35.91   46.64   36.99   47.28   37.35
   48.16   37.47   57.66   38.41
#Mann= 3 , 0 , 0
       0    .055       0   12.84    .035       0   23.36    .055       0
Bank Sta=12.84,23.36
XS Rating Curve= 0 ,0
Exp/Cntr=0.3,0.1

Type RM Length L Ch R = 1 ,2459.31 ,45.43,47.9,50.41
XS GIS Cut Line= 2
346314.5562744145422865.28967285346371.1104736335422921.87249756
#Sta/Elev= 28
       0   41.37    2.04   40.46    2.78   40.17    6.69   37.94    7.18   37.76
    8.39   37.39   19.88   32.41   21.81   31.49   22.58   31.42   22.79   31.39
   30.12   30.35   30.31   30.34   33.51   30.33   35.69   30.33   48.13   30.34
   50.09   30.34   54.14   32.53   54.45   32.68   55.17   32.76   56.73   32.83
   58.52   32.91   63.91   33.33   65.93   33.48    66.8   33.54   67.49   33.59
   68.84   34.46   77.01   39.86      80   40.06
#Mann= 3 , 0 , 0
       0    .055       0   33.51    .035       0   48.13    .055       0
Bank Sta=33.51,48.13
XS Rating Curve= 0 ,0
Exp/Cntr=0.3,0.1

Type RM Length L Ch R = 1 ,2411.41 ,43.95,47.9,53.88
XS GIS Cut Line= 2
346283.4758911135422892.98492432346340.3834838875422971.04272461
#Sta/Elev= 20
       0   37.69    9.26   31.79   12.55   30.94   34.83   30.06   42.09   29.77
   46.84   29.47    50.1   29.56   51.12   29.59   52.05  29.864   60.17   32.26
   60.44    32.4   63.85    32.6   68.81    32.9   81.14   33.72   85.72   35.11
    93.3   38.53   93.36   38.56   93.48   38.59    93.5    38.6    96.6   39.34
#Mann= 3 , 0 , 0
       0    .055       0   42.09    .035       0   52.05    .055       0
Bank Sta=42.09,52.05
XS Rating Curve= 0 ,0
Exp/Cntr=0.3,0.1

Type RM Length L Ch R = 1 ,2363.51 ,48.76,47.9,46.93
XS GIS Cut Line= 2
346250.454711914 5422910.3057251346292.1392822275423015.34210205
#Sta/Elev= 27
       0    45.3    3.45   42.46     4.1   42.04    4.23   41.96    6.35   40.79
   12.91    36.7   19.15   33.22   21.34   32.16   22.28   31.72   22.87   31.33
   23.23   30.93   29.62   29.27   31.45   29.07   45.98   29.27   52.63   29.36
   55.51   29.35   62.53   29.93   62.92   29.97   63.62   30.12   72.32   32.76
   73.94   32.85   73.98   32.85   74.55   32.87   99.72    33.6  101.11   33.73
  101.45    33.8  113.01    36.3
#Mann= 3 , 0 , 0
       0    .055       0   29.62    .035       0   45.98    .055       0
Bank Sta=29.62,45.98
XS Rating Curve= 0 ,0
Exp/Cntr=0.3,0.1

Type RM Length L Ch R = 1 ,2315.61 ,48.49,47.9,49.46
XS GIS Cut Line= 2
346204.1672973635422930.50671387346256.7380981455423041.16589355
#Sta/Elev= 30
       0   49.48    2.56   48.78    4.28   48.03    5.45   47.37    8.33      46
    8.74   45.65   11.46   43.15   18.72   35.46   20.46   33.55   20.87   33.22
    22.8   31.96   24.87   30.26   25.41   29.81   25.85   29.66   26.63   29.31
   29.98   28.65   30.71   28.23    41.4   28.23   51.63   28.23   51.99   28.44
    54.2   29.47    55.8   30.53   62.79   31.33   63.38   31.39    74.5    32.6
   76.48   32.78   76.74    32.8    98.1    33.7  108.33   33.87  122.51   35.25
#Mann= 3 , 0 , 0
       0    .055       0   30.71    .035       0   51.63    .055       0
Bank Sta=30.71,51.63
XS Rating Curve= 0 ,0
Exp/Cntr=0.3,0.1