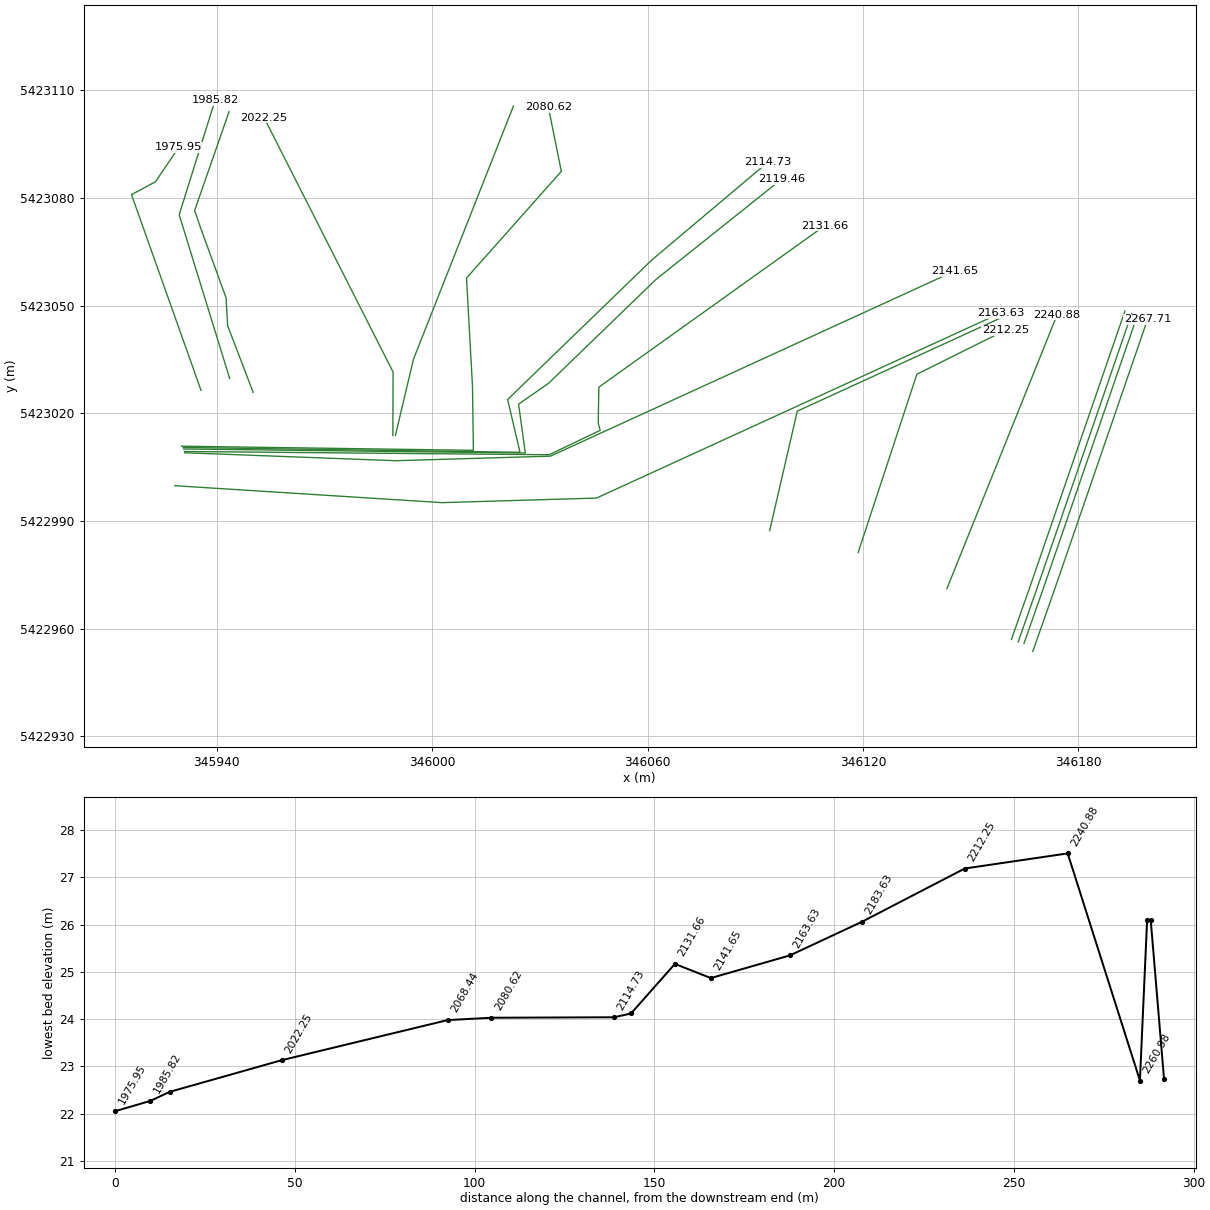
HEC-RAS study Corner_Brook2.prj: Corner_Brook2

--- Corner_Brook2.g01 (geometry) --- (continued)

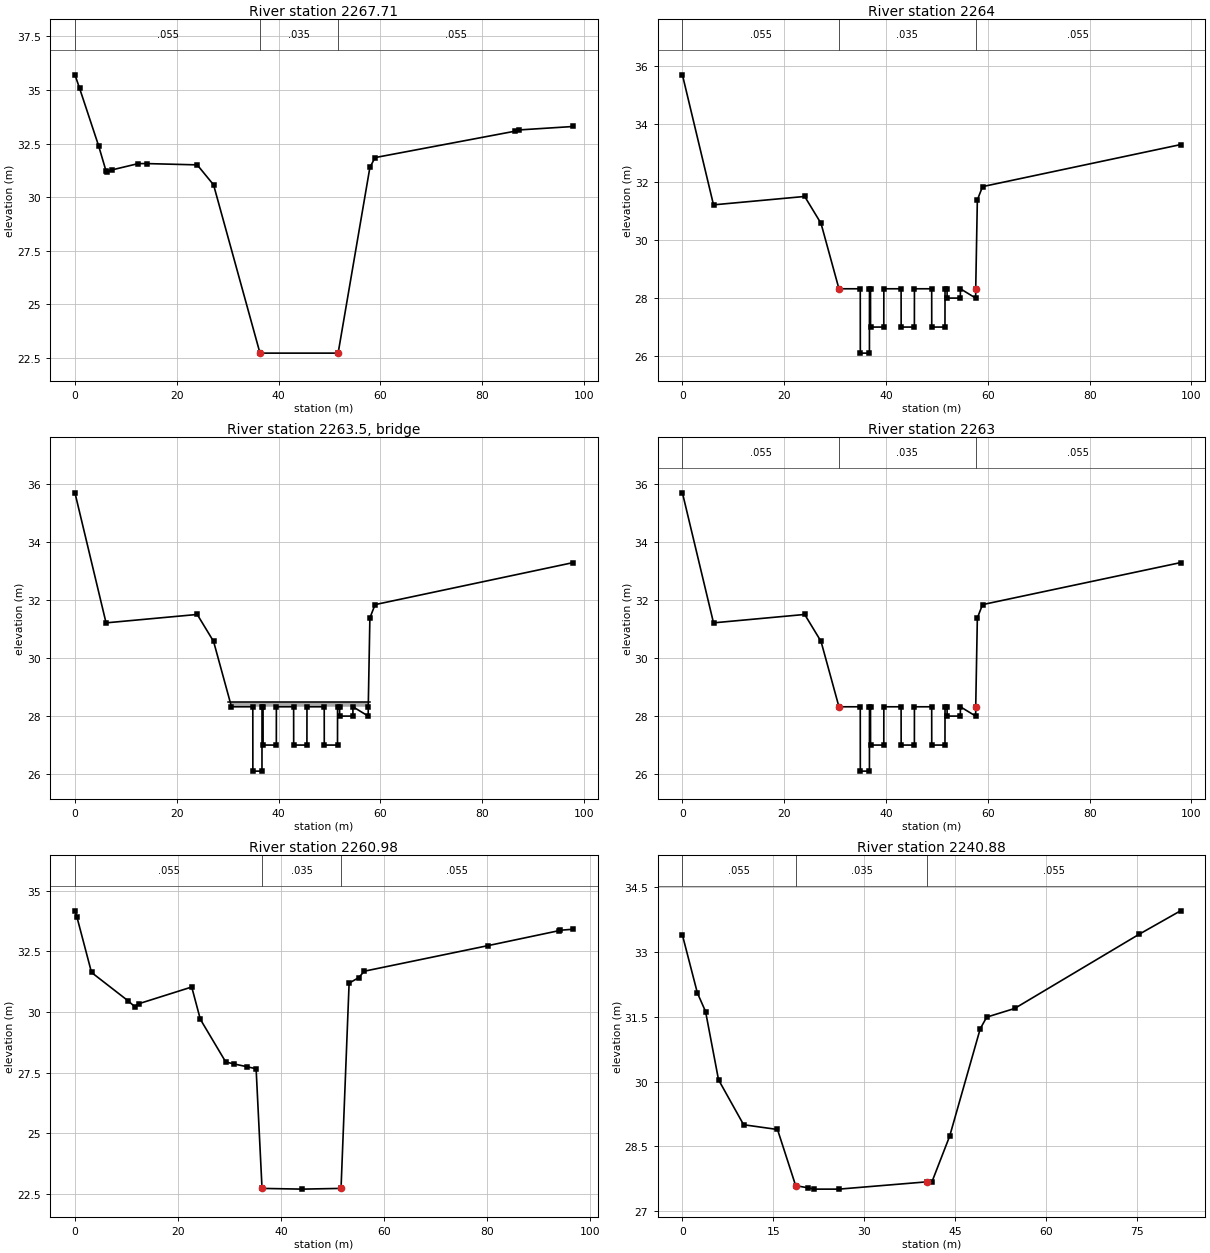
Type RM Length L Ch R = 1 ,2267.71 ,3.71,3.71,3.71
XS GIS Cut Line= 3
       346167.32     5422953.681      346172.939     5422969.644
      346199.281     5423046.168
#Sta/Elev= 17
       0   35.71      .9   35.09    4.65    32.4    6.11   31.22    6.36   31.18
    7.34   31.28   12.44   31.57   14.17   31.57   24.02   31.51   27.23   30.58
   36.35   22.73    51.7   22.73   57.94   31.39   58.96   31.85   86.42   33.08
   87.27   33.14   97.85    33.3
#Mann= 3 , 0 , 0
       0    .055       0   36.35    .035       0    51.7    .055       0
Bank Sta=36.35,51.7
XS Rating Curve= 0 ,0
Exp/Cntr=0.5,0.3

Type RM Length L Ch R = 1 ,2264    ,1,1,1
Node Photo=..\..\..\Corner Brook\Windshield Survey\CB photos\P1000680.JPG
XS GIS Cut Line= 3
      346164.876     5422955.935      346170.276     5422971.289
      346196.486     5423047.406
#Sta/Elev= 30
       0   35.71    6.11   31.22   24.02   31.51   27.23   30.58   30.75  28.322
   34.94  28.322   34.95    26.1   36.74    26.1   36.75  28.322   36.95  28.322
   36.96      27   39.56      27   39.57  28.322   42.96  28.322   42.97      27
   45.57      27   45.58  28.322   48.97  28.322   48.98      27   51.58      27
   51.59  28.322   51.99  28.322      52      28    54.6      28   54.61  28.322
   57.61      28   57.62  28.322   57.94   31.39   58.96   31.85   97.85    33.3
#Mann= 3 , 0 , 0
       0    .055       0   30.75    .035       0   57.62    .055       0
Bank Sta=30.75,57.62
XS Rating Curve= 0 ,0
Exp/Cntr=0.5,0.3

Type RM Length L Ch R = 3 ,2263.5  ,,,
Node Photo=..\..\..\Corner Brook\Windshield Survey\CB photos\P1000676.JPG
BEGIN DESCRIPTION:
Bowater Dam
END DESCRIPTION:
Bridge Culvert--1,0,-1,-1, 0
Deck Dist Width WeirC Skew NumUp NumDn MinLoCord MaxHiCord MaxSubmerge Is_Ogee
0.3,0.6,1.67,0, 2, 2, 26.1, , 0.98, 0, 0,0,,
      30      58
    28.5    28.5
  28.322  28.322
      30      58
    28.5    28.5
  28.322  28.322
BR Coef=-1 , 0 , 0 ,, 0 ,,,0.8,-1,,0,
WSPro=,,,, 1 ,,,, 0 ,,,, 0 ,,,,-1 ,-1 ,-1 , 0 , 0 , 0 , 0 , 0
BC Design=,, 0 ,, 0 ,,,,,,
BC Use User HTab Curves=0
BC User HTab FreeFlow(D)= 0

Type RM Length L Ch R = 1 ,2263    ,2,2,2
Node Photo=..\..\..\Corner Brook\Windshield Survey\CB photos\P1000677.JPG
BEGIN DESCRIPTION:
Bowater Dam
END DESCRIPTION:
XS GIS Cut Line= 3
      346163.246     5422956.327      346168.647     5422971.682
      346194.856     5423047.798
#Sta/Elev= 30
       0   35.71    6.11   31.22   24.02   31.51   27.23   30.58   30.75  28.322
   34.94  28.322   34.95    26.1   36.74    26.1   36.75  28.322   36.95  28.322
   36.96      27   39.56      27   39.57  28.322   42.96  28.322   42.97      27
   45.57      27   45.58  28.322   48.97  28.322   48.98      27   51.58      27
   51.59  28.322   51.99  28.322      52      28    54.6      28   54.61  28.322
   57.61      28   57.62  28.322   57.94   31.39   58.96   31.85   97.85    33.3
#Mann= 3 , 0 , 0
       0    .055       0   30.75    .035       0   57.62    .055       0
Bank Sta=30.75,57.62
XS Rating Curve= 0 ,0
Exp/Cntr=0.5,0.3

Type RM Length L Ch R = 1 ,2260.98 ,23.13,20.09,20.28
XS GIS Cut Line= 3
      346161.359     5422956.991       346166.76     5422972.345
      346192.969     5423048.462
#Sta/Elev= 22
       0   34.17     .39   33.91    3.22   31.63   10.33   30.46   11.61   30.22
   12.39   30.34   22.69   31.03   24.36    29.7    29.3   27.94   30.89   27.86
   33.52   27.74    35.2   27.66   36.35   22.73   44.17    22.7    51.7   22.73
   53.27   31.19   55.17   31.42   56.19   31.68   80.35   32.74   93.99   33.35
   94.25   33.37   96.78   33.41
#Mann= 3 , 0 , 0
       0    .055       0   36.35    .035       0    51.7    .055       0
Bank Sta=36.35,51.7
XS Rating Curve= 0 ,0
Exp/Cntr=0.5,0.3

Type RM Length L Ch R = 1 ,2240.88 ,28.07,28.63,29.71
XS GIS Cut Line= 2
346143.3950805665422971.15368652346174.0800781255423047.40252686
#Sta/Elev= 18
       0   33.39    2.47   32.05    3.82   31.62    5.96   30.04    10.1      29
   15.69   28.89   18.69   27.59   20.74   27.54   21.67   27.51   25.84   27.51
   40.44   27.68   41.18   27.68   44.11   28.74   49.14   31.22   50.21   31.49
   54.81   31.69   75.39   33.41   82.19   33.95
#Mann= 3 , 0 , 0
       0    .055       0   18.69    .035       0   40.44    .055       0
Bank Sta=18.69,40.44
XS Rating Curve= 0 ,0
Exp/Cntr=0.3,0.1

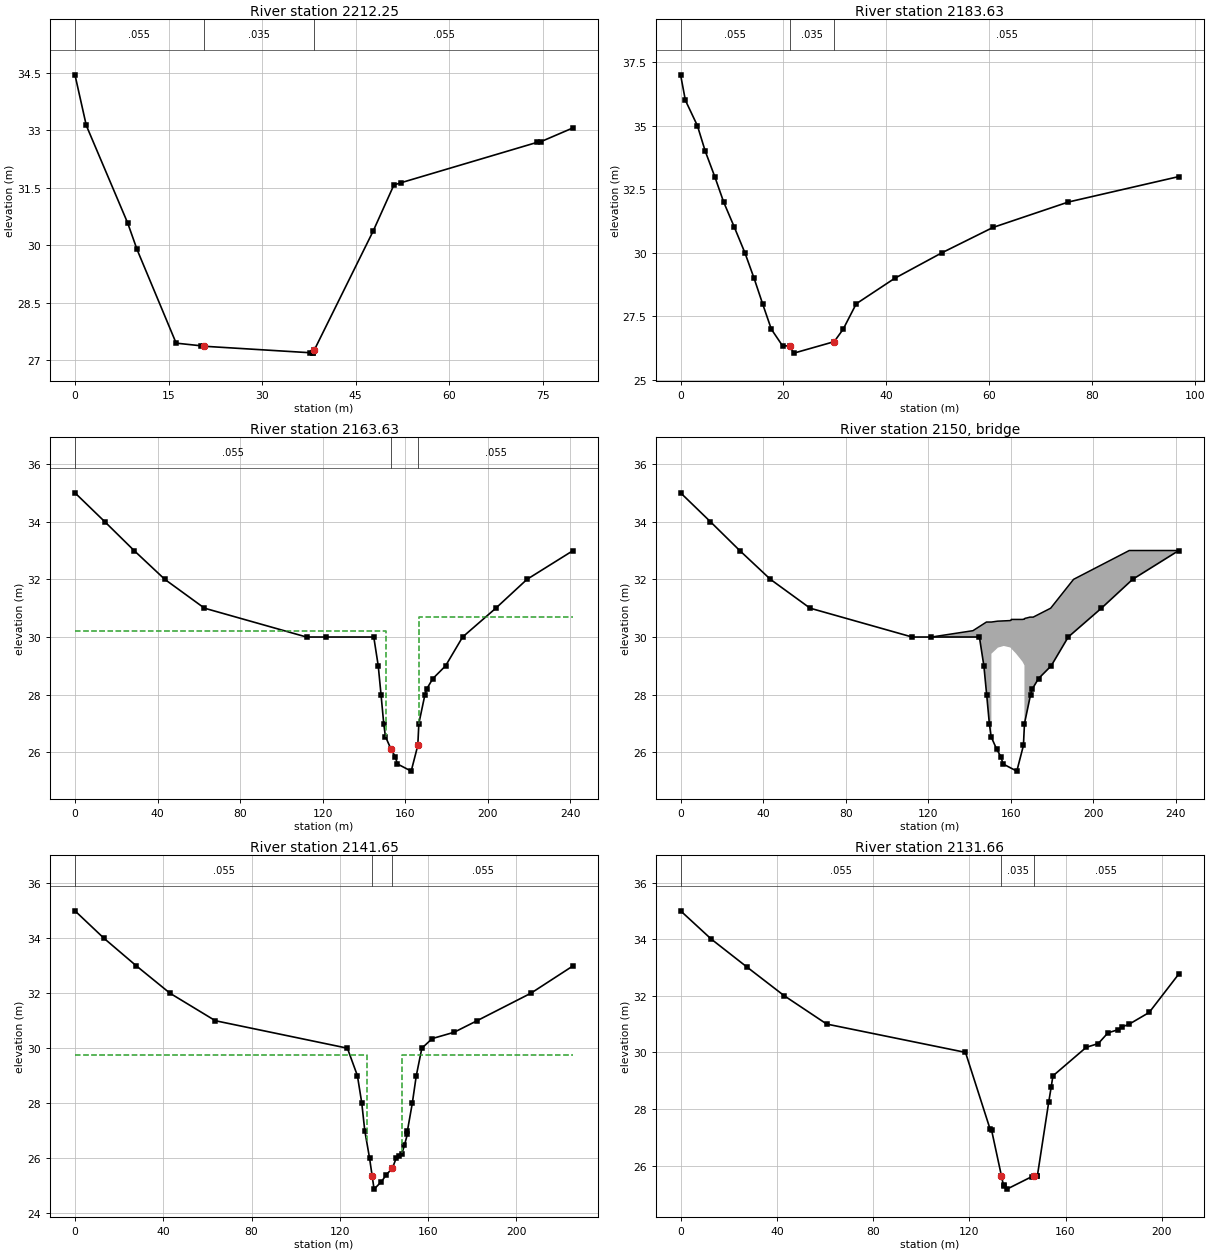
Type RM Length L Ch R = 1 ,2212.25 ,26.98,28.63,31.48
XS GIS Cut Line= 3
346118.6710815435422981.20568848346135.0164794925423030.85992432
346159.7166748055423043.15087891
#Sta/Elev= 17
       0   34.44    1.82   33.12    8.45   30.58    9.95   29.89   16.22   27.45
   20.27   27.38   20.61   27.37   37.72    27.2   38.12   27.19   38.14   27.19
   38.33   27.26    47.8   30.37   51.12   31.57   52.28   31.63   74.06   32.68
    74.7    32.7   79.86   33.06
#Mann= 3 , 0 , 0
       0    .055       0   20.61    .035       0   38.33    .055       0
Bank Sta=20.61,38.33
XS Rating Curve= 0 ,0
Exp/Cntr=0.3,0.1

Type RM Length L Ch R = 1 ,2183.63 ,26.62,19.98,12.38
XS GIS Cut Line= 3
       346094.03      5422987.31      346101.712     5423020.588
      346158.706     5423046.703
#Sta/Elev= 22
       0      37     .93      36    3.27      35    4.79      34    6.64      33
    8.37      32   10.47      31   12.51      30   14.29      29   15.94      28
   17.64      27   19.81   26.35   21.18   26.34   22.02   26.06   29.85   26.51
    31.6      27   34.14      28   41.61      29   50.75      30   60.71      31
   75.37      32   96.84      33
#Mann= 3 , 0 , 0
       0    .055       0   21.18    .035       0   29.85    .055       0
Bank Sta=21.18,29.85
XS Rating Curve= 0 ,0
Exp/Cntr=0.3,0.1

Type RM Length L Ch R = 1 ,2163.63 ,22.26,22,21.26
Node Photo=..\..\..\Corner Brook\Windshield Survey\CB photos\P1000674.JPG
XS GIS Cut Line= 4
      345928.344     5422999.821       346002.75     5422995.103
      346045.799     5422996.378      346158.322     5423047.918
#Sta/Elev= 26
       0      35   14.43      34   28.63      33   43.53      32   62.75      31
  112.18      30  121.52      30  144.77      30  146.94      29  148.29      28
  149.59      27  150.41   26.55  153.14   26.11   155.2   25.85  156.19    25.6
   162.9   25.35   166.1   26.24  166.61      27  169.55      28  170.42    28.2
  173.42   28.56  179.55      29  187.81      30   203.9      31  219.01      32
  241.39      33
#Mann= 3 , 0 , 0
       0    .055       0  153.14    .035       0   166.1    .055       0
#XS Ineff= 2 , 0
       0  150.58   30.22   166.6       0   30.69
Permanent Ineff=
       F       F
Bank Sta=153.14,166.1
XS Rating Curve= 0 ,0
Exp/Cntr=0.5,0.3

Type RM Length L Ch R = 3 ,2150    ,,,
Node Photo=..\..\..\Corner Brook\Windshield Survey\CB photos\P1000666.JPG
BEGIN DESCRIPTION:
O'Connell Drive (Structure 2110-C)
END DESCRIPTION:
Bridge Culvert--1,0,-1,-1, 0
Deck Dist Width WeirC Skew NumUp NumDn MinLoCord MaxHiCord MaxSubmerge Is_Ogee
2.8,14,1.67,0, 24, 21, 30, , 0.98, 0, 0,0,,
  121.52  141.64  148.18  150.55  150.58  150.59  153.59  153.63  156.59  159.59
  160.05  160.21  162.59  165.59  166.59   166.6  166.93  167.66  169.24  170.83
   179.3  190.38  217.37  241.39
      30   30.22   30.52   30.52   30.52   30.52   30.55   30.55   30.56   30.57
   30.58   30.61   30.61   30.61   30.62   30.63   30.65   30.66   30.69   30.69
      31      32      33      33
                                      24   29.42   29.62   29.63   29.69   29.64
   29.62    29.6   29.42   29.15   29.02      24
                                
   63.59  121.13  129.24  131.89  132.23  132.24  134.88  135.24  138.24  138.43
  141.24  143.24  147.24  148.23  148.24  148.38  150.89  153.03  155.32  162.74
   171.7
      31   30.13   30.46   30.47   30.48   30.48    30.5  30.505   30.51   30.53
   30.54   30.55   30.58   30.59   30.59   30.59    30.6   30.61   30.56   30.49
   30.58
                                      24   29.42   29.59   29.62   29.69   29.69
   29.64   29.57   29.15   29.02      24
        
BR Coef=-1 , 0 , 0 ,, 0 ,,,0.8,-1,,0,
WSPro=,,,, 1 ,,,, 0 ,,,, 0 ,,,,-1 ,-1 ,-1 , 0 , 0 , 0 , 0 , 0
BC Design=,, 0 ,, 0 ,,,,,,
BC Use User HTab Curves=0
BC User HTab FreeFlow(D)= 0

Type RM Length L Ch R = 1 ,2141.65 ,9.72,9.99,12.86
Node Photo=..\..\..\Corner Brook\Windshield Survey\CB photos\P1000672.JPG
XS GIS Cut Line= 4
      345931.094     5423008.999      345989.918     5423006.781
      346032.967     5423008.056      346145.491     5423059.596
#Sta/Elev= 29
       0      35   13.16      34   27.76      33   43.07      32   63.59      31
  123.41      30  127.95      29  129.93      28  131.28      27  133.45      26
  134.61   25.36   135.5   24.87  138.82   25.14   141.1    25.4  143.78   25.63
  145.54      26  146.89   26.07   148.1   26.16  149.26   26.47  150.59   26.87
  150.62      27  152.82      28  154.62      29  157.14      30  161.84   30.35
  171.77   30.58  182.15      31  206.52      32   225.7      33
#Mann= 3 , 0 , 0
       0    .055       0  134.61    .035       0  143.78    .055       0
#XS Ineff= 2 , 0
       0  132.23   29.75  148.24       0   29.75
Permanent Ineff=
       F       F
Bank Sta=134.61,143.78
XS Rating Curve= 0 ,0
Exp/Cntr=0.5,0.3

Type RM Length L Ch R = 1 ,2131.66 ,11.18,12.2,13.35
XS GIS Cut Line= 6
       345931.02     5423009.346      346032.623     5423008.449
       346046.82     5423015.244      346046.274     5423017.228
      346046.445     5423027.265      346109.389     5423072.259
#Sta/Elev= 27
       0      35   12.77      34   27.81      33   43.09      32   60.74      31
  118.41      30   128.6    27.3  129.24   27.26  133.32  25.651  134.21    25.3
  134.39   25.28  135.63   25.17  145.96   25.61   146.8   25.62  148.21   25.63
  148.29   25.64  153.03   28.26  154.04   28.78  154.75   29.17  168.61   30.18
  173.58   30.31  177.62   30.69   181.8    30.8  183.46    30.9   186.3   30.99
  194.75   31.41  207.08   32.77
#Mann= 3 , 0 , 0
       0    .055       0  133.32    .035       0   146.8    .055       0
Bank Sta=133.32,146.8
XS Rating Curve= 0 ,0
Exp/Cntr=0.3,0.1

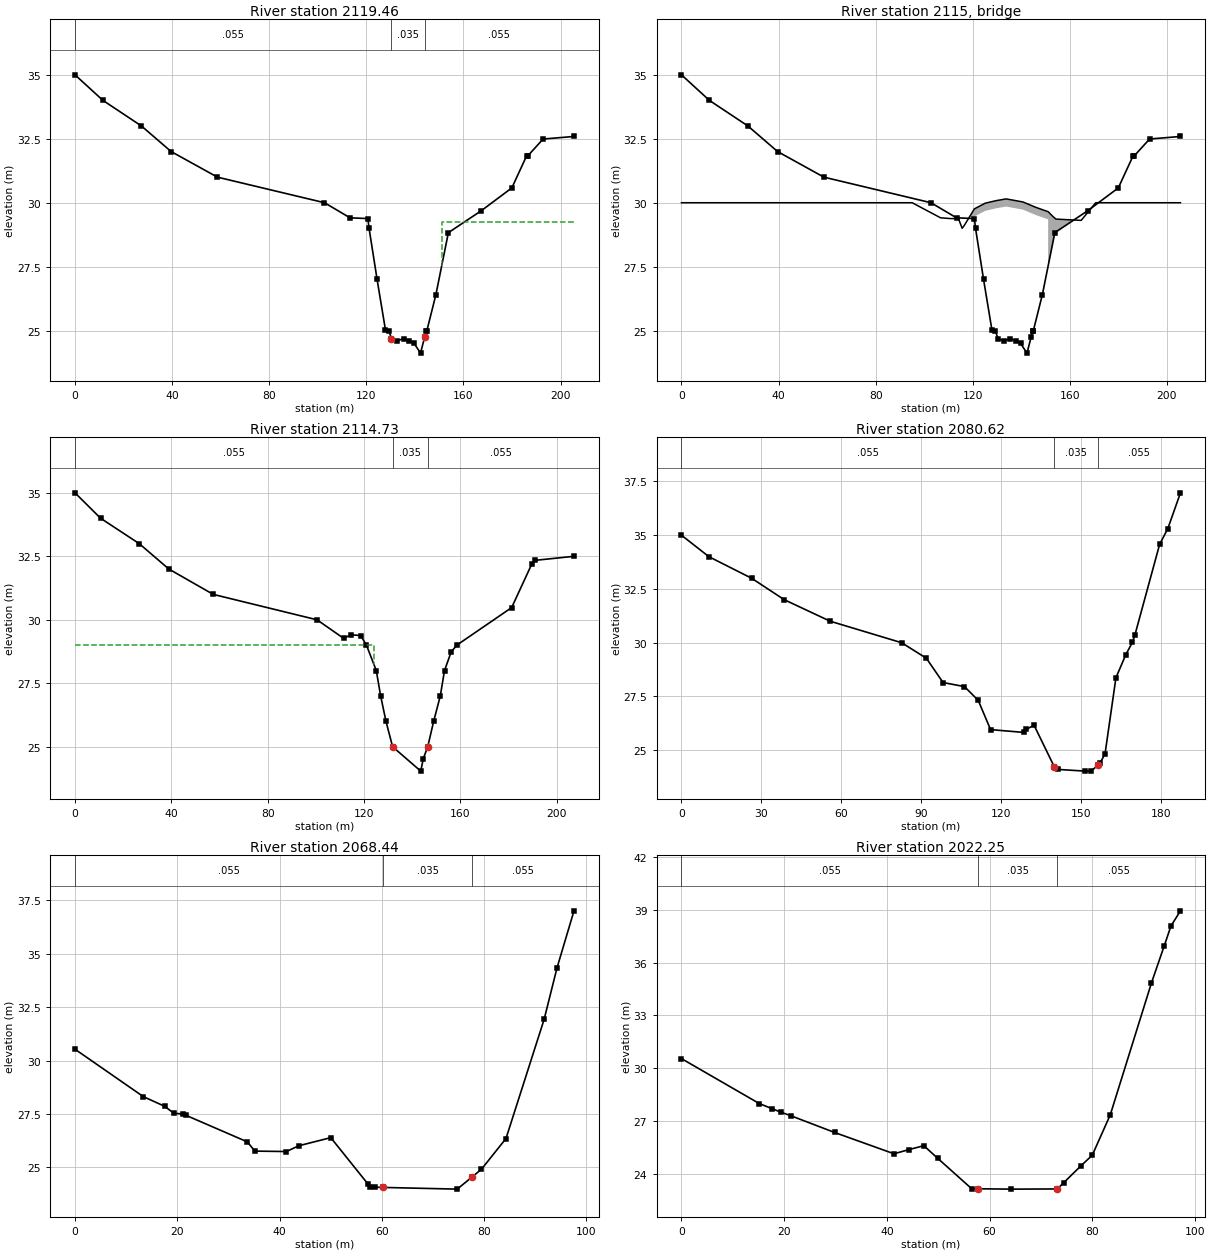
Type RM Length L Ch R = 1 ,2119.46 ,4.74,4.73,4.89
Node Photo=..\..\..\Corner Brook\Windshield Survey\CB photos\P1000665.JPG
XS GIS Cut Line= 6
      345930.788     5423010.049      346025.969      5423008.93
      346024.086     5423022.536      346032.457     5423028.361
      346062.357     5423057.266      346097.406     5423085.242
#Sta/Elev= 29
       0      35   11.52      34   27.38      33   39.61      32   58.67      31
  102.78      30   113.3   29.41  120.67   29.38  121.14      29  124.45      27
  127.87   25.04  129.31      25  130.35   24.69  132.68    24.6  135.48   24.69
  137.61    24.6   139.7    24.5  142.33   24.12  144.11   24.77  144.62      25
  144.96      25  148.68   26.41  153.81   28.83  167.41   29.69  179.96   30.58
  186.08   31.84  186.61   31.84  192.83   32.49  205.56   32.59
#Mann= 3 , 0 , 0
       0    .055       0  130.35    .035       0  144.11    .055       0
#XS Ineff= 2 , 0
       0  116.42   29.38  151.05       0   29.25
Permanent Ineff=
       F       F
Bank Sta=130.35,144.11
XS Rating Curve= 0 ,0
Exp/Cntr=0.4,0.2

Type RM Length L Ch R = 3 ,2115    ,,,
Node Photo=..\..\..\Corner Brook\Windshield Survey\CB photos\P1000664.JPG
BEGIN DESCRIPTION:
Pedestrian Bridge (Structure 2110A)
END DESCRIPTION:
Bridge Culvert--1,0,-1,-1, 0
Deck Dist Width WeirC Skew NumUp NumDn MinLoCord MaxHiCord MaxSubmerge Is_Ogee
1.12,1.96,1.67,0, 22, 21, 29.25, , 0.98, 0, 0,0,,
       0   95.04  106.74  110.86  114.11  115.62  116.42  116.43  120.67  125.09
  129.55  133.78  135.47  140.66  145.94  151.04  151.05  153.03  154.28  164.66
  170.67  205.55
      30      30   29.41   29.38   29.38      29    29.1    29.1   29.76   29.98
   30.08   30.15   30.12   30.03   29.82   29.65   29.65   29.46   29.36   29.31
      30      30
                                                      24    28.8   29.46   29.68
   29.78   29.85   29.82   29.73   29.52   29.35      24
                
       0  102.44  114.49  118.56  121.79  124.11  124.12  128.41  132.78  137.25
  141.47  143.06  148.35  153.63  158.74  158.75  160.59   162.9  165.77  172.31
  207.13
      30      30   29.41   29.38   29.38   29.58   29.58   29.78   29.99   30.11
   30.15   30.12      30   29.81    29.5    29.5   29.45    29.1   29.31      30
      30
                                              24   29.28   29.48   29.69   29.81
   29.85   29.82    29.7   29.51    29.2      24
        
BR Coef=-1 , 0 , 0 ,, 0 ,,,0.8,-1,,0,
WSPro=,,,, 1 ,,,, 0 ,,,, 0 ,,,,-1 ,-1 ,-1 , 0 , 0 , 0 , 0 , 0
BC Design=,, 0 ,, 0 ,,,,,,
BC Use User HTab Curves=0
BC User HTab FreeFlow(D)= 0

Type RM Length L Ch R = 1 ,2114.73 ,32.9,34.11,35.58
Node Photo=..\..\..\Corner Brook\Windshield Survey\CB photos\P1000663.JPG
XS GIS Cut Line= 5
      345930.691     5423010.476       346024.48     5423009.128
      346021.044     5423023.831      346061.201     5423062.699
      346093.589     5423089.982
#Sta/Elev= 26
       0      35   10.61      34   26.65      33   38.94      32   57.39      31
  100.45      30  111.51   29.27  114.49   29.41  118.56   29.38  120.99      29
  125.06      28  126.88      27  129.09      26  131.84      25  143.52   24.04
  144.57   24.53  146.42      25  148.87      26  151.63      27  153.38      28
  156.13   28.73  158.46      29  181.25   30.48  189.63    32.2  190.86   32.34
  207.13    32.5
#Mann= 3 , 0 , 0
       0    .055       0  131.84    .035       0  146.42    .055       0
#XS Ineff= 2 , 0
       0  124.11      29  158.75       0      29
Permanent Ineff=
       F       F
Bank Sta=131.84,146.42
XS Rating Curve= 0 ,0
Exp/Cntr=0.4,0.2

Type RM Length L Ch R = 1 ,2080.62 ,7.82,12.17,17.26
XS GIS Cut Line= 6
      345930.185     5423010.828      346011.495     5423009.672
      346011.251     5423027.508      346009.591     5423057.665
      346035.995      5423087.37      346032.374     5423105.315
#Sta/Elev= 28
       0      35   10.31      34   26.33      33   38.62      32   55.87      31
    82.7      30   91.97   29.28   98.25   28.15   106.3   27.96  111.46   27.32
   116.1   25.96  128.59   25.83  129.56   25.97  132.41   26.17  140.04   24.23
   141.3   24.11   151.7   24.03  153.95   24.03  156.53   24.33  157.34   24.43
   159.1   24.84  163.18   28.37  166.91   29.45  169.37   30.02  170.31   30.36
  179.58   34.57  182.68   35.31  187.42   36.97
#Mann= 3 , 0 , 0
       0    .055       0  140.04    .035       0  156.53    .055       0
Bank Sta=140.04,156.53
XS Rating Curve= 0 ,0
Exp/Cntr=0.3,0.1

Type RM Length L Ch R = 1 ,2068.44 ,33.61,46.19,57.27
XS GIS Cut Line= 3
345989.7929077155423013.86950684345994.8095092775423035.04589844
346022.6514892585423105.56347656
#Sta/Elev= 22
       0   30.53   13.37   28.31   17.52   27.86   19.34   27.53   21.14    27.5
   21.76   27.43   33.72   26.19   35.17   25.76   41.34   25.74   43.75   26.01
   50.02   26.39   57.22   24.24   57.73   24.06    58.7   24.07   60.17   24.06
   74.74   23.98   77.71   24.56   79.48   24.91   84.28   26.35   91.74   31.93
   94.27   34.35   97.58   37.01
#Mann= 3 , 0 , 0
       0    .055       0   60.17    .035       0   77.71    .055       0
Bank Sta=60.17,77.71
XS Rating Curve= 0 ,0
Exp/Cntr=0.3,0.1

Type RM Length L Ch R = 1 ,2022.25 ,34.56,31.11,28.31
XS GIS Cut Line= 3
345989.0667114265423013.80352783 345989.132690435423031.48352051
345953.182128906 5423102.3637085
#Sta/Elev= 22
       0   30.55   15.18   27.99   17.68    27.7   19.31   27.51   21.32    27.3
   29.82   26.35   41.38   25.14   44.34   25.38   47.19    25.6   49.86   24.89
   56.52   23.15   57.83   23.15   64.14   23.13   73.19   23.14   74.41   23.49
   77.73   24.44   79.99   25.06    83.5   27.36   91.52   34.86   93.99   36.95
   95.31   38.09   97.16   38.95
#Mann= 3 , 0 , 0
       0    .055       0   57.83    .035       0   73.19    .055       0
Bank Sta=57.83,73.19
XS Rating Curve= 0 ,0
Exp/Cntr=0.3,0.1

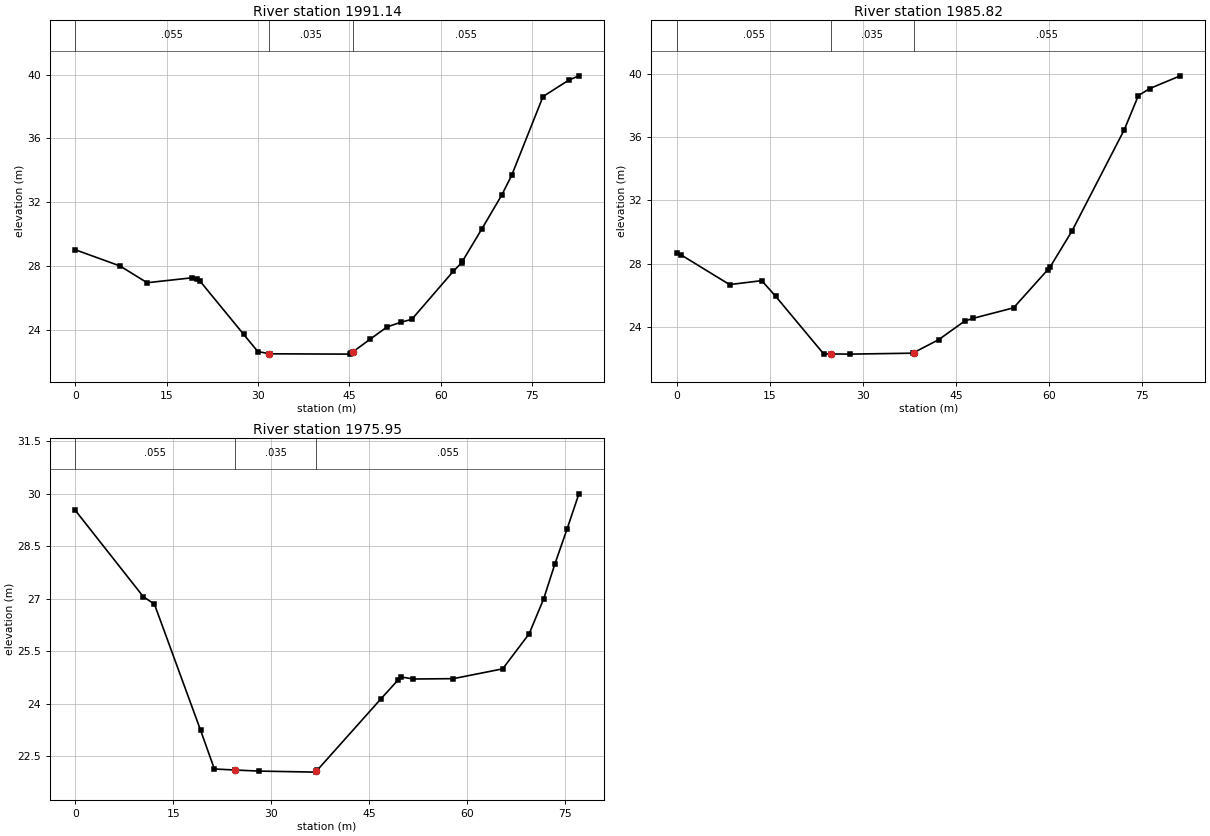
Type RM Length L Ch R = 1 ,1991.14 ,4.99,5.33,3.98
XS GIS Cut Line= 6
 345950.168090825423025.80169678345943.0416870125423044.42907715
345942.630493164 5423052.0993042 345935.503906255423071.68548584
345933.8593139655423076.47930908345943.4526977545423104.00952148
#Sta/Elev= 26
       0   29.01    7.36   27.99    11.8   26.94    19.2   27.25   19.94   27.15
   20.51   27.03   27.63   23.71   29.98   22.62   31.83   22.49   31.94   22.48
   45.08   22.46   45.34   22.54   45.58    22.6   48.47   23.41   51.21   24.17
   53.54   24.47   55.25   24.64    62.1   27.67   63.45    28.2   63.58   28.29
   66.78   30.33   70.04   32.45   71.67   33.69    76.8   38.62   81.03   39.65
   82.69   39.92
#Mann= 3 , 0 , 0
       0    .055       0   31.83    .035       0   45.58    .055       0
Bank Sta=31.83,45.58
XS Rating Curve= 0 ,0
Exp/Cntr=0.3,0.1

Type RM Length L Ch R = 1 ,1985.82 ,9.55,9.86,16.12
XS GIS Cut Line= 3
345943.615112305 5423029.6887207345929.5490722665423075.29351807
345939.5516967775423107.15447998
#Sta/Elev= 21
       0   28.66     .72   28.55    8.54   26.67   13.72   26.92   15.98   25.92
    23.7   22.28   24.86   22.28   27.92   22.27   38.04   22.33   38.17   22.36
    42.2   23.18   46.39   24.36   47.72   24.53   54.28    25.2   59.76    27.6
   60.16   27.78    63.7   30.07   72.11   36.47   74.38   38.63   76.18   39.07
   81.12   39.88
#Mann= 3 , 0 , 0
       0    .055       0   24.86    .035       0   38.17    .055       0
Bank Sta=24.86,38.17
XS Rating Curve= 0 ,0
Exp/Cntr=0.3,0.1

Type RM Length L Ch R = 1 ,1975.95 ,52.27,46.23,29.18
XS GIS Cut Line= 4
      345935.646     5423026.368      345916.273     5423080.885
      345922.939     5423084.477      345929.488     5423094.137
#Sta/Elev= 21
       0   29.53   10.43   27.06   12.12   26.85    19.2   23.24    21.3   22.14
   24.49   22.11   28.08   22.08    36.8   22.05   36.89   22.07   37.07   22.11
   46.78   24.14   49.41   24.68   49.86   24.77   51.74   24.71   57.86   24.72
   65.43      25   69.48      26   71.71      27   73.43      28    75.3      29
    77.1      30
#Mann= 3 , 0 , 0
       0    .055       0   24.49    .035       0   36.89    .055       0
Bank Sta=24.49,36.89
XS Rating Curve= 0 ,0
Exp/Cntr=0.3,0.1