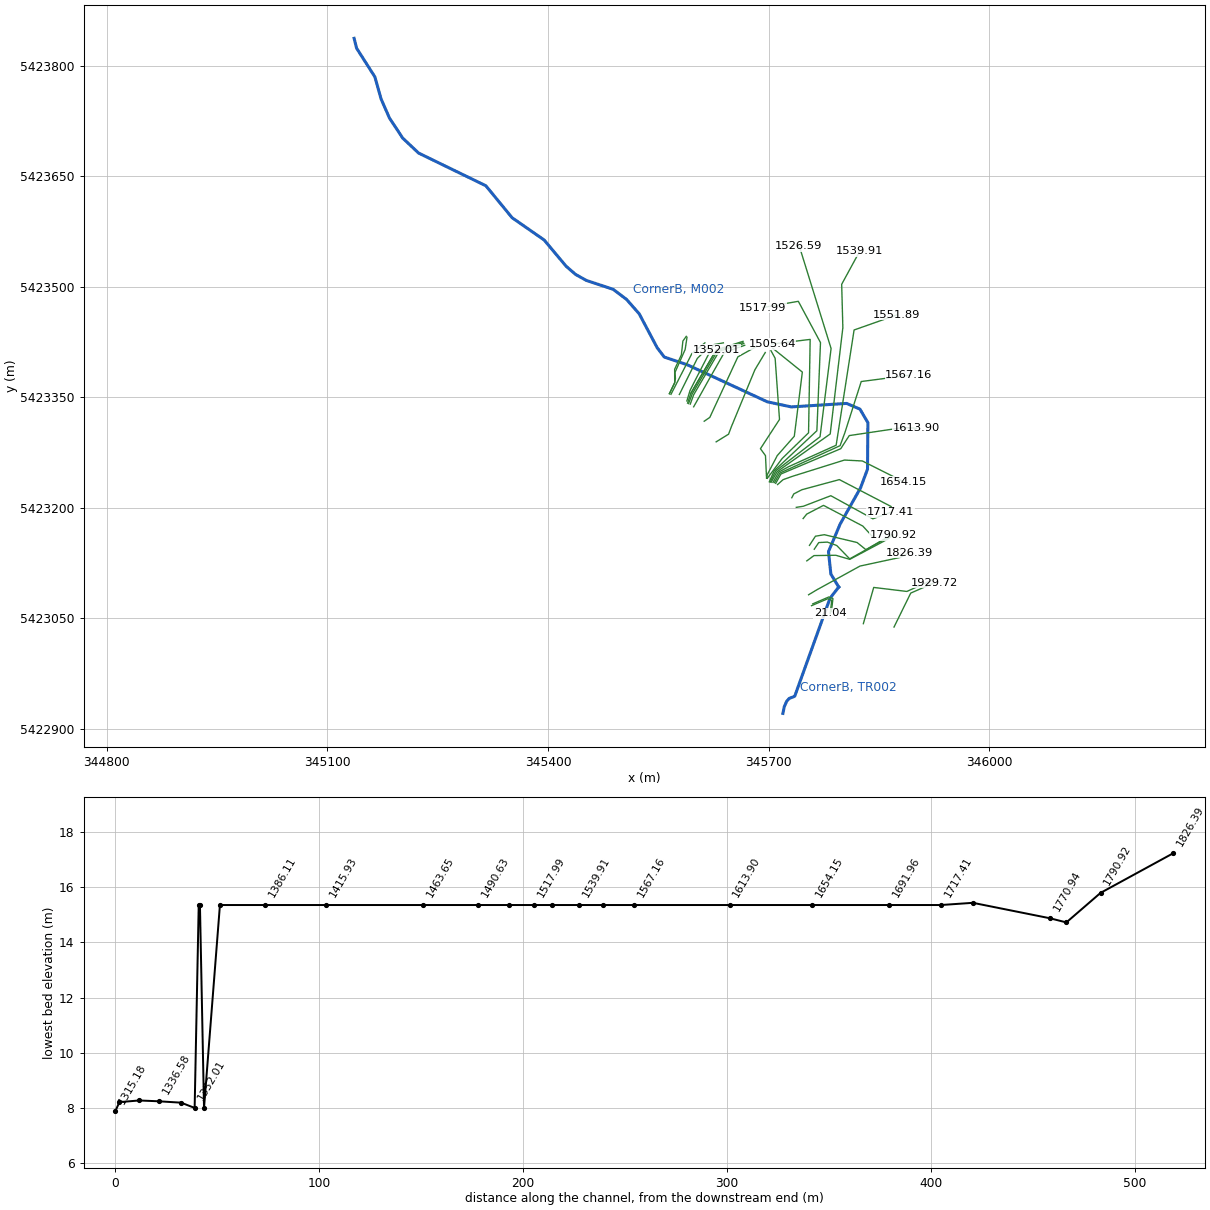
HEC-RAS study Corner_Brook2.prj: Corner_Brook2

--- Corner_Brook2.g01 (geometry) --- (continued)

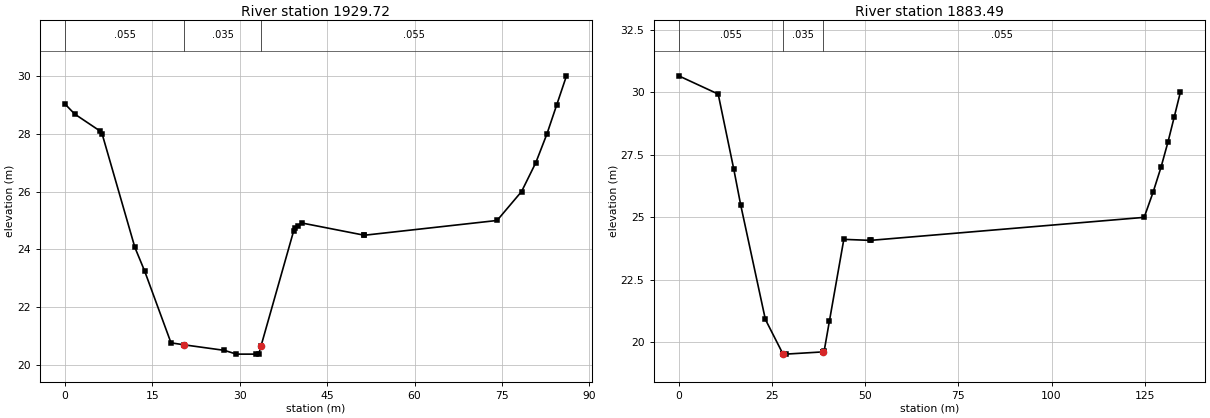
Type RM Length L Ch R = 1 ,1929.72 ,44.45,46.23,49.08
XS GIS Cut Line= 3
      345870.248     5423037.994      345892.961      5423084.11
      345924.694     5423098.062
#Sta/Elev= 25
       0   29.03    1.68   28.68    6.05   28.09    6.41   27.98   12.01   24.07
   13.69   23.25   18.21   20.77   20.52    20.7   27.37   20.51   29.43   20.38
   32.75   20.38   33.26   20.38   33.66  20.664   39.27   24.65   39.41   24.74
   39.92   24.81   40.73   24.91   51.38   24.49   51.41   24.49   74.16      25
   78.36      26   80.81      27   82.73      28    84.4      29   86.07      30
#Mann= 3 , 0 , 0
       0    .055       0   20.52    .035       0   33.66    .055       0
Bank Sta=20.52,33.66
XS Rating Curve= 0 ,0
Exp/Cntr=0.3,0.1

Type RM Length L Ch R = 1 ,1883.49 ,70.29,57.09,46.34
XS GIS Cut Line= 5
      345828.559     5423042.591      345831.718      5423053.53
      345842.662     5423091.804       345887.72     5423086.365
      345922.318     5423102.044
#Sta/Elev= 22
       0   30.66   10.59   29.93   14.78   26.92   16.62    25.5   23.24   20.92
   27.95   19.54   27.98   19.53   28.02   19.53   28.69   19.53   38.76   19.62
   38.82   19.63   39.01   19.65   40.41   20.84   44.29   24.12   51.24   24.08
   51.49   24.08  124.86      25  127.24      26  129.37      27  131.22      28
   132.9      29  134.56      30
#Mann= 3 , 0 , 0
       0    .055       0   28.02    .035       0   38.82    .055       0
Bank Sta=28.02,38.82
XS Rating Curve= 0 ,0
Exp/Cntr=0.3,0.1

River Reach=CornerB         ,TR002
Reach XY= 9
345719.2092895515422920.77648926345721.0733032235422929.76287842
345724.3626708985422937.21508789345727.7899169925422941.09490967
345733.6691284185422943.30712891345735.3291015635422944.13690186
345782.7587280275423075.71228027345785.974121094 5423080.6439209
 345795.121093755423092.33508301

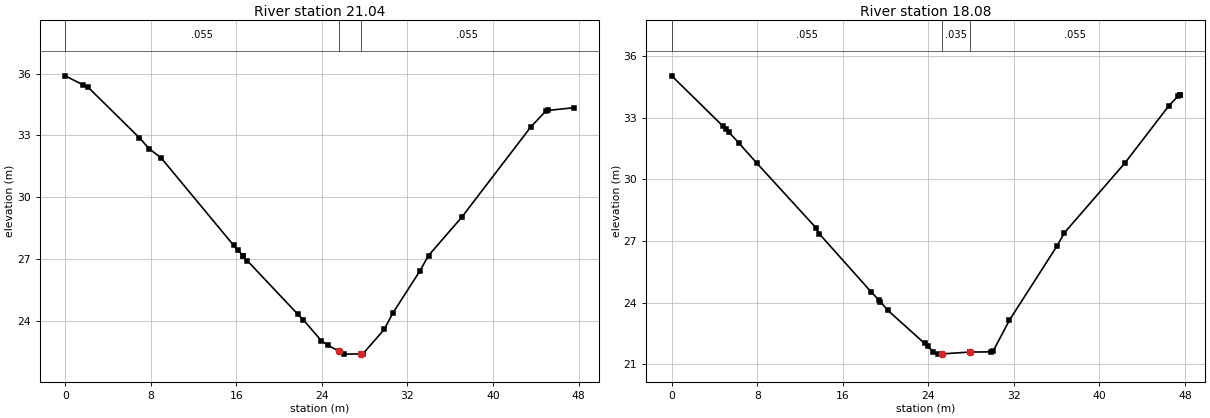
Type RM Length L Ch R = 1 ,21.04   ,2.92,2.96,3.06
XS GIS Cut Line= 4
345758.1389160165423067.02331543345780.1409301765423076.43328857
345785.6174926765423074.22491455345783.5037231455423056.65307617
#Sta/Elev= 28
       0   35.89    1.67   35.45    2.13   35.34    6.94   32.88    7.85   32.35
    8.99   31.89   15.74   27.66   16.15   27.42   16.61   27.16   16.63   27.14
   17.04    26.9   21.76    24.3   22.28   24.03   23.93   23.03   24.53   22.81
   25.64    22.5   26.07   22.37   27.64   22.38   27.83   22.38   29.83   23.57
   30.62   24.35   33.15    26.4   33.97   27.16   37.06   29.01   43.54   33.41
   44.94   34.18   45.17   34.21   47.53   34.34
#Mann= 3 , 0 , 0
       0    .055       0   25.64    .035       0   27.64    .055       0
Bank Sta=25.64,27.64
XS Rating Curve= 0 ,0
Exp/Cntr=0.3,0.1

Type RM Length L Ch R = 1 ,18.08   ,6.77,18.08,0.34
XS GIS Cut Line= 4
345759.7786865235423069.50152588345781.7808837895423078.91149902
345787.257324219  5423076.703125345785.1434936525423059.13110352
#Sta/Elev= 29
       0   35.03    4.82   32.57    5.09   32.46    5.33    32.3    6.25   31.78
    7.98   30.77   13.47   27.65   13.79   27.35   18.63   24.53   19.41    24.1
    19.5   24.05   20.19   23.63   23.65   22.01   23.93   21.87   24.47   21.61
   24.86   21.49   25.24    21.5   27.86   21.59   27.91   21.59   29.83    21.6
   30.08   21.66   31.58   23.14   36.04   26.76   36.73    27.4   42.35   30.77
   46.47   33.56   47.36   34.05    47.5   34.08   47.53   34.08
#Mann= 3 , 0 , 0
       0    .055       0   25.24    .035       0   27.91    .055       0
Bank Sta=25.24,27.91
XS Rating Curve= 0 ,0
Exp/Cntr=0.3,0.1

River Reach=CornerB         ,M002
Reach XY= 30
 345795.121093755423092.33508301345784.4091186525423109.94171143
345781.1890869145423140.42089844345797.1063232425423178.01727295
 345824.759704595423227.04888916345834.2301025395423252.41668701
345834.7415161135423315.57470703345823.9451293955423333.93792725
345805.7623291025423341.69970703345730.5678710945423336.96691895
345698.1629028325423343.85968018345589.332519531 5423394.1585083
345558.0211181645423404.66192627345548.3703002935423417.30889893
345523.9216918955423463.39508057345506.7647094735423482.90130615
345488.5355224615423496.61987305345451.9880981455423508.76208496
345437.404724121 5423516.9074707 345424.536926275423528.05389404
 345394.726684575423563.63671875345351.1911010745423593.86071777
345315.5029296885423637.28607178345224.142089844 5423681.6574707
345202.4815063485423702.02111816345184.4268798835423729.34588623
 345173.060485845423755.28271484345164.6962890635423785.07788086
345139.8189086915423824.09051514345136.4133300785423837.49328613

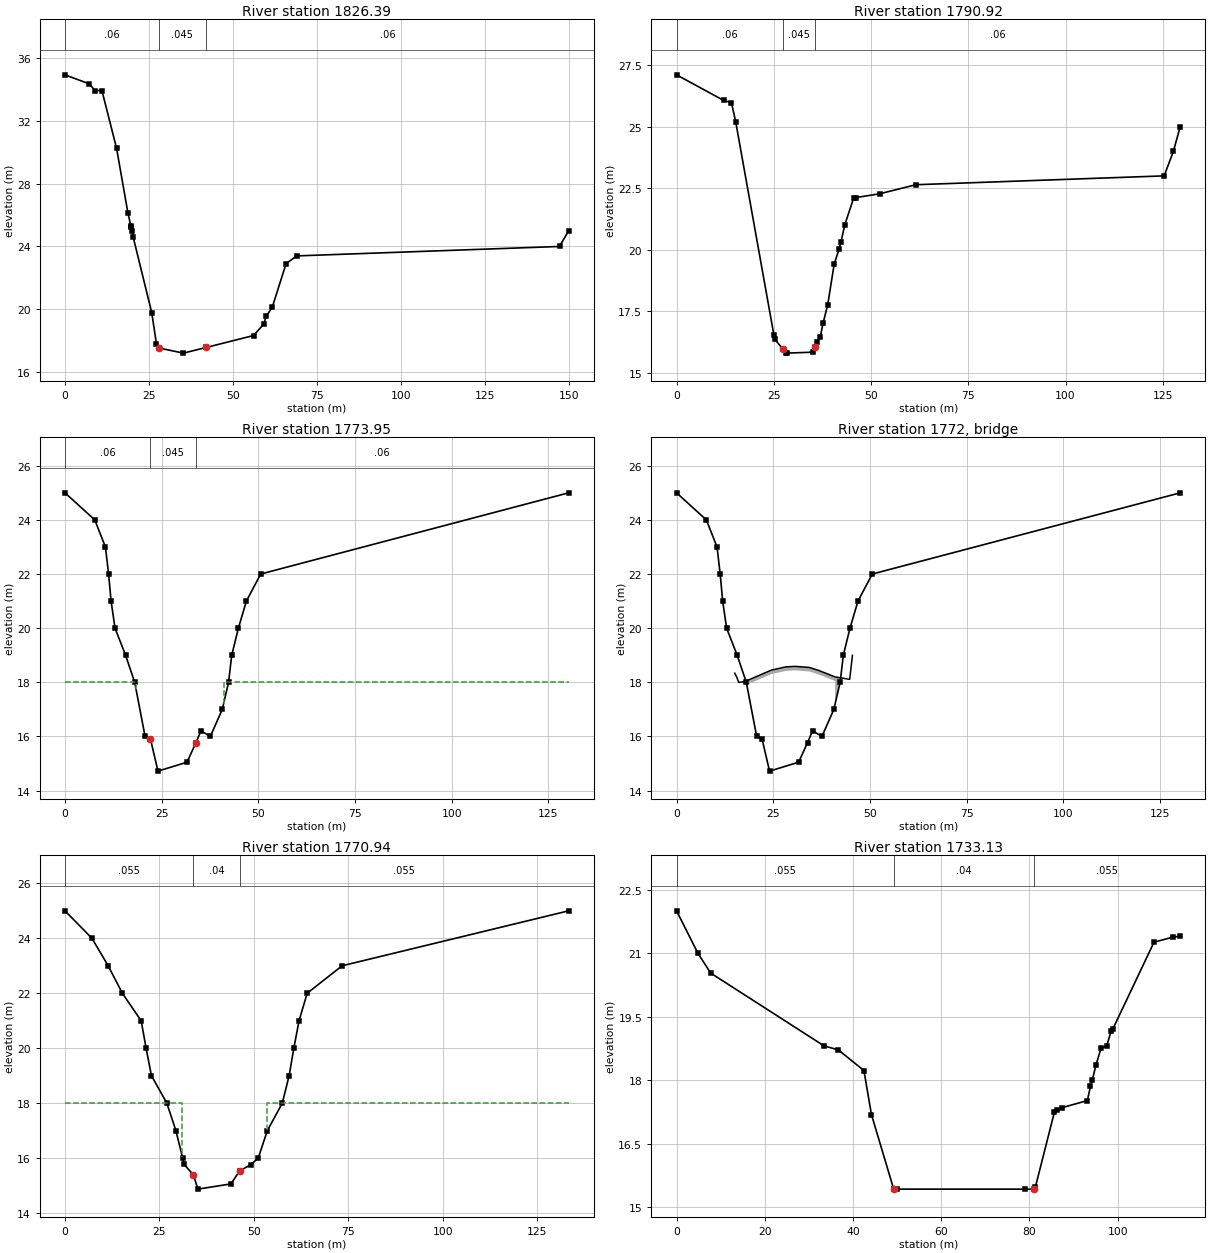
Type RM Length L Ch R = 1 ,1826.39 ,40.26,35.47,34.01
XS GIS Cut Line= 5
      345754.172     5423081.877      345765.677     5423088.757
      345824.044     5423120.836      345878.652     5423132.582
      345891.045     5423139.228
#Sta/Elev= 23
       0   34.91    7.29   34.33    8.92   33.91      11   33.91   15.37   30.23
   18.72   26.15   19.64   25.28   19.75   25.24    19.9      25   20.32   24.58
   25.82    19.8   27.23   17.81   27.87   17.55   35.24   17.22   42.03   17.58
   56.14   18.34   59.14   19.06   59.88   19.55   61.69   20.13   65.82   22.91
   68.98    23.4  147.23      24  149.93      25
#Mann= 3 , 0 , 0
       0     .06       0   27.87    .045       0   42.03     .06       0
Bank Sta=27.87,42.03
XS Rating Curve= 0 ,0
Exp/Cntr=0.3,0.1

Type RM Length L Ch R = 1 ,1790.92 ,18.6,16.77,13.53
XS GIS Cut Line= 6
      345751.702     5423127.865      345761.429     5423135.042
      345791.135     5423135.505      345810.069     5423129.948
      345861.119     5423157.051      345869.281     5423163.092
#Sta/Elev= 26
       0   27.11   12.09   26.07    14.1   25.98   15.19   25.21   25.04   16.51
   25.21   16.36   27.26   15.97   28.14    15.8   28.35   15.79   35.18   15.83
   35.63   16.02   36.21   16.26   36.94   16.45   37.68   17.02   38.86   17.76
   40.51    19.4    41.8   20.04   42.27   20.32   43.25   21.01    45.5   22.09
   46.19   22.12   52.19   22.27   61.53   22.64  125.35      23  127.72      24
  129.48      25
#Mann= 3 , 0 , 0
       0     .06       0   27.26    .045       0   35.63     .06       0
Bank Sta=27.26,35.63
XS Rating Curve= 0 ,0
Exp/Cntr=0.3,0.1

Type RM Length L Ch R = 1 ,1773.95 ,9.46,8.02,9.37
Node Photo=..\..\..\Corner Brook\Windshield Survey\CB photos\P1000661.JPG
XS GIS Cut Line= 6
      345761.829     5423143.685      345767.933     5423152.725
      345779.693     5423153.364      345792.387     5423148.747
      345810.052     5423130.611      345868.647     5423163.341
#Sta/Elev= 22
       0      25     7.7      24   10.46      23   11.28      22   11.92      21
   12.94      20   15.67      19   18.03      18   20.71      16   22.11    15.9
   24.04   14.72   31.56   15.05   33.85   15.77   35.16   16.21   37.58      16
   40.66      17   42.29      18   43.11      19   44.83      20    46.9      21
   50.59      22  130.21      25
#Mann= 3 , 0 , 0
       0     .06       0   22.11    .045       0   33.85     .06       0
#XS Ineff= 2 , 0
       0   18.47      18   40.99       0      18
Permanent Ineff=
       F       F
Bank Sta=22.11,33.85
XS Rating Curve= 0 ,0
Exp/Cntr=0.5,0.3

Type RM Length L Ch R = 3 ,1772    ,,,
Node Photo=..\..\..\Corner Brook\Windshield Survey\CB photos\P1000658.JPG
BEGIN DESCRIPTION:
Pedestrian Bridge u/s of Glynmill Dam (Structure #2109)
END DESCRIPTION:
Bridge Culvert--1,0,-1,-1, 0
Deck Dist Width WeirC Skew NumUp NumDn MinLoCord MaxHiCord MaxSubmerge Is_Ogee
3.78,1.76,1.67,0, 15, 17, 18, , 0.98, 0, 0,0,,
   15.03    15.5   16.08   18.14   18.47   18.48   24.47    28.2   30.64   34.33
   36.74   40.98   40.99   44.76   45.47
   18.34   18.21      18   18.03   18.08   18.08   18.45   18.57   18.59   18.55
   18.44    18.2    18.2   18.11      19
                                      14   17.93    18.3   18.42   18.44    18.4
   18.29   18.05      14
   25.64    27.4   30.55   31.05   31.06   33.12   36.83   40.49    42.9    46.5
   48.95   53.56   53.57   56.67   57.54   59.32   60.56
   18.32   18.21   18.03   18.03   18.03   18.23   18.47   18.59   18.61   18.54
   18.43   18.21   18.21      18   18.06      19      20
                              14   17.88   18.08   18.32   18.44   18.46   18.39
   18.28   18.06      14
BR Coef=-1 , 0 , 0 ,, 0 ,,,0.8,-1,,0,
WSPro=,,,, 1 ,,,, 0 ,,,, 0 ,,,,-1 ,-1 ,-1 , 0 , 0 , 0 , 0 , 0
BC Design=,, 0 ,, 0 ,,,,,,
BC Use User HTab Curves=0
BC User HTab FreeFlow(D)= 0

Type RM Length L Ch R = 1 ,1770.94 ,40.38,37.81,37.86
Node Photo=..\..\..\Corner Brook\Windshield Survey\CB photos\P1000659.JPG
XS GIS Cut Line= 6
      345755.322     5423148.956      345763.458     5423161.361
      345775.461     5423163.425      345820.082       5423152.8
      345832.069      5423143.08      345867.894      5423163.82
#Sta/Elev= 25
       0      25    7.14      24   11.43      23   15.18      22   20.16      21
   21.47      20   22.88      19   26.95      18   29.35      17   31.15      16
   31.54   15.77   33.97   15.39   35.18   14.87    43.9   15.06   46.22   15.53
   49.16   15.76   51.14      16   53.55      17   57.51      18   59.32      19
   60.56      20   61.94      21   64.09      22   73.34      23  133.28      25
#Mann= 3 , 0 , 0
       0    .055       0   33.97     .04       0   46.22    .055       0
#XS Ineff= 2 , 0
       0   31.05      18   53.57       0      18
Permanent Ineff=
       F       F
Bank Sta=33.97,46.22
XS Rating Curve= 0 ,0
Exp/Cntr=0.5,0.3

Type RM Length L Ch R = 1 ,1733.13 ,16.21,15.72,15.8
XS GIS Cut Line= 5
      345746.741     5423185.349       345751.59     5423191.382
      345774.408     5423203.252      345827.859     5423175.139
      345841.612     5423160.146
#Sta/Elev= 27
       0      22    4.83      21    7.74   20.53   33.46   18.81   36.64   18.72
   42.48   18.23   44.19   17.19   49.23   15.43   49.39   15.43   49.87   15.43
    78.9   15.43   81.07   15.43   81.36   15.48   85.65   17.24    86.3    17.3
   87.28   17.35   93.14   17.52   93.85   17.86   94.25      18   95.09   18.36
   96.23   18.75   97.52   18.81   98.53   19.16   98.87    19.2  108.26   21.26
  112.57   21.38   114.2    21.4
#Mann= 3 , 0 , 0
       0    .055       0   49.23     .04       0   81.07    .055       0
Bank Sta=49.23,81.07
XS Rating Curve= 0 ,0
Exp/Cntr=0.3,0.1

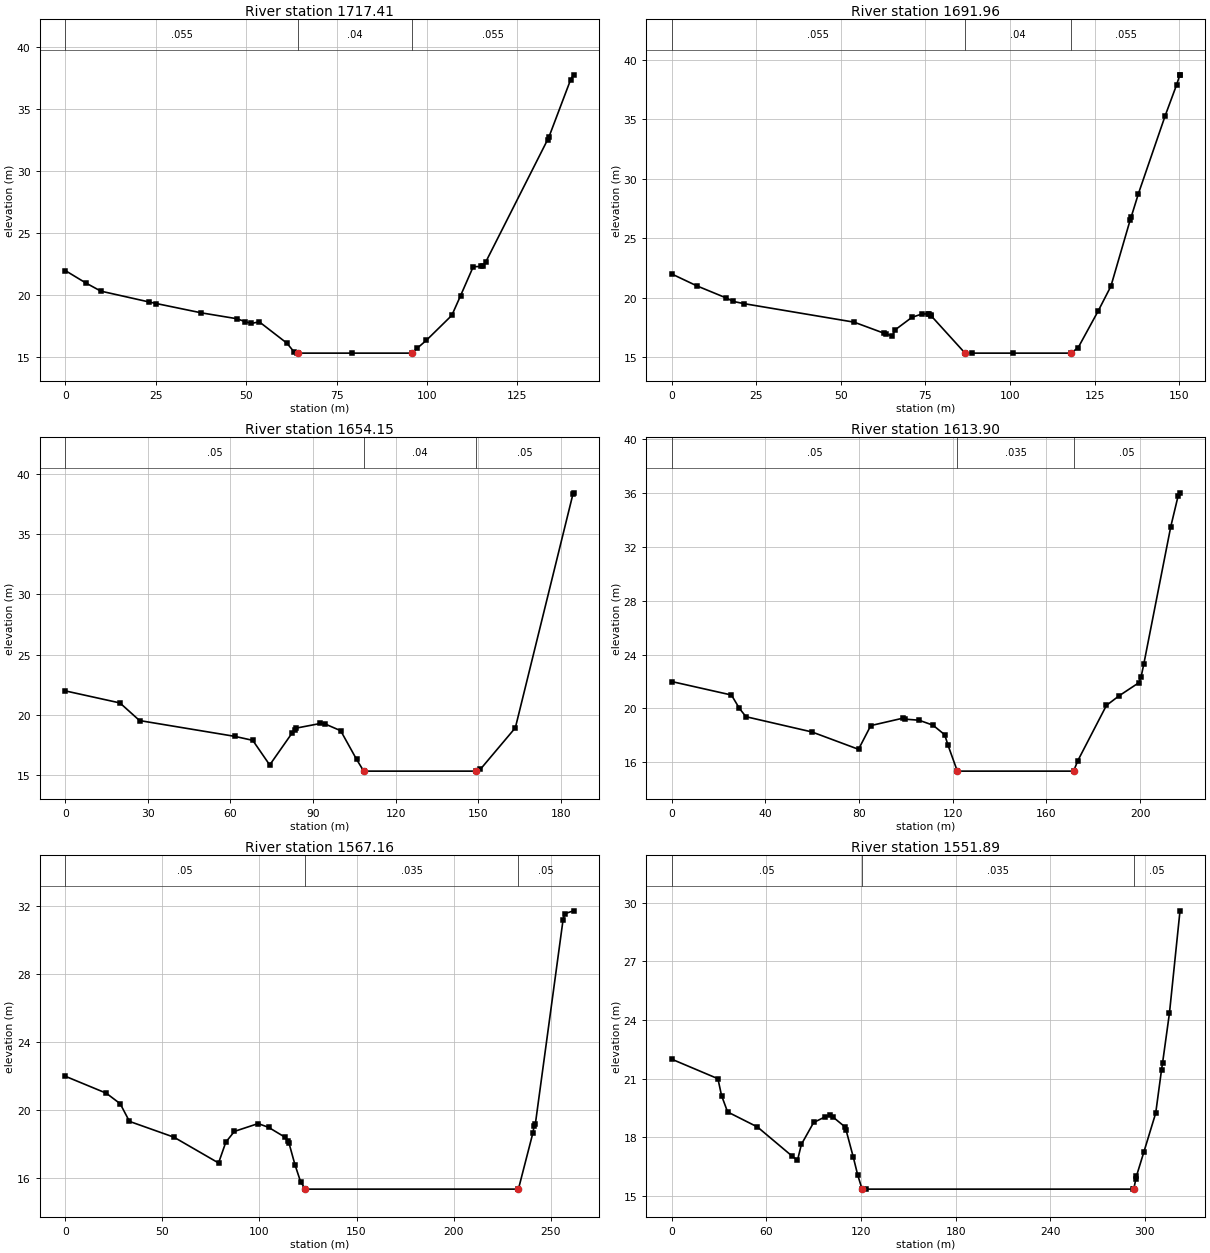
Type RM Length L Ch R = 1 ,1717.41 ,25.46,25.45,26.11
XS GIS Cut Line= 5
      345737.376      5423200.53      345747.104      5423202.08
      345784.369     5423216.364      345841.542     5423184.989
      345865.534     5423193.662
#Sta/Elev= 28
       0      22    5.68      21    9.85   20.34   23.29   19.46    25.2   19.34
   37.66   18.59   47.43   18.12   49.76   17.88   51.48   17.74   53.63   17.87
   61.28   16.15   63.35   15.41   64.06   15.35   64.26   15.35   79.34   15.35
   95.77   15.35   97.27   15.74   99.85   16.39  106.85   18.39  109.25   19.96
  112.76    22.3  114.98   22.33  115.37   22.33  116.22   22.68  133.31   32.52
  133.71   32.76  139.66   37.34  140.49   37.75
#Mann= 3 , 0 , 0
       0    .055       0   64.26     .04       0   95.77    .055       0
Bank Sta=64.26,95.77
XS Rating Curve= 0 ,0
Exp/Cntr=0.3,0.1

Type RM Length L Ch R = 1 ,1691.96 ,32.19,37.81,37.44
XS GIS Cut Line= 5
      345731.341     5423213.631      345734.047      5423218.83
      345745.026     5423224.492      345795.976     5423238.237
      345866.305      5423201.69
#Sta/Elev= 30
       0      22    7.43      21   15.98      20   18.21   19.69   21.48    19.5
   53.93   17.95   62.77   17.02   63.44   16.97   65.14   16.78   66.12   17.32
   70.98   18.35   73.88   18.63   75.68   18.65    76.1   18.63   76.53   18.55
   76.77   18.46   86.71   15.35   88.69   15.35  100.99   15.35  117.99   15.35
  120.14   15.81  126.06   18.89  129.82   20.97   135.5   26.52   135.8   26.77
  137.95   28.74  145.88    35.3  149.21   37.86  150.21   38.72  150.24   38.72
#Mann= 3 , 0 , 0
       0    .055       0   86.71     .04       0  117.99    .055       0
Bank Sta=86.71,117.99
XS Rating Curve= 0 ,0
Exp/Cntr=0.3,0.1

Type RM Length L Ch R = 1 ,1654.15 ,26.43,40.25,54.75
XS GIS Cut Line= 6
      345711.988     5423231.515       345719.48      5423238.17
      345731.897     5423242.609      345802.852     5423264.787
      345827.233     5423263.538      345883.185     5423235.425
#Sta/Elev= 19
       0      22   19.87      21      27   19.54    61.6   18.23    68.1    17.9
   74.26   15.86   82.52   18.55   83.58   18.79   83.79   18.91   92.69    19.3
   94.23   19.27  100.02    18.7  105.81   16.32   108.4   15.35  149.16   15.35
  150.78   15.51  163.45   18.94  184.39   38.33  184.58   38.41
#Mann= 3 , 0 , 0
       0     .05       0   108.4     .04       0  149.16     .05       0
Bank Sta=108.4,149.16
XS Rating Curve= 0 ,0
Exp/Cntr=0.3,0.1

Type RM Length L Ch R = 1 ,1613.90 ,6.28,46.75,75.1
XS GIS Cut Line= 6
      345709.491     5423233.179      345716.566     5423245.864
      345797.852     5423280.216      345809.417     5423298.021
      345882.872     5423308.954      345901.002     5423308.017
#Sta/Elev= 24
       0      22   25.51      21   28.94      20   31.72   19.39   59.84   18.26
   79.77   16.97      85   18.73    98.7   19.28    99.5   19.21   105.6   19.13
  111.57   18.76  116.56   18.05     118   17.26  121.95   15.35  171.58   15.35
  173.37   16.12  185.61   20.23     191   20.94  199.51   21.92  200.42   22.36
  201.59   23.33  213.08   33.51  216.25   35.81  217.01   36.01
#Mann= 3 , 0 , 0
       0     .05       0  121.95    .035       0  171.58     .05       0
Bank Sta=121.95,171.58
XS Rating Curve= 0 ,0
Exp/Cntr=0.3,0.1

Type RM Length L Ch R = 1 ,1567.16 ,8.5,15.27,80.02
XS GIS Cut Line= 6
      345707.826     5423234.219       345715.11     5423247.112
      345796.942     5423284.288      345803.506     5423302.093
      345825.699     5423371.437      345890.402     5423379.871
#Sta/Elev= 23
       0      22   21.14      21   28.31   20.38   33.07   19.34   55.97   18.41
   78.96   16.89   82.71   18.12   87.13   18.75   99.33   19.21  104.69   18.99
  113.13   18.41  114.66    18.2  115.15   18.09  118.29   16.79  121.24   15.77
  123.67   15.35  233.35   15.35  240.76   18.64   241.4   19.04   242.1   19.21
  256.35   31.22  257.21   31.57  261.73   31.74
#Mann= 3 , 0 , 0
       0     .05       0  123.67    .035       0  233.35     .05       0
Bank Sta=123.67,233.35
XS Rating Curve= 0 ,0
Exp/Cntr=0.3,0.1

Type RM Length L Ch R = 1 ,1551.89 ,13.15,11.97,90.06
XS GIS Cut Line= 6
      345705.745     5423234.427      345713.445      5423248.36
      345727.212     5423255.882      345791.603     5423284.932
      345815.984     5423441.425      345874.115     5423461.906
#Sta/Elev= 28
       0      22   29.32      21   31.61   20.14   35.45    19.3   54.38   18.53
    76.5   17.03   79.77   16.83   82.24   17.64   90.01   18.76   97.09   19.04
  100.63   19.13  102.25   19.04  109.62   18.55  110.54   18.38   115.1      17
  117.95   16.07  120.71   15.35   123.2   15.35  292.43   15.35  292.96   15.35
  294.22   15.85  294.64   16.01  299.44   17.27  306.87   19.24  310.57   21.46
  311.19   21.79  315.59   24.36  322.27   29.59
#Mann= 3 , 0 , 0
       0     .05       0  120.71    .035       0  292.96     .05       0
Bank Sta=120.71,292.96
XS Rating Curve= 0 ,0
Exp/Cntr=0.3,0.1

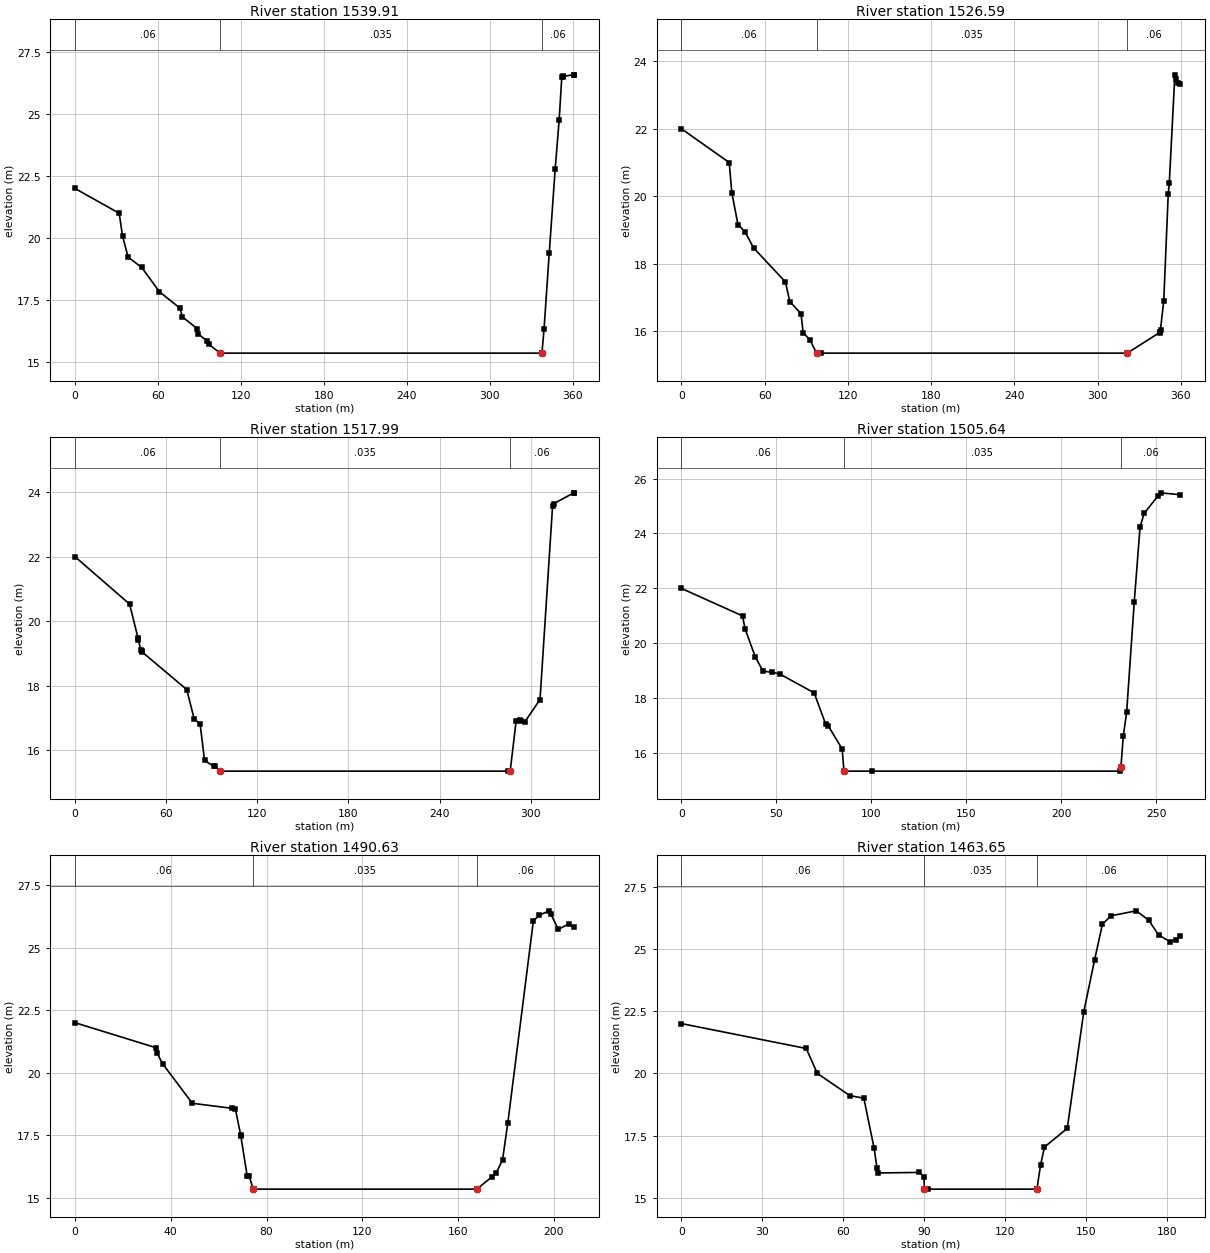
Type RM Length L Ch R = 1 ,1539.91 ,10.59,13.32,74.85
XS GIS Cut Line= 6
      345703.248     5423234.634      345711.364     5423248.984
      345783.516     5423300.208      345800.708      5423444.52
      345799.119     5423503.467      345823.812     5423548.759
#Sta/Elev= 26
       0      22   31.96      21   34.39   20.08   38.39   19.23   48.26   18.81
   61.04   17.83   75.82   17.17   77.71   16.81   88.41   16.34      89   16.13
   95.72   15.83   96.71   15.71  104.98   15.35  105.21   15.35  337.43   15.35
  337.56   15.35  337.69   15.35  339.18   16.31  342.97    19.4  347.23   22.77
  350.14   24.78  352.02   26.49  353.08    26.5   353.2   26.53  360.53   26.59
  360.86   26.59
#Mann= 3 , 0 , 0
       0     .06       0  104.98    .035       0  337.69     .06       0
Bank Sta=104.98,337.69
XS Rating Curve= 0 ,0
Exp/Cntr=0.3,0.1

Type RM Length L Ch R = 1 ,1526.59 ,11.14,8.6,95.57
XS GIS Cut Line= 6
      345701.999      5423235.05      345709.699     5423250.231
      345769.716     5423296.429      345784.723     5423416.258
      345742.212     5423553.073      345740.337     5423555.259
#Sta/Elev= 25
       0      22   34.44      21   36.29   20.11   40.73   19.16   45.79   18.95
   51.96   18.47   74.97   17.46   78.06   16.88   86.17   16.52    87.7   15.96
   92.79   15.73   97.37   15.35   97.63   15.35  100.58   15.35  321.32   15.35
  344.66   15.96  345.16   15.99  345.31   16.05  347.65    16.9  350.89   20.07
  351.64   20.39  355.65    23.6  356.82   23.48  357.97   23.36   359.7   23.33
#Mann= 3 , 0 , 0
       0     .06       0   97.37    .035       0  321.32     .06       0
Bank Sta=97.37,321.32
XS Rating Curve= 0 ,0
Exp/Cntr=0.3,0.1

Type RM Length L Ch R = 1 ,1517.99 ,8.97,12.35,53.09
XS GIS Cut Line= 6
      345700.751     5423235.258       345707.41     5423250.231
      345765.412     5423304.612      345770.316     5423424.349
      345740.189     5423480.365      345691.846     5423471.963
#Sta/Elev= 25
       0      22   35.92   20.53   41.42   19.49   41.78   19.41   43.27    19.1
    43.8   19.08   44.29   19.04   73.55   17.88   78.38   16.98   82.38    16.8
   85.26   15.68   91.31    15.5   92.02    15.5   95.71   15.35  284.92   15.35
  286.42   15.35  290.33   16.91  292.72   16.95  293.67   16.89  295.97   16.87
  306.05   17.57  314.29   23.56  314.92   23.64  328.31   23.98  328.41   23.98
#Mann= 3 , 0 , 0
       0     .06       0   95.71    .035       0  286.42     .06       0
Bank Sta=95.71,286.42
XS Rating Curve= 0 ,0
Exp/Cntr=0.3,0.1

Type RM Length L Ch R = 1 ,1505.64 ,15.22,15.01,28.16
XS GIS Cut Line= 6
      345698.045     5423240.041      345705.745     5423250.231
      345718.144     5423266.817      345754.091     5423301.802
      345756.279      5423428.62      345704.391     5423422.373
#Sta/Elev= 23
       0      22   32.17      21   33.48   20.53   38.81   19.52    42.9   18.99
   47.47   18.95   51.63   18.89   69.86    18.2   75.98   17.05   77.36   16.99
   84.64   16.15   85.54   15.35  100.45   15.35     231   15.35  231.39    15.5
  232.63   16.62  234.41    17.5  238.41   21.51  241.46   24.24  243.61   24.73
  250.92   25.37  252.26   25.48  262.74   25.41
#Mann= 3 , 0 , 0
       0     .06       0   85.54    .035       0  231.39     .06       0
Bank Sta=85.54,231.39
XS Rating Curve= 0 ,0
Exp/Cntr=0.3,0.1

Type RM Length L Ch R = 1 ,1490.63 ,32.16,26.98,34.14
XS GIS Cut Line= 6
      345697.629     5423240.041      345697.837     5423244.616
      345711.583     5423270.875      345734.714     5423297.114
      345745.654     5423384.263      345705.644     5423416.436
#Sta/Elev= 25
       0      22   33.86      21   34.22    20.8   36.59   20.36   49.01   18.78
    65.5   18.58   66.97   18.56    69.2   17.52   69.29   17.46    71.9   15.89
   72.74   15.88   74.43   15.35   74.57   15.35  167.82   15.35  174.19   15.84
  175.88   15.98  178.59   16.52   180.8      18  191.47   26.07  193.99    26.3
  198.13   26.47  198.72   26.35   201.9   25.73  206.22   25.94  208.44   25.82
#Mann= 3 , 0 , 0
       0     .06       0   74.43    .035       0  167.82     .06       0
Bank Sta=74.43,167.82
XS Rating Curve= 0 ,0
Exp/Cntr=0.3,0.1

Type RM Length L Ch R = 1 ,1463.65 ,55.26,47.71,36.96
XS GIS Cut Line= 6
      345697.005     5423240.041      345695.548     5423270.819
      345688.681     5423280.177      345714.601     5423319.919
      345708.662     5423403.008      345703.035     5423413.315
#Sta/Elev= 27
       0      22   46.26      21   50.35      20   62.35   19.11   67.61      19
   71.41   16.99   72.49   16.19   72.85      16    88.2   16.02   89.92   15.84
      90   15.35    91.5   15.35  131.62   15.35  131.74   15.35  133.11   16.32
  134.55   17.04     143   17.79   149.1   22.46  153.11   24.55  156.03   25.99
  159.19   26.33  168.58   26.53  173.22   26.15  176.86   25.56  181.09   25.29
  183.39   25.37  184.96    25.5
#Mann= 3 , 0 , 0
       0     .06       0      90    .035       0  131.74     .06       0
Bank Sta=90,131.74
XS Rating Curve= 0 ,0
Exp/Cntr=0.3,0.1

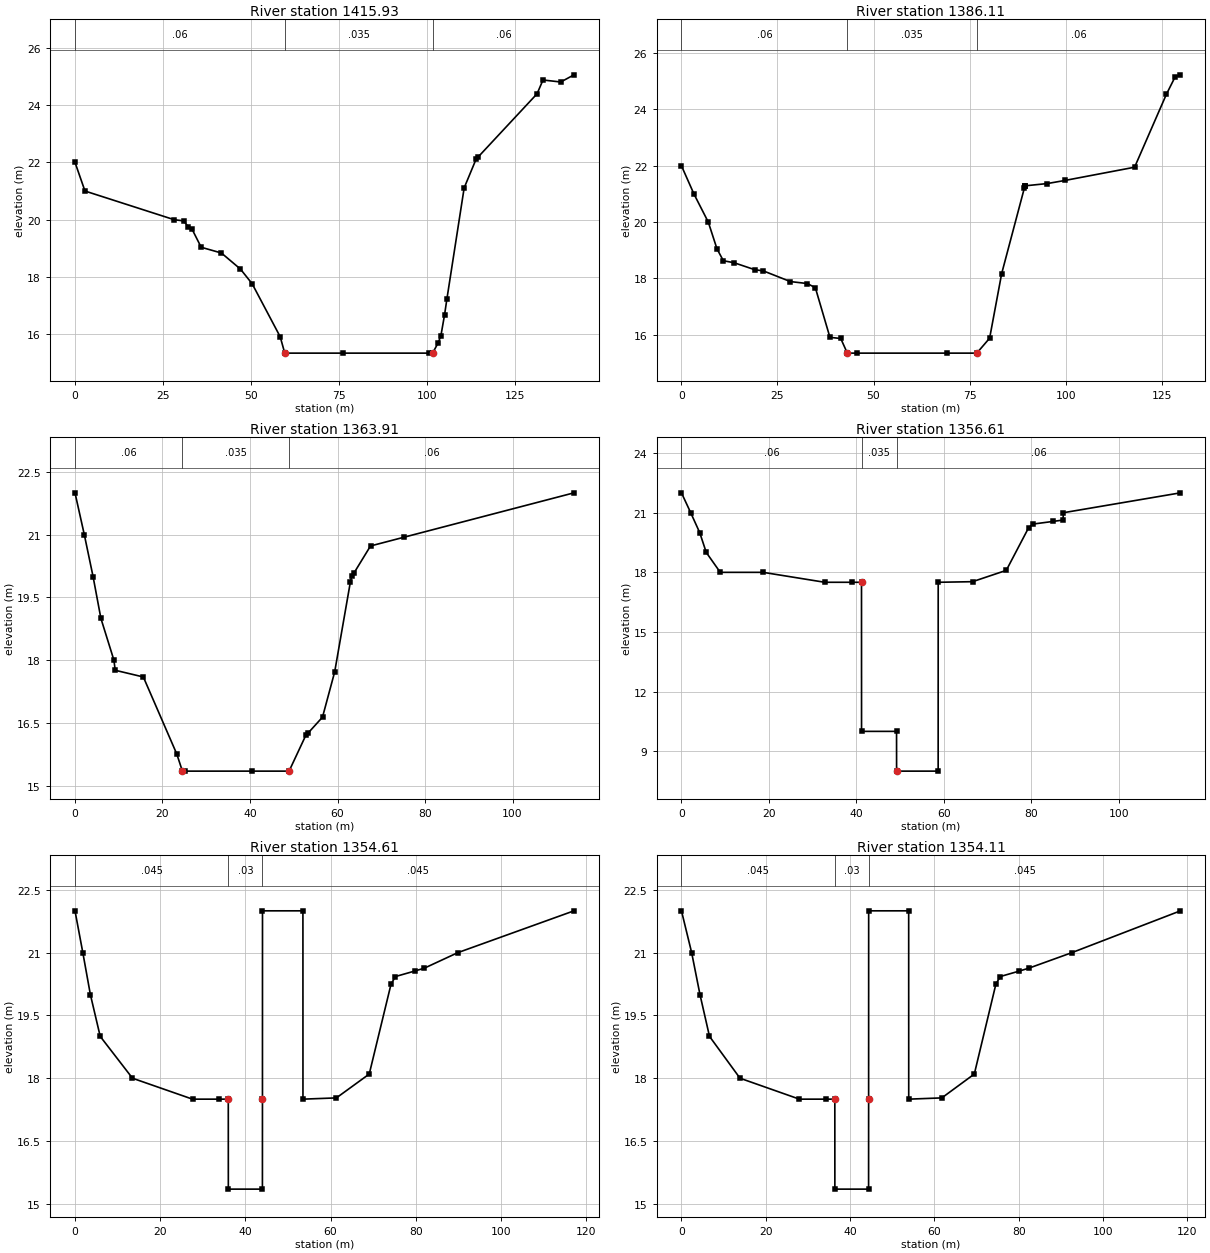
Type RM Length L Ch R = 1 ,1415.93 ,31.39,29.83,29.88
XS GIS Cut Line= 5
       345628.54     5423289.535      345645.396     5423299.933
      345649.272     5423310.236      345681.155      5423387.39
      345695.221     5423410.817
#Sta/Elev= 26
       0      22    2.83      21   28.16      20   30.81   19.96   32.11   19.76
   33.18   19.68   35.81   19.04   41.55   18.84   46.95   18.28   50.27   17.77
   58.24   15.92   59.53   15.35   76.16   15.35  100.57   15.35   101.5   15.35
  103.11   15.72  103.85   15.96  104.89   16.69  105.54   17.23  110.45   21.11
  113.83   22.11  114.29   22.17  131.14   24.39  132.82   24.87  137.86    24.8
  141.62   25.05
#Mann= 3 , 0 , 0
       0     .06       0   59.53    .035       0   101.5     .06       0
Bank Sta=59.53,101.5
XS Rating Curve= 0 ,0
Exp/Cntr=0.3,0.1

Type RM Length L Ch R = 1 ,1386.11 ,24.24,22.2,21.91
Node Photo=..\..\..\Corner Brook\Windshield Survey\CB photos\P1000657.JPG
XS GIS Cut Line= 4
      345612.263     5423317.512       345619.89     5423322.731
      345658.024     5423404.882      345684.281     5423419.563
#Sta/Elev= 29
       0      22    3.25      21    6.99      20    9.25   19.05   10.91   18.63
   13.67   18.56   19.12   18.31    21.3   18.27   28.36   17.89   32.79   17.82
   34.86   17.67   38.65   15.91   41.46   15.87   43.18   15.35   45.61   15.35
   69.11   15.35   76.88   15.35   80.22   15.88   83.35   18.17   89.26   21.21
   89.37   21.28    89.5   21.29   89.51   21.29   95.23   21.37   99.82   21.48
  117.96   21.95  126.24   24.54  128.52   25.16   129.9   25.23
#Mann= 3 , 0 , 0
       0     .06       0   43.18    .035       0   76.88     .06       0
Bank Sta=43.18,76.88
XS Rating Curve= 0 ,0
Exp/Cntr=0.3,0.1

Type RM Length L Ch R = 1 ,1363.91 ,8.1,7.8,10.76
Node Photo=..\..\..\Corner Brook\Windshield Survey\CB photos\P1000652.JPG
XS GIS Cut Line= 5
       345597.92     5423337.105      345607.093     5423353.359
      345617.952     5423372.843      345639.601     5423410.833
      345667.279     5423420.628
#Sta/Elev= 22
       0      22    2.13      21    4.13      20    5.92      19     8.9      18
    9.19   17.76   15.62    17.6   23.26   15.76   24.55   15.35   25.05   15.35
   40.57   15.35   48.93   15.35   52.82   16.22   53.28   16.26   56.57   16.64
   59.35   17.72   62.94   19.87   63.28   20.02    63.8   20.09   67.54   20.73
   75.22   20.94  114.05      22
#Mann= 3 , 0 , 0
       0     .06       0   24.55    .035       0   48.93     .06       0
Bank Sta=24.55,48.93
XS Rating Curve= 0 ,0
Exp/Cntr=0.3,0.1

Type RM Length L Ch R = 1 ,1356.61 ,2,2,2
Node Photo=..\..\..\Corner Brook\Windshield Survey\CB photos\P1000651.JPG
BEGIN DESCRIPTION:
immediately downstream of Glynmill Dam
END DESCRIPTION:
XS GIS Cut Line= 5
      345593.298      5423340.72      345597.934     5423353.398
      345606.261     5423367.638       345632.63     5423412.484
      345666.152     5423422.998
#Sta/Elev= 22
       0      22    2.11      21    4.17      20    5.67      19    8.87      18
   18.66      18   32.75    17.5   39.04    17.5   41.15    17.5   41.16      10
   49.16      10   49.17       8   58.67       8   58.68    17.5   66.53   17.53
   74.24    18.1   79.36   20.25    80.4   20.43   84.88   20.56   87.18   20.63
   87.31      21  114.05      22
#Mann= 3 , 0 , 0
       0     .06       0   41.15    .035       0   49.17     .06       0
Bank Sta=41.15,49.17
XS Rating Curve= 0 ,0
Exp/Cntr=0.3,0.1

Type RM Length L Ch R = 1 ,1354.61 ,0.6,0.6,0.6
XS GIS Cut Line= 5
      345590.987     5423341.523      345595.925     5423354.503
      345604.252     5423368.742       345630.62     5423413.589
      345664.968     5423424.243
#Sta/Elev= 22
       0      22    1.84      21    3.61      20    5.92      19    13.5      18
   27.59    17.5   33.88    17.5   35.99    17.5      36   15.35      44   15.35
   44.01    17.5   44.02      22   53.51      22   53.52    17.5   61.37   17.53
   69.08    18.1    74.2   20.25   75.24   20.43   79.72   20.56   82.02   20.63
   89.86      21  117.15      22
#Mann= 3 , 0 , 0
       0    .045       0   35.99     .03       0   44.01    .045       0
Bank Sta=35.99,44.01
XS Rating Curve= 0 ,0
Exp/Cntr=0.3,0.1

Type RM Length L Ch R = 1 ,1354.11 ,2,2,2
XS GIS Cut Line= 5
      345589.681     5423342.126      345594.201     5423355.516
      345602.528     5423369.756      345628.896     5423414.602
      345665.039     5423426.014
#Sta/Elev= 22
       0      22    2.42      21    4.39      20    6.65      19   13.89      18
   27.98    17.5   34.27    17.5   36.38    17.5   36.39   15.35   44.39   15.35
    44.4    17.5   44.41      22    53.9      22   53.91    17.5   61.76   17.53
   69.47    18.1   74.59   20.25   75.63   20.43   80.11   20.56   82.41   20.63
   92.59      21  118.37      22
#Mann= 3 , 0 , 0
       0    .045       0   36.38     .03       0    44.4    .045       0
Bank Sta=36.38,44.4
XS Rating Curve= 0 ,0
Exp/Cntr=0.3,0.1

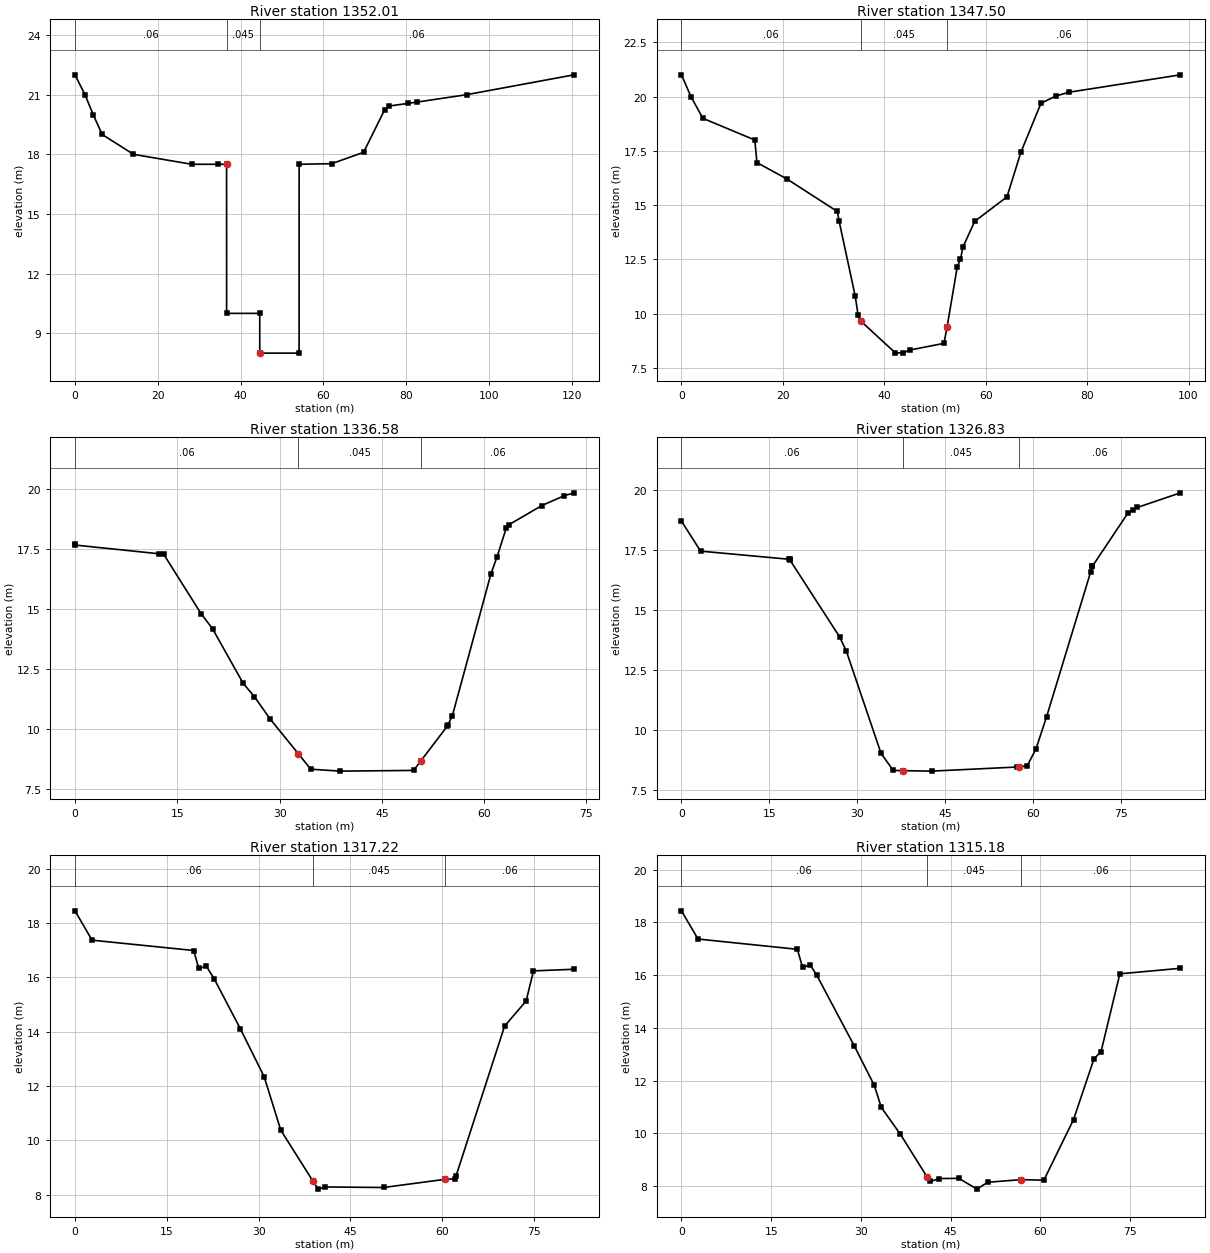
Type RM Length L Ch R = 1 ,1352.01 ,5.89,6.61,7.34
BEGIN DESCRIPTION:
immediately downstream of Glynmill Dam
END DESCRIPTION:
XS GIS Cut Line= 3
 345594.032702965423355.40754138345602.3596682925423369.64734851
  345628.72825965423414.49353992
#Sta/Elev= 21
       0      22    2.42      21    4.39      20    6.56      19   14.13      18
   28.22    17.5   34.51    17.5   36.62    17.5   36.63      10   44.63      10
   44.64       8   54.14       8   54.15    17.5      62   17.53   69.71    18.1
   74.83   20.25   75.87   20.43   80.35   20.56   82.65   20.63   94.59      21
  120.55      22
#Mann= 3 , 0 , 0
       0     .06       0   36.62    .045       0   44.64     .06       0
Bank Sta=36.62,44.64
XS Rating Curve= 0 ,0
Exp/Cntr=0.3,0.1

Type RM Length L Ch R = 1 ,1347.50 ,10.9,10.91,11.24
XS GIS Cut Line= 5
      345588.686     5423345.055      345593.026     5423359.294
      345598.692     5423370.579      345624.909     5423421.453
      345638.343      5423423.96
#Sta/Elev= 26
       0      21    1.87      20    4.21      19   14.46      18   14.89   16.96
   20.77   16.21   30.74   14.71   31.07   14.29   34.28    10.8   34.83    9.94
   35.34    9.67   42.14    8.21   43.61    8.19   44.98    8.33   51.77    8.64
   52.39     9.4   54.39   12.16   55.03   12.52   55.52   13.08   57.85   14.26
   64.19   15.38   66.96   17.45    70.9   19.69   73.88   20.03   76.45    20.2
   98.41      21
#Mann= 3 , 0 , 0
       0     .06       0   35.34    .045       0   52.39     .06       0
Bank Sta=35.34,52.39
XS Rating Curve= 0 ,0
Exp/Cntr=0.3,0.1

Type RM Length L Ch R = 1 ,1336.58 ,9.87,9.75,9.67
XS GIS Cut Line= 3
345578.5264892585423353.88812256345602.9235229495423402.84667969
345616.0902709965423415.81207275
#Sta/Elev= 24
       0    17.7     .04   17.67   12.25   17.31   13.02   17.28   18.49   14.81
   20.17   14.18   24.65   11.91   26.32   11.34   28.63   10.41   32.74    8.97
   34.58    8.32   38.91    8.24   49.67    8.27    50.7    8.66   54.61   10.12
    54.7   10.18   55.34   10.55   61.01   16.48   61.91   17.19   63.23   18.37
   63.64   18.52   68.47   19.32   71.66   19.72   73.18   19.85
#Mann= 3 , 0 , 0
       0     .06       0   32.74    .045       0    50.7     .06       0
Bank Sta=32.74,50.7
XS Rating Curve= 0 ,0
Exp/Cntr=0.3,0.1

Type RM Length L Ch R = 1 ,1326.83 ,9.03,9.61,10.57
XS GIS Cut Line= 3
345567.1068725595423354.02850342345595.5656738285423409.42608643
345613.1859130865423423.93969727
#Sta/Elev= 23
       0   18.69    3.26   17.44   18.41    17.1   18.44    17.1   18.45   17.09
   26.96   13.87   28.11   13.28   34.04    9.01   36.12     8.3   37.81    8.29
   42.68    8.27   57.15    8.44   57.65    8.45   58.96    8.49   60.46    9.19
   62.28   10.54   69.79   16.57   70.07    16.8   70.09   16.81   76.13   19.02
   77.07   19.17   77.74   19.26   85.11   19.87
#Mann= 3 , 0 , 0
       0     .06       0   37.81    .045       0   57.65     .06       0
Bank Sta=37.81,57.65
XS Rating Curve= 0 ,0
Exp/Cntr=0.3,0.1

Type RM Length L Ch R = 1 ,1317.22 ,2.21,2.04,2.76
XS GIS Cut Line= 6
345565.0184936525423354.92169189345572.2908935555423370.13171387
345573.1593017585423375.54650879345572.6735229495423384.02532959
345586.377319336 5423414.9362793345588.875305176 5423431.4876709
#Sta/Elev= 20
       0   18.45    2.79   17.37    19.4   16.99   20.23   16.33   21.48   16.41
   22.79   15.93      27   14.12   30.91   12.35   33.63   10.38   38.88   8.507
   39.74    8.21   40.91    8.29   50.43    8.27   60.45    8.57   62.04    8.59
   62.28     8.7   70.21   14.21   73.72   15.13   74.93   16.24   81.55    16.3
#Mann= 3 , 0 , 0
       0     .06       0   38.88    .045       0   60.45     .06       0
Bank Sta=38.88,60.45
XS Rating Curve= 0 ,0
Exp/Cntr=0.3,0.1

Type RM Length L Ch R = 1 ,1315.18 ,1.1,1.6,1.22
XS GIS Cut Line= 6
 345564.968872075423354.94750977345572.1588745125423369.88769531
345572.0980834965423388.09851074345581.2106933595423407.60107422
 345583.316284185423426.44488525345587.8651123055423432.73028564
#Sta/Elev= 23
       0   18.44    2.77   17.37   19.38   16.98   20.25    16.3   21.55   16.38
   22.64   15.99   28.89   13.32   32.24   11.82   33.42   10.98   36.62    9.96
   41.07   8.343   41.56    8.17   43.13    8.28   46.38    8.29   49.42    7.88
   51.18    8.14   56.79    8.24   60.61    8.22   65.57   10.52   68.98   12.82
   70.17    13.1   73.31   16.05   83.45   16.26
#Mann= 3 , 0 , 0
       0     .06       0   41.07    .045       0   56.79     .06       0
Bank Sta=41.07,56.79
XS Rating Curve= 0 ,0
Exp/Cntr=0.3,0.1