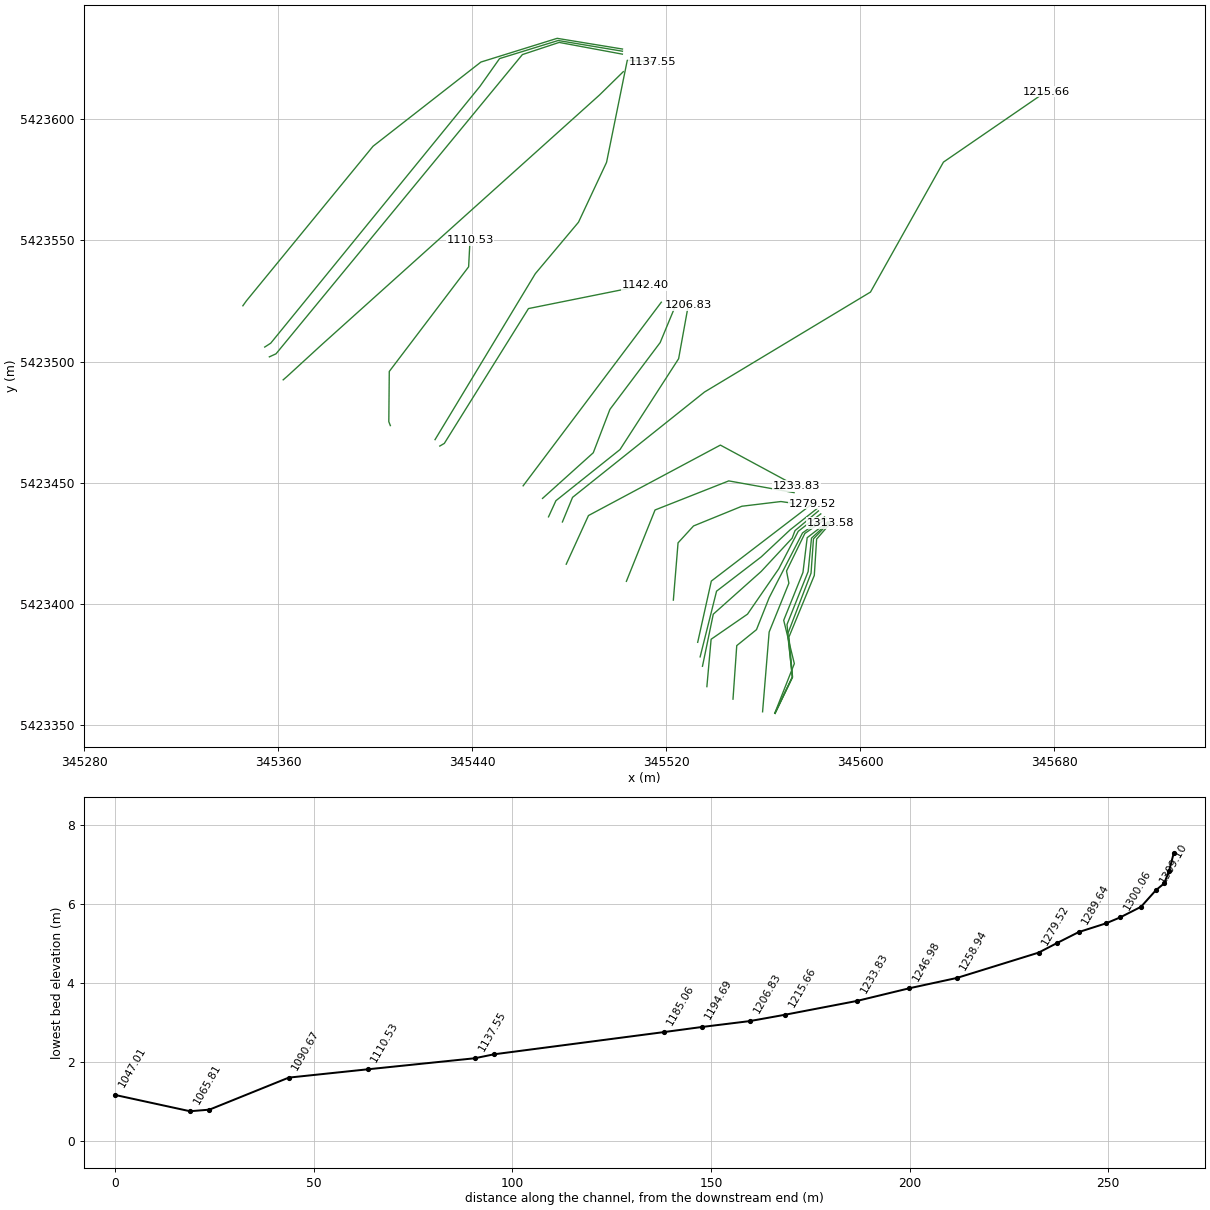
HEC-RAS study Corner_Brook2.prj: Corner_Brook2

--- Corner_Brook2.g01 (geometry) --- (continued)

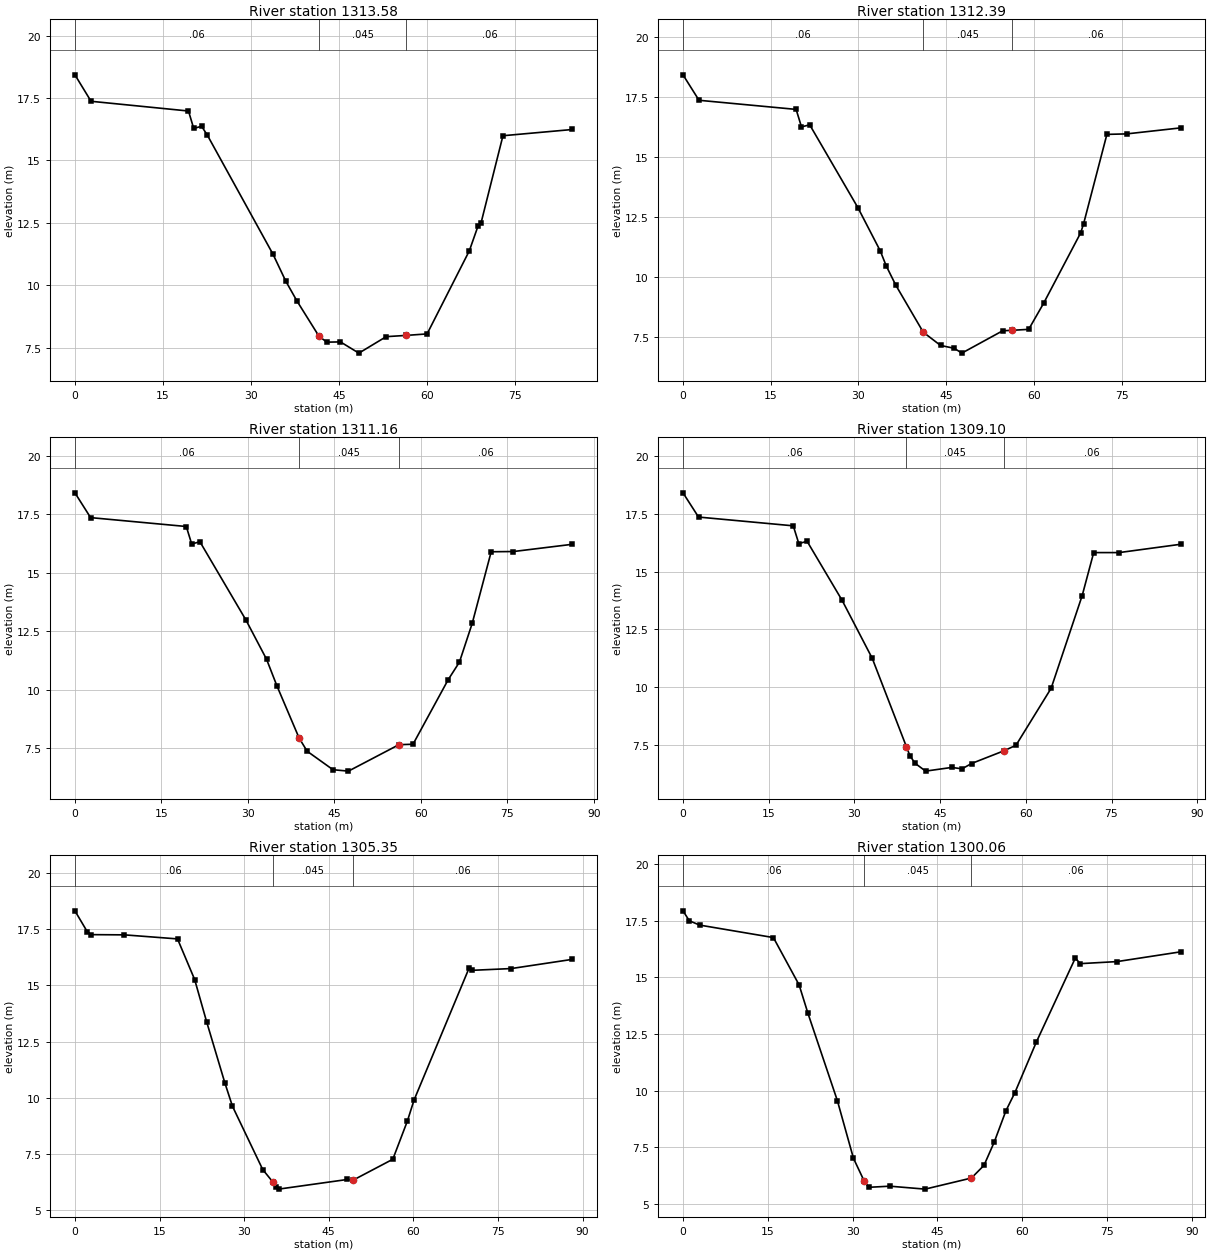
Type RM Length L Ch R = 1 ,1313.58 ,0.78,1.18,1.58
XS GIS Cut Line= 6
345564.9194946295423354.97808838345572.1093139655423369.91827393
345570.6159057625423386.47210693 345581.06829834 5423411.8572998
345582.025512695 5423426.8270874345587.8176879885423433.50067139
#Sta/Elev= 21
       0   18.43    2.75   17.37   19.36   16.98   20.25   16.28   21.59   16.37
   22.58   16.01   33.77   11.24   35.95   10.16   37.87    9.36   41.62    7.95
   42.95    7.72   45.26    7.73    48.4    7.28   53.06    7.94   56.47    7.99
   60.03    8.05   67.23   11.38   68.71   12.37   69.23    12.5   72.96   15.99
   84.81   16.24
#Mann= 3 , 0 , 0
       0     .06       0   41.62    .045       0   56.47     .06       0
Bank Sta=41.62,56.47
XS Rating Curve= 0 ,0
Exp/Cntr=0.3,0.1

Type RM Length L Ch R = 1 ,1312.39 ,0.46,1.23,1.32
XS GIS Cut Line= 6
345564.8464965825423355.00653076345572.0363159185423369.94647217
345570.0844726565423387.67047119345579.7243041995423412.77947998
345580.729309082 5423426.9362793345587.0941162115423433.58447266
#Sta/Elev= 22
       0   18.42    2.74   17.36   19.34   16.98   20.26   16.25   21.66   16.34
   29.92   12.88   33.72   11.09   34.75   10.46   36.38    9.66   41.08     7.7
   44.03    7.15   46.39    7.03   47.67    6.83   54.65    7.76    56.2    7.78
    59.1    7.82   61.66    8.91   67.99   11.84   68.49   12.22   72.47   15.94
   75.85   15.96   85.06   16.21
#Mann= 3 , 0 , 0
       0     .06       0   41.08    .045       0    56.2     .06       0
Bank Sta=41.08,56.2
XS Rating Curve= 0 ,0
Exp/Cntr=0.3,0.1

Type RM Length L Ch R = 1 ,1311.16 ,0.62,2.06,2.03
XS GIS Cut Line= 6
345564.8093261725423355.02832031345571.9993286135423369.96832275
345569.8137207035423391.62249756345578.523071289 5423413.4307251
345579.9135131845423427.22930908345587.4268798835423434.16430664
#Sta/Elev= 20
       0   18.42    2.72   17.36   19.32   16.98   20.26   16.23   21.68   16.33
   29.67   12.98   33.25    11.3   35.05   10.16    38.9    7.93   40.29    7.37
   44.77    6.58   47.45    6.52    56.2    7.65   58.65    7.67   64.75   10.43
    66.7   11.18   68.92   12.84   72.21    15.9   76.08   15.91   86.31   16.22
#Mann= 3 , 0 , 0
       0     .06       0    38.9    .045       0    56.2     .06       0
Bank Sta=38.9,56.2
XS Rating Curve= 0 ,0
Exp/Cntr=0.3,0.1

Type RM Length L Ch R = 1 ,1309.10 ,6.52,3.75,6.42
XS GIS Cut Line= 6
345564.7744750985423355.04187012345572.8378906255423375.49188232
345568.4577026375423393.36468506345576.3964843755423413.10290527
345578.139099121 5423427.4229126345586.6586914065423434.00231934
#Sta/Elev= 21
       0   18.41    2.72   17.36    19.3   16.98   20.27   16.21   21.72   16.31
   27.85   13.75   33.12   11.24    39.1    7.41   39.71    7.02   40.62    6.69
   42.46    6.35   47.03    6.51   48.84    6.45    50.5    6.68   56.16    7.23
   58.28    7.47   64.43    9.94   69.87   13.96   71.88   15.82   76.32   15.82
   87.08   16.18
#Mann= 3 , 0 , 0
       0     .06       0    39.1    .045       0   56.16     .06       0
Bank Sta=39.1,56.16
XS Rating Curve= 0 ,0
Exp/Cntr=0.3,0.1

Type RM Length L Ch R = 1 ,1305.35 ,5.31,5.29,1.97
XS GIS Cut Line= 6
345559.7445068365423355.62988281345562.455322266 5423388.5269165
 345570.587707525423408.65209961345569.6195068365423413.68347168
345577.1710815435423429.16448975345586.0778808595423435.35668945
#Sta/Elev= 22
       0   18.32    2.19   17.39    2.87   17.26    8.78   17.25   18.19   17.07
   21.23   15.26   23.34   13.39   26.57   10.67   27.93    9.62    33.3     6.8
   35.05    6.26   35.66    6.01   36.11    5.93   48.31    6.36   49.32    6.33
   56.36    7.26   58.94    8.96   60.13     9.9   69.88   15.77   70.32   15.67
   77.36   15.75   88.21   16.16
#Mann= 3 , 0 , 0
       0     .06       0   35.05    .045       0   49.32     .06       0
Bank Sta=35.05,49.32
XS Rating Curve= 0 ,0
Exp/Cntr=0.3,0.1

Type RM Length L Ch R = 1 ,1300.06 ,8.07,3.57,2.09
XS GIS Cut Line= 6
345547.5458984385423360.85467529345549.094909668 5423382.9151001
345557.2272949225423389.49450684345562.4553222665423402.65332031
345576.2028808595423429.35791016345585.3032836915423435.93731689
#Sta/Elev= 22
       0   17.94    1.12    17.5    2.96   17.31   15.99   16.76   20.54   14.67
   22.11   13.41   27.31    9.56   30.15    7.02   32.04    6.02   32.84    5.74
   36.58    5.79   42.82    5.66   51.02    6.15   53.24    6.71   55.04    7.73
   57.12    9.12   58.69    9.91   62.48   12.14   69.38   15.85   70.29   15.61
   76.77    15.7      88   16.13
#Mann= 3 , 0 , 0
       0     .06       0   32.04    .045       0   51.02     .06       0
Bank Sta=32.04,51.02
XS Rating Curve= 0 ,0
Exp/Cntr=0.3,0.1

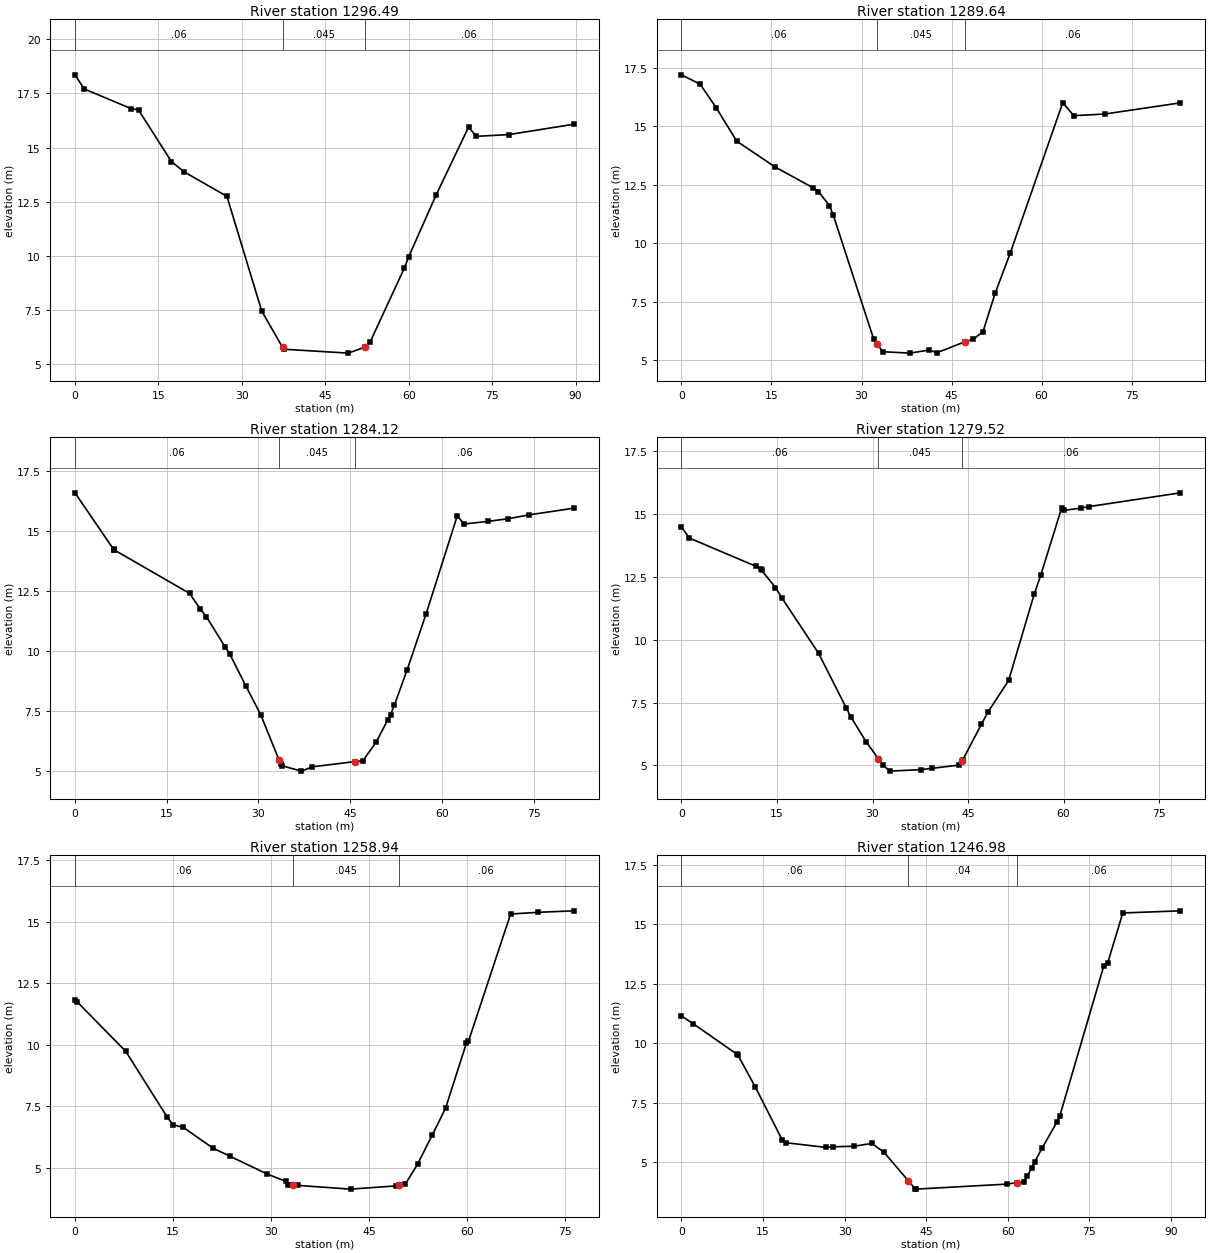
Type RM Length L Ch R = 1 ,1296.49 ,8.66,6.85,4.93
XS GIS Cut Line= 6
345536.7785034185423365.99432373345538.5211181645423385.53912354
345553.5272827155423395.89208984345566.4035034185423414.56591797
345574.439086914  5423430.046875345583.7418823245423437.23492432
#Sta/Elev= 20
       0   18.36    1.65   17.71   10.09    16.8   11.42   16.74   17.35   14.35
   19.62   13.88   27.32   12.75   33.58    7.45   37.34    5.77    37.6    5.69
   49.12    5.51   52.08    5.78    53.1    6.04   59.25    9.45   60.02    9.97
   64.95   12.82   70.76   15.94   72.19   15.52   77.98    15.6   89.73   16.08
#Mann= 3 , 0 , 0
       0     .06       0   37.34    .045       0   52.08     .06       0
Bank Sta=37.34,52.08
XS Rating Curve= 0 ,0
Exp/Cntr=0.3,0.1

Type RM Length L Ch R = 1 ,1289.64 ,6.54,5.51,4.2
XS GIS Cut Line= 6
345534.960083008 5423374.4005127345539.4135131845423395.88031006
345559.163513184 5423413.4899292345571.9431152345423427.22930908
345573.1046752935423430.32550049345582.7863159185423438.45288086
#Sta/Elev= 24
       0   17.21    3.11   16.81    5.82   15.79     9.2   14.37   15.56   13.27
   21.94   12.37   22.83   12.21   24.65   11.61   25.27   11.22      32    5.91
    32.6   5.689   33.52    5.35   38.08    5.29   41.21    5.42    42.6    5.31
   47.16    5.77   48.65    5.89   50.24    6.21   52.28    7.87   54.76    9.56
   63.53   16.02   65.36   15.46    70.5   15.53   83.14   16.01
#Mann= 3 , 0 , 0
       0     .06       0    32.6    .045       0   47.16     .06       0
Bank Sta=32.6,47.16
XS Rating Curve= 0 ,0
Exp/Cntr=0.3,0.1

Type RM Length L Ch R = 1 ,1284.12 ,4.63,4.6,4.6
XS GIS Cut Line= 5
345533.9918823245423378.27069092345540.7689208985423405.36248779
345559.163513184 5423419.4888916345571.1685180665423430.71252441
345582.2053222665423439.42047119
#Sta/Elev= 30
       0   16.61    6.32   14.25    6.35   14.24    6.42   14.23   18.73   12.42
   20.51   11.76   21.48   11.45   24.52    10.2   25.31    9.89   27.93    8.57
   30.41    7.34   33.36    5.48   33.66    5.29   33.92    5.23   37.04    5.01
   38.82    5.19   45.86    5.41   47.06    5.44   49.26    6.22   51.12    7.13
   51.61    7.37   52.25    7.77   54.32    9.23   57.44   11.58   62.52   15.65
   63.63   15.31   67.55   15.42   70.86   15.53   74.21   15.69   81.61   15.97
#Mann= 3 , 0 , 0
       0     .06       0   33.36    .045       0   45.86     .06       0
Bank Sta=33.36,45.86
XS Rating Curve= 0 ,0
Exp/Cntr=0.3,0.1

Type RM Length L Ch R = 1 ,1279.52 ,21.06,20.58,18.23
XS GIS Cut Line= 3
345532.9932861335423384.27532959345538.6085205085423409.52868652
345580.2744750985423441.43670654
#Sta/Elev= 29
       0   14.49    1.24   14.05   11.65   12.93   12.46   12.81   12.57   12.77
   14.76   12.08   15.81   11.65   21.53    9.46   25.87    7.29   26.57    6.94
   29.04    5.92   30.91    5.27   31.67    5.01    32.7    4.77   37.55    4.83
    39.3    4.88   43.58    5.01      44    5.16   44.15    5.21   47.08    6.63
   48.17    7.14   51.37    8.38   55.38   11.81    56.4   12.56   59.71   15.26
   60.07   15.15   62.69   15.24   63.93    15.3   78.35   15.85
#Mann= 3 , 0 , 0
       0     .06       0   30.91    .045       0      44     .06       0
Bank Sta=30.91,44
XS Rating Curve= 0 ,0
Exp/Cntr=0.3,0.1

Type RM Length L Ch R = 1 ,1258.94 ,14.84,11.95,10.6
XS GIS Cut Line= 6
345522.9550781255423401.68572998345524.8914794925423425.29412842
 345531.281127935423432.26068115345551.2249145515423440.38812256
345567.2958984385423442.32330322345572.7175292975423441.54907227
#Sta/Elev= 26
       0   11.82     .36   11.74    7.78    9.73   14.08    7.07   14.99    6.75
   16.57    6.64   21.09     5.8   23.69    5.47   29.43    4.74   32.23    4.45
   32.63    4.29   33.14    4.29    33.4    4.29   34.19    4.28   42.15    4.13
   49.05    4.26    49.5    4.28    50.5    4.32    52.4    5.14   54.68    6.34
   56.69    7.42   59.87   10.06   60.19   10.14   66.64   15.32   70.86   15.39
   76.34   15.45
#Mann= 3 , 0 , 0
       0     .06       0    33.4    .045       0    49.5     .06       0
Bank Sta=33.4,49.5
XS Rating Curve= 0 ,0
Exp/Cntr=0.3,0.1

Type RM Length L Ch R = 1 ,1246.98 ,14.29,13.16,11.44
XS GIS Cut Line= 4
345503.5922851565423409.42608643345515.4036865235423438.84008789
345545.8032836915423450.83770752345572.7175292975423445.99987793
#Sta/Elev= 28
       0   11.14    2.15   10.82   10.24    9.53    10.4    9.49   13.55    8.17
   18.51    5.94   19.18    5.82   26.62    5.62   27.86    5.65    31.7    5.67
   34.98    5.79   37.22    5.42   41.66    4.23   42.99    3.87   43.08    3.87
   59.75    4.08   61.59    4.14      63    4.19   63.52    4.41   64.38    4.75
   64.91    5.01    66.3     5.6      69    6.68   69.56    6.96   77.65   13.26
   78.34   13.37   81.12   15.47   91.72   15.56
#Mann= 3 , 0 , 0
       0     .06       0   41.66     .04       0   61.59     .06       0
Bank Sta=41.66,61.59
XS Rating Curve= 0 ,0
Exp/Cntr=0.3,0.1

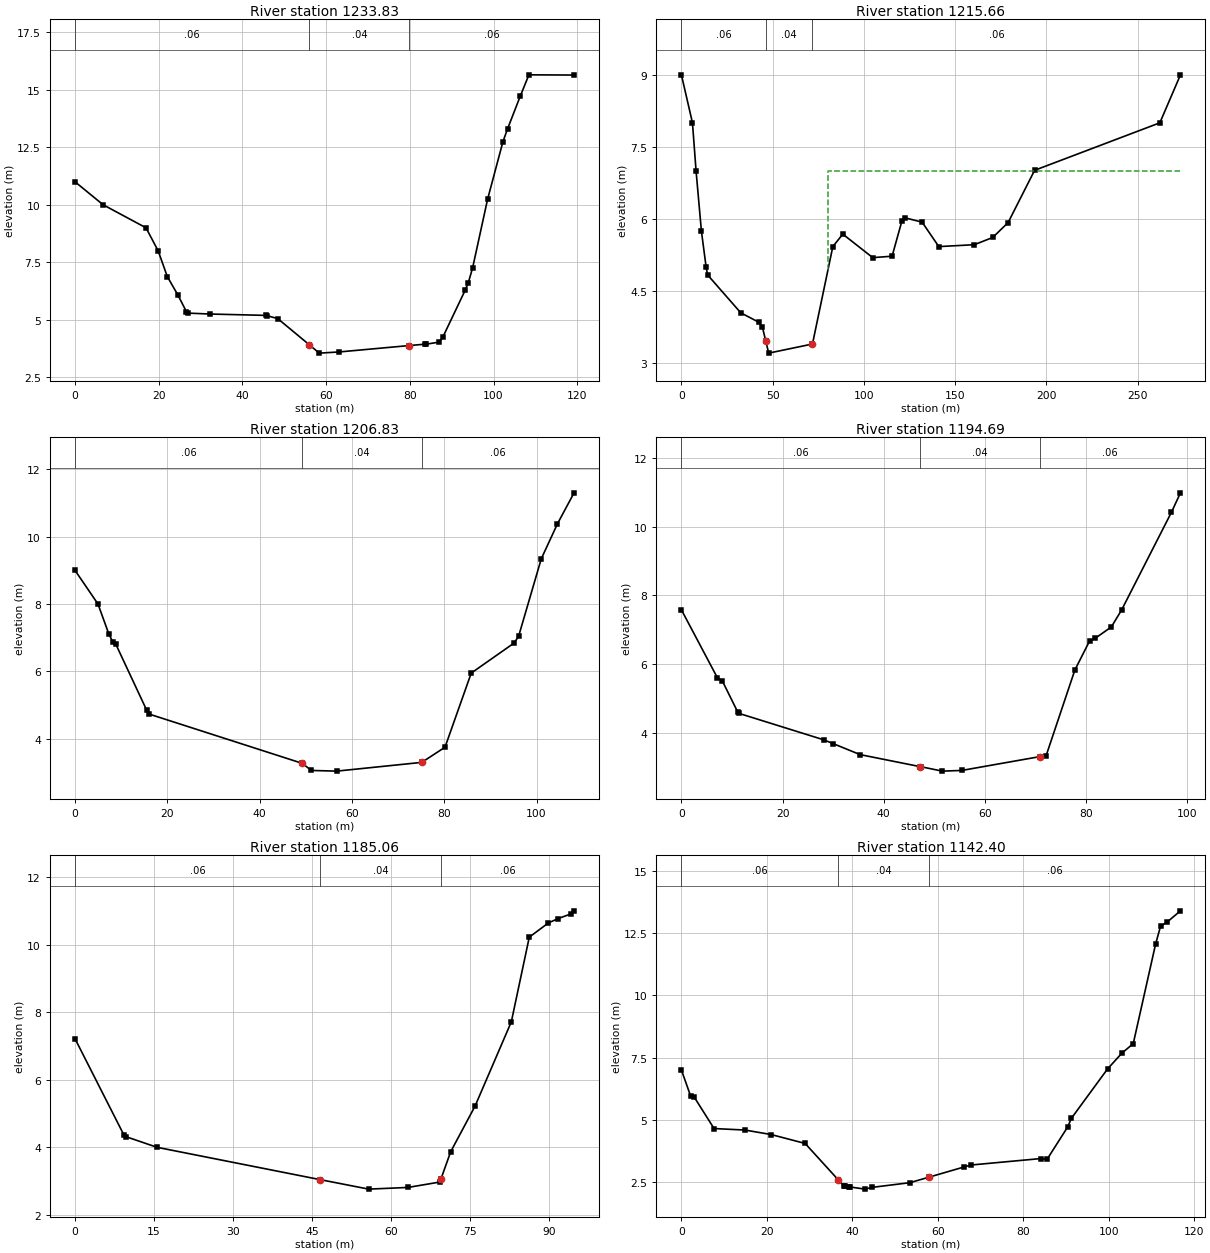
Type RM Length L Ch R = 1 ,1233.83 ,13.43,18.16,44.49
XS GIS Cut Line= 4
      345478.785     5423416.491      345487.955     5423436.547
      345542.344     5423465.597      345573.601     5423448.729
#Sta/Elev= 29
       0      11    6.72      10   16.96       9   19.86       8   22.05    6.88
   24.57    6.08   26.63    5.35   26.98    5.29   32.23    5.25    45.7    5.19
   45.85    5.18   48.44    5.05      56    3.91   58.36    3.55   63.03     3.6
   79.88    3.88   83.71    3.94   83.96    3.94   87.04    4.03   87.94    4.27
   93.23    6.29   93.96    6.61      95    7.26   98.57   10.24  102.25   12.75
  103.36   13.31  106.35   14.71  108.44   15.65  119.23   15.64
#Mann= 3 , 0 , 0
       0     .06       0      56     .04       0   79.88     .06       0
Bank Sta=56,79.88
XS Rating Curve= 0 ,0
Exp/Cntr=0.3,0.1

Type RM Length L Ch R = 1 ,1215.66 ,3.29,8.84,30.29
XS GIS Cut Line= 6
      345477.213       5423433.9      345481.391     5423444.044
      345535.779     5423487.463      345604.234     5423528.694
      345634.313     5423582.273      345676.696     5423611.391
#Sta/Elev= 26
       0       9    6.06       8    8.03       7   10.97    5.74   13.56    4.99
   14.36    4.83   32.53    4.04   42.62    3.84    44.4    3.74   46.23    3.45
   47.83     3.2   71.81    3.39   82.96    5.42   88.42    5.68  104.84    5.19
  115.43    5.22  120.85    5.96  122.47    6.02  131.88    5.93  141.03    5.42
  160.48    5.46  170.55    5.61  178.98    5.92  193.51    7.01  262.13       8
  273.42       9
#Mann= 3 , 0 , 0
       0     .06       0   46.23     .04       0   71.81     .06       0
#XS Ineff= 2 , 0
   10.97                   80.27   10.97       7
Permanent Ineff=
       F       F
Bank Sta=46.23,71.81
XS Rating Curve= 0 ,0
Exp/Cntr=0.3,0.1

Type RM Length L Ch R = 1 ,1206.83 ,5.65,12.13,10.44
XS GIS Cut Line= 5
      345471.485     5423436.009      345474.532      5423442.67
       345500.97      5423463.77      345525.126     5423501.218
       345529.12     5423523.268
#Sta/Elev= 18
       0       9    4.98       8    7.33    7.11    8.24    6.86     8.8    6.82
   15.56    4.84   16.14    4.73   49.26    3.27    51.2    3.06    56.7    3.04
   75.14     3.3   80.17    3.75   85.85    5.95   95.12    6.84   96.11    7.04
  101.02    9.34  104.53   10.38  108.13    11.3
#Mann= 3 , 0 , 0
       0     .06       0   49.26     .04       0   75.14     .06       0
Bank Sta=49.26,75.14
XS Rating Curve= 0 ,0
Exp/Cntr=0.3,0.1

Type RM Length L Ch R = 1 ,1194.69 ,13.81,9.63,10.09
XS GIS Cut Line= 5
345469.0161132815423443.62091064345489.9384765635423462.43969727
345496.7857055665423480.30792236345517.5178833015423507.87091064
345523.9846801765423523.45812988
#Sta/Elev= 21
       0    7.58    7.09    5.61     8.1    5.51   11.09    4.62   11.34    4.57
   28.14     3.8   29.98    3.69   35.33    3.37    47.2    3.02   47.28    3.02
   51.57    2.89   55.42    2.91   70.78    3.31   72.09    3.34   77.77    5.83
    80.7    6.68   81.77    6.75   84.97    7.08   86.99    7.57   96.84   10.41
   98.64   10.98
#Mann= 3 , 0 , 0
       0     .06       0    47.2     .04       0   70.78     .06       0
Bank Sta=47.2,70.78
XS Rating Curve= 0 ,0
Exp/Cntr=0.3,0.1

Type RM Length L Ch R = 1 ,1185.06 ,39.08,42.67,27.12
XS GIS Cut Line= 2
345461.0206909185423448.80969238345517.9926757815423524.51312256
#Sta/Elev= 17
       0    7.22    9.27    4.37    9.77    4.31   15.57       4   46.59    3.04
   55.77    2.76   63.21    2.81   69.26    2.97    69.5    3.07   71.33    3.87
   75.95    5.22   82.84    7.72   86.25   10.23   89.87   10.65   91.71   10.78
   94.19   10.92   94.75   11.01
#Mann= 3 , 0 , 0
       0     .06       0   46.59     .04       0    69.5     .06       0
Bank Sta=46.59,69.5
XS Rating Curve= 0 ,0
Exp/Cntr=0.3,0.1

Type RM Length L Ch R = 1 ,1142.40 ,4.43,4.85,27.61
XS GIS Cut Line= 4
      345426.654     5423465.206      345428.519     5423466.288
      345463.215     5423521.888      345511.352     5423531.572
#Sta/Elev= 29
       0       7    2.16    5.95    2.99    5.91    7.64    4.64   14.87    4.58
   20.97     4.4   28.96    4.04   36.66   2.583      38    2.33   38.37    2.31
   39.13    2.29   39.35    2.29   42.98     2.2    44.6    2.27   53.49    2.46
   57.94   2.682    66.1    3.09    67.7    3.17   84.05    3.43   85.58     3.4
   90.39     4.7   91.26    5.05   99.73    7.04  103.11    7.68  105.75    8.06
  110.98   12.07  112.14   12.79  113.63   12.95   116.8   13.41
#Mann= 3 , 0 , 0
       0     .06       0   36.66     .04       0   57.94     .06       0
Bank Sta=36.66,57.94
XS Rating Curve= 0 ,0
Exp/Cntr=0.3,0.1

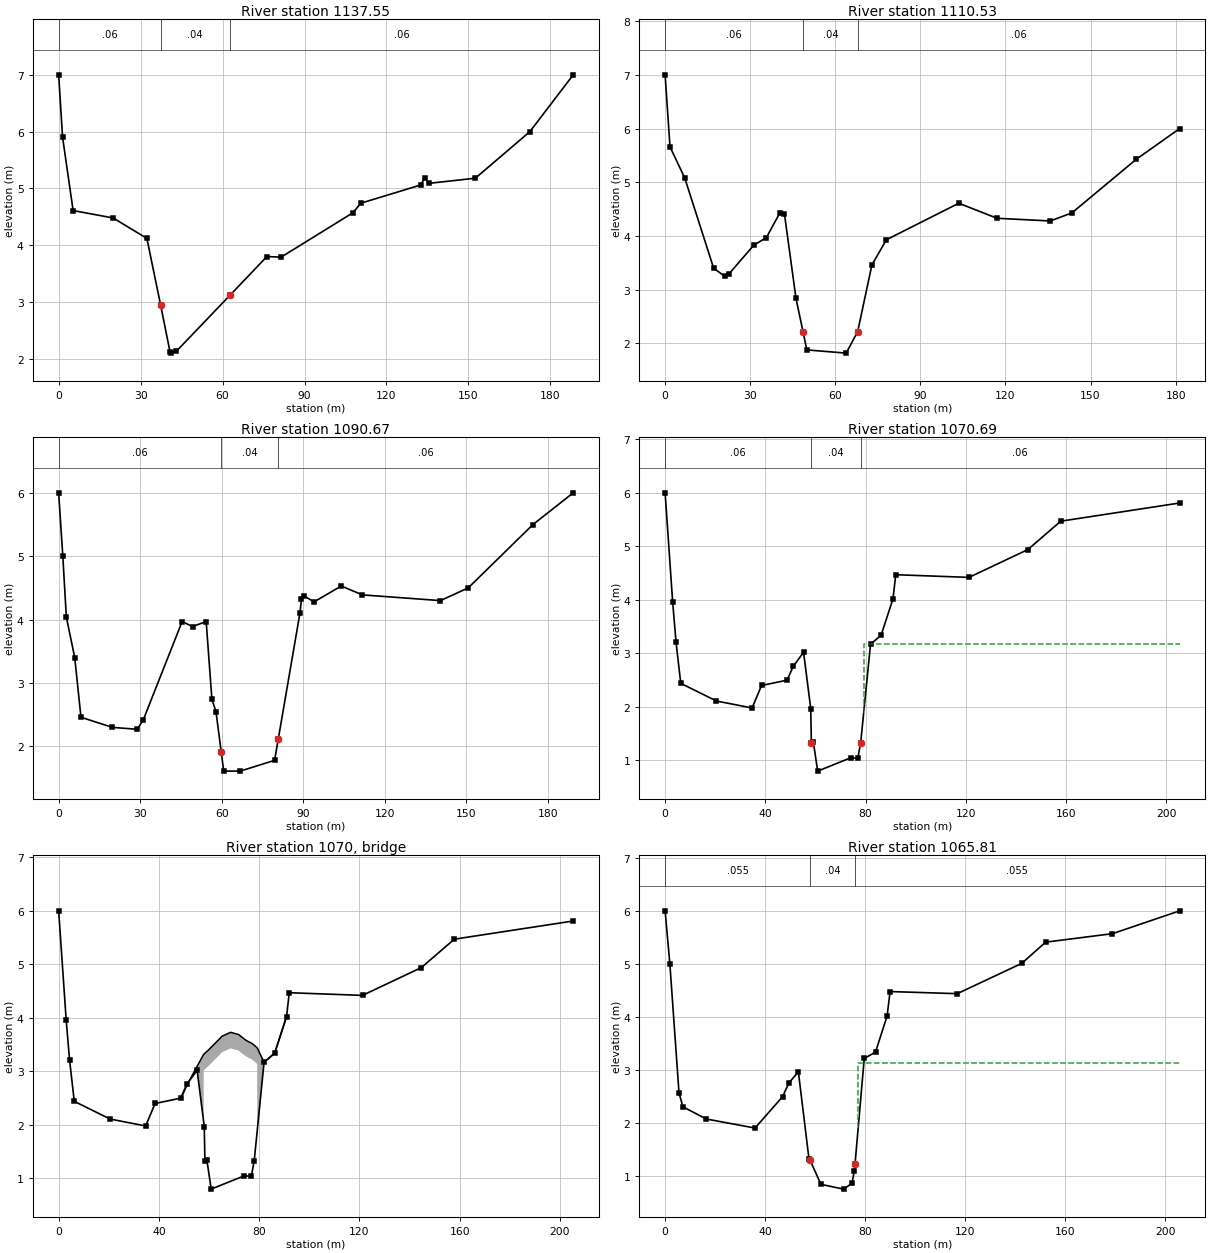
Type RM Length L Ch R = 1 ,1137.55 ,29.92,27.02,29.65
XS GIS Cut Line= 6
      345424.695     5423467.845      345466.029     5423536.257
      345483.845     5423557.498      345495.411     5423582.174
      345503.954      5423624.25      345514.441     5423623.702
#Sta/Elev= 20
       0       7    1.44     5.9     5.3    4.61   19.94    4.48    32.3    4.12
   37.31    2.95   40.77    2.12    41.1     2.1   43.02    2.13   62.73    3.12
   76.22     3.8   81.43    3.79  107.66    4.57  110.64    4.74  132.49    5.06
  133.99    5.18  135.71    5.09  152.53    5.18  172.49       6  188.35       7
#Mann= 3 , 0 , 0
       0     .06       0   37.31     .04       0   62.73     .06       0
Bank Sta=37.31,62.73
XS Rating Curve= 0 ,0
Exp/Cntr=0.3,0.1

Type RM Length L Ch R = 1 ,1110.53 ,25.03,19.85,11
XS GIS Cut Line= 5
      345406.265     5423473.636      345405.634     5423475.242
      345405.824     5423495.961      345438.539     5423539.111
       345439.11     5423550.136
#Sta/Elev= 23
       0       7    1.72    5.66    6.92    5.08   17.12     3.4   21.03    3.25
   22.44    3.29   31.27    3.83    35.7    3.97   40.46    4.43   42.08    4.41
   46.14    2.84   48.62    2.22   49.96    1.88   63.84    1.82   67.89    2.22
    72.9    3.46   78.01    3.93  103.55    4.61  117.02    4.33  135.79    4.28
  143.42    4.43  166.17    5.43  181.43       6
#Mann= 3 , 0 , 0
       0     .06       0   48.62     .04       0   67.89     .06       0
Bank Sta=48.62,67.89
XS Rating Curve= 0 ,0
Exp/Cntr=0.3,0.1

Type RM Length L Ch R = 1 ,1090.67 ,16.1,19.98,36.69
XS GIS Cut Line= 5
      345362.084     5423492.508      345363.835     5423494.033
       345377.77     5423506.815      345492.503     5423609.947
      345502.318     5423619.568
#Sta/Elev= 28
       0       6    1.53       5    2.83    4.04    5.92     3.4    8.21    2.46
   19.77     2.3   28.91    2.27   31.14    2.42   45.42    3.97   49.24    3.89
   54.26    3.97   56.37    2.74   57.86    2.55    59.8    1.91   60.71    1.61
   66.75    1.61   79.42    1.78   80.75    2.11   88.73     4.1   89.31    4.32
   90.36    4.37   93.94    4.28  103.94    4.53  111.72    4.39  140.41     4.3
  150.63     4.5  174.45     5.5  189.25       6
#Mann= 3 , 0 , 0
       0     .06       0    59.8     .04       0   80.75     .06       0
Bank Sta=59.8,80.75
XS Rating Curve= 0 ,0
Exp/Cntr=0.3,0.1

Type RM Length L Ch R = 1 ,1070.69 ,4.67,4.88,5.23
XS GIS Cut Line= 5
      345356.384     5423501.981      345359.122     5423503.233
      345460.709     5423626.616       345475.87     5423631.631
      345501.934     5423626.792
#Sta/Elev= 25
       0       6    3.01    3.96    4.36    3.21    6.24    2.44    20.5    2.11
   34.71    1.98   38.47     2.4   48.69     2.5   51.13    2.76   55.25    3.02
    58.1    1.97   58.36    1.32   59.12    1.35   60.87      .8   74.09    1.05
   76.88    1.04   78.03    1.33   81.96    3.17   86.18    3.34   90.93    4.02
   92.01    4.47  121.24    4.42  144.74    4.94  157.86    5.47  205.31    5.81
#Mann= 3 , 0 , 0
       0     .06       0   58.36     .04       0   78.03     .06       0
#XS Ineff= 2 , 0
    3.01   57.88    1.98   79.23    3.01    3.17
Permanent Ineff=
       F       F
Bank Sta=58.36,78.03
XS Rating Curve= 0 ,0
Exp/Cntr=0.5,0.3

Type RM Length L Ch R = 3 ,1070    ,,,
BEGIN DESCRIPTION:
Pedestrian Trail Bridge (Structure #2107)
END DESCRIPTION:
Bridge Culvert--1,0,-1,-1, 0
Deck Dist Width WeirC Skew NumUp NumDn MinLoCord MaxHiCord MaxSubmerge Is_Ogee
1.9,1.9,1.67,0, 16, 16, 1.98, , 0.98, 0, 0,0,,
   48.85   51.36   57.87   57.88   59.79   62.32   65.29    68.6   71.74   74.76
   77.22   79.22   79.23   81.96   86.19   90.88
     2.5    2.76    3.32    3.32     3.4    3.52    3.66    3.73    3.69    3.58
    3.52    3.44    3.44    3.17    3.34    4.02
                       1    3.02     3.1    3.22    3.36    3.43    3.39    3.28
    3.22    3.14       1
   46.83   49.37   55.76   55.77   57.69   60.23   63.19   66.51   69.65   72.74
   75.12   77.15   77.16   79.87   84.11   88.77
     2.5    2.76    3.32    3.32     3.4    3.52    3.66    3.73    3.69    3.58
    3.52    3.44    3.44    3.17    3.34    4.02
                       1    3.02     3.1    3.22    3.36    3.43    3.39    3.28
    3.22    3.14       1
BR Coef=-1 , 0 , 0 ,, 0 ,,,0.8,-1,,0,
WSPro=,,,, 1 ,,,, 0 ,,,, 0 ,,,,-1 ,-1 ,-1 , 0 , 0 , 0 , 0 , 0
BC Design=,, 0 ,, 0 ,,,,,,
BC Use User HTab Curves=0
BC User HTab FreeFlow(D)= 0

Type RM Length L Ch R = 1 ,1065.81 ,18.84,18.79,18.93
XS GIS Cut Line= 6
      345354.466     5423506.021      345356.933     5423507.606
      345443.205     5423613.497      345451.303     5423624.964
      345475.468     5423632.417       345501.96     5423628.005
#Sta/Elev= 25
       0       6     1.9       5    5.56    2.57    7.11    2.31   16.49    2.08
   35.93    1.91   46.94     2.5   49.51    2.76   53.27    2.97   57.53    1.32
   57.98     1.3    62.3     .85   71.37     .76   74.68     .87   75.68    1.11
   75.93    1.24    79.6    3.22   84.11    3.34   88.74    4.02   89.93    4.48
  116.77    4.44  142.54    5.01   152.1    5.41  178.84    5.57   205.7       6
#Mann= 3 , 0 , 0
       0    .055       0   57.98     .04       0   75.93    .055       0
#XS Ineff= 2 , 0
    2.93   55.77    1.98   77.16    2.93    3.14
Permanent Ineff=
       F       F
Bank Sta=57.98,75.93
XS Rating Curve= 0 ,0
Exp/Cntr=0.5,0.3

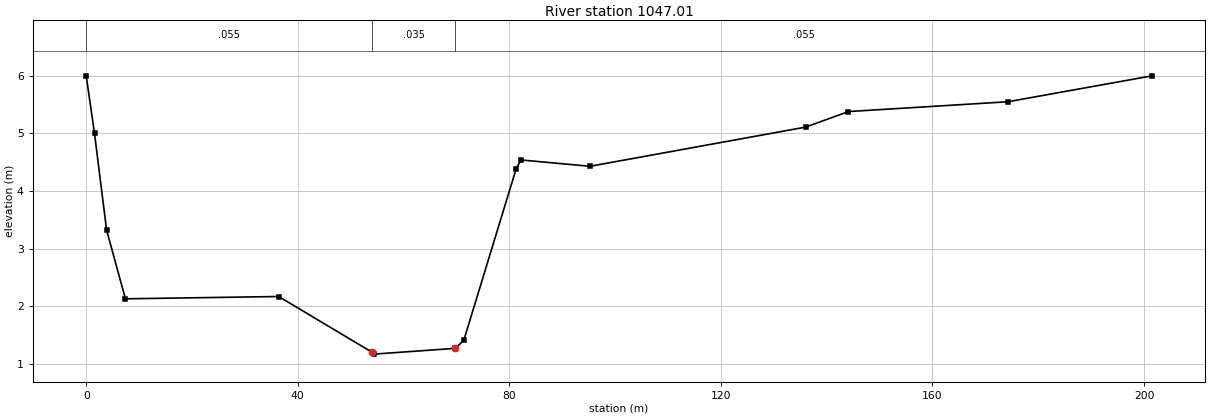
Type RM Length L Ch R = 1 ,1047.01 ,53.72,42.98,45.75
XS GIS Cut Line= 6
      345345.453     5423523.043      345346.931     5423525.098
      345399.131      5423588.82      345443.606     5423623.533
       345475.05     5423633.312      345501.969       5423628.9
#Sta/Elev= 16
       0       6    1.57       5    3.86    3.32    7.41    2.13   36.39    2.17
   54.09     1.2   54.36    1.17   69.79    1.27   71.39    1.41    81.3    4.39
   82.19    4.54   95.25    4.43  136.02    5.11  144.12    5.38  174.25    5.55
  201.53       6
#Mann= 3 , 0 , 0
       0    .055       0   54.09    .035       0   69.79    .055       0
Bank Sta=54.09,69.79
XS Rating Curve= 0 ,0
Exp/Cntr=0.3,0.1