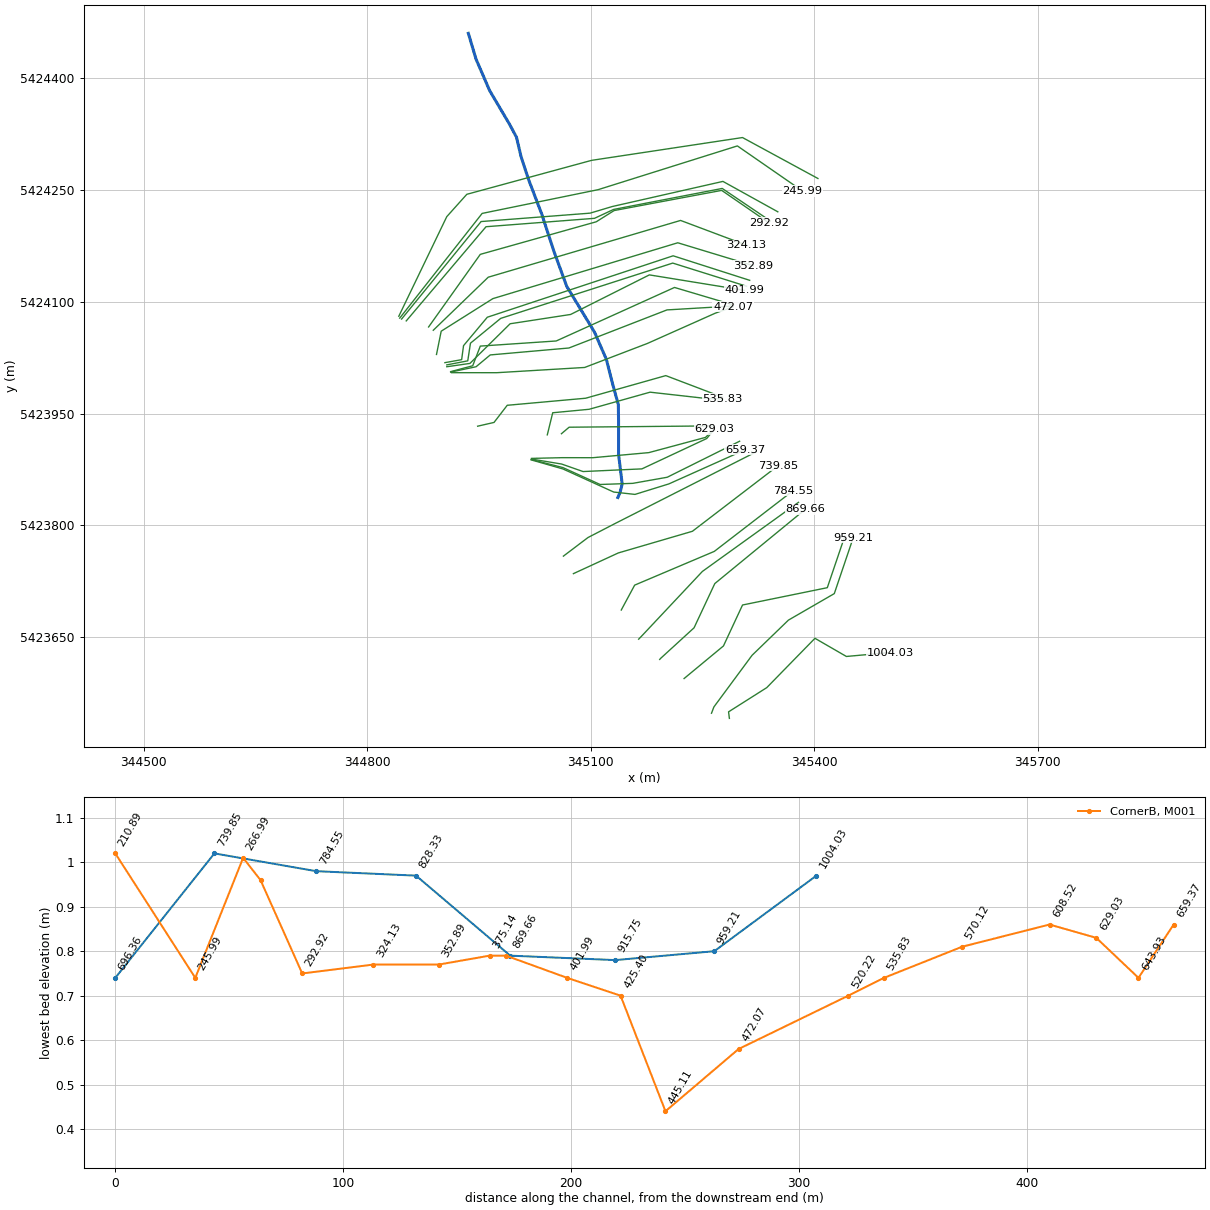
HEC-RAS study Corner_Brook2.prj: Corner_Brook2

--- Corner_Brook2.g01 (geometry) --- (continued)

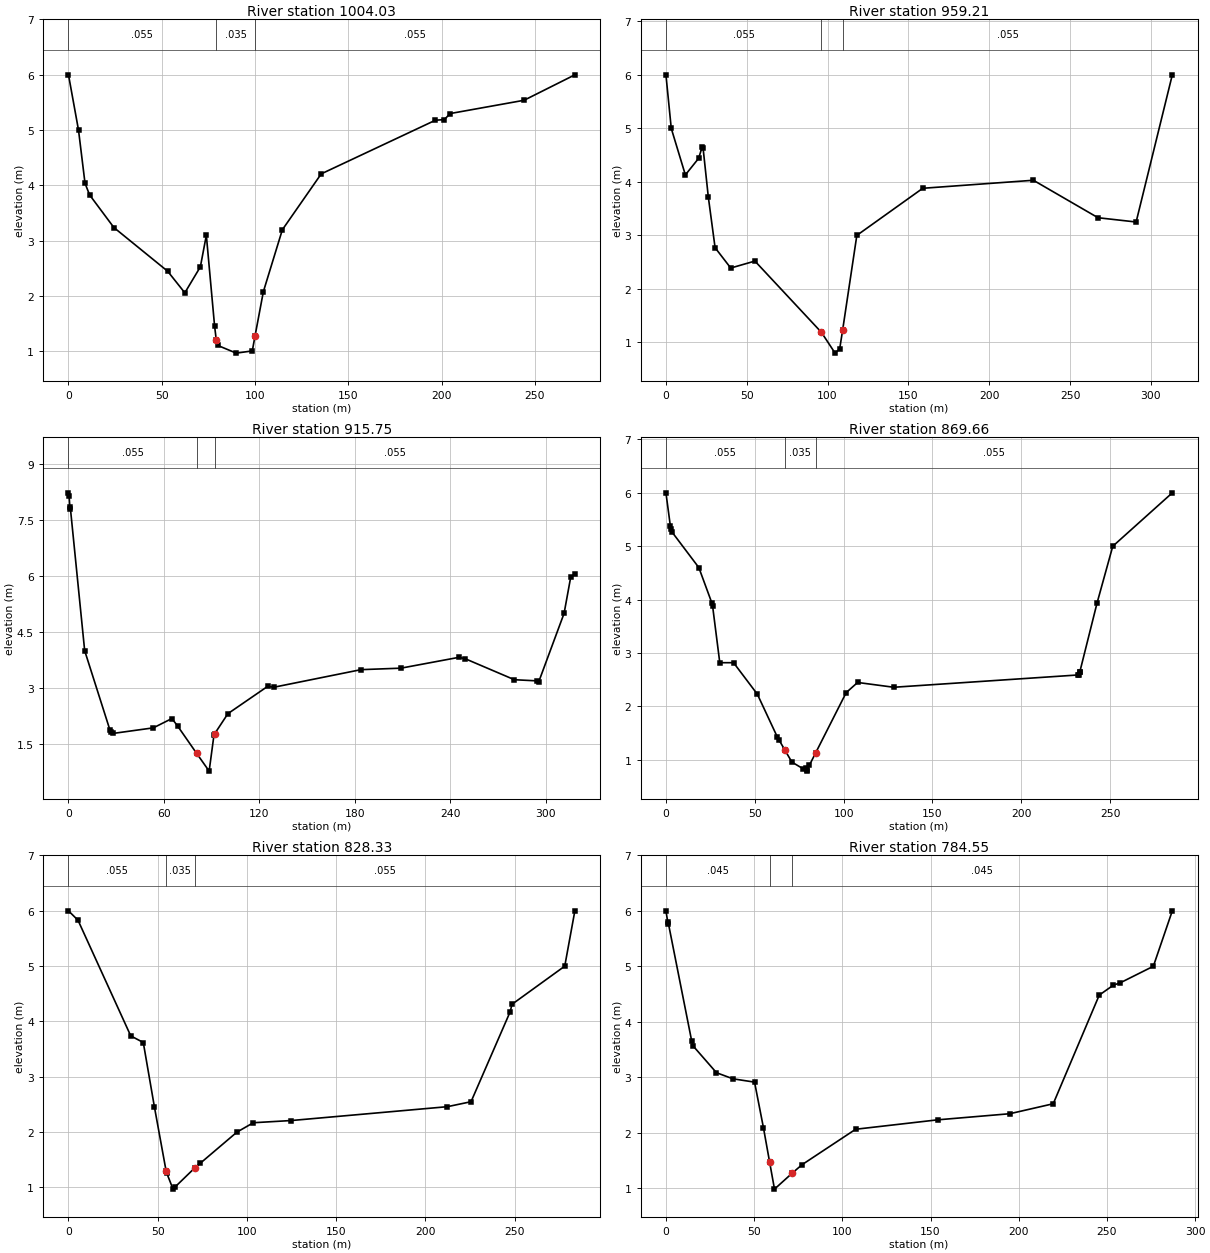
Type RM Length L Ch R = 1 ,1004.03 ,33.48,44.82,43.49
XS GIS Cut Line= 6
      345286.098     5423540.982      345284.981     5423549.769
      345336.244     5423582.255      345400.947     5423648.475
      345443.145     5423624.111      345501.909     5423629.421
#Sta/Elev= 23
       0       6    5.38       5    8.86    4.04   11.31    3.83   24.33    3.24
   53.16    2.45   62.36    2.06   70.69    2.53   73.89     3.1   78.31    1.46
   79.25     1.2   79.94    1.11   89.91     .97   98.52    1.01   99.99    1.28
  104.45    2.08  114.63     3.2  135.47    4.21   196.7    5.18  201.44    5.19
  204.57     5.3  244.18    5.54  271.42       6
#Mann= 3 , 0 , 0
       0    .055       0   79.25    .035       0   99.99    .055       0
Bank Sta=79.25,99.99
XS Rating Curve= 0 ,0
Exp/Cntr=0.3,0.1

Type RM Length L Ch R = 1 ,959.21  ,44.89,43.46,56.67
XS GIS Cut Line= 6
       345262.09     5423547.921      345265.312     5423556.369
      345316.575     5423625.714      345365.337      5423672.88
      345426.915      5423708.49      345452.275     5423783.359
#Sta/Elev= 20
       0       6    3.29       5   12.02    4.13   20.24    4.44   22.48    4.66
   22.99    4.63   26.21    3.72   30.41    2.77   40.09    2.39   55.05    2.52
   96.16    1.19  104.66      .8  107.51     .88  109.37    1.24  118.11       3
   158.9    3.88  227.34    4.03  267.33    3.33  290.91    3.25   313.3       6
#Mann= 3 , 0 , 0
       0    .055       0   96.16    .035       0  109.37    .055       0
Bank Sta=96.16,109.37
XS Rating Curve= 0 ,0
Exp/Cntr=0.3,0.1

Type RM Length L Ch R = 1 ,915.75  ,44.49,46.09,46.12
XS GIS Cut Line= 5
      345225.291      5423594.48      345278.116     5423638.211
      345303.747     5423693.187      345417.539     5423716.431
      345440.982     5423785.463
#Sta/Elev= 28
       0    8.24     .38    8.16     .85    7.87    1.26     7.8   10.17    4.01
   26.14    1.87    26.6    1.83   27.93    1.79   53.33    1.94      65    2.19
   68.58    1.99   80.48    1.26   88.41     .78   91.45    1.75   91.86    1.78
  100.19    2.32  125.11    3.05  129.23    3.03  183.83     3.5  208.97    3.54
  245.38    3.83  249.51    3.79  280.29    3.23  294.34     3.2  295.62    3.18
  311.51    5.01  315.71    5.99  318.28    6.06
#Mann= 3 , 0 , 0
       0    .055       0   80.48    .035       0   91.86    .055       0
Bank Sta=80.48,91.86
XS Rating Curve= 0 ,0
Exp/Cntr=0.3,0.1

Type RM Length L Ch R = 1 ,869.66  ,42.02,41.32,31.8
XS GIS Cut Line= 5
      345192.565     5423620.154        345194.3      5423621.99
      345238.686     5423662.597      345266.505     5423721.946
       345387.72     5423821.424
#Sta/Elev= 30
       0       6    2.53    5.37    2.61    5.33    3.56    5.26   18.53     4.6
   25.83    3.94   26.23    3.89   30.31    2.82   38.07    2.82   51.46    2.23
   62.69    1.43   63.54    1.38   66.98   1.183   70.88     .96   77.41     .83
   78.71     .84   79.44     .79   79.53     .82   80.74      .9   84.36   1.137
  101.47    2.26   107.9    2.45  128.23    2.36  231.87    2.59  232.69    2.59
  232.97    2.64  232.99    2.65   242.7    3.94  251.52       5  285.04       6
#Mann= 3 , 0 , 0
       0    .055       0   66.98    .035       0   84.36    .055       0
Bank Sta=66.98,84.36
XS Rating Curve= 0 ,0
Exp/Cntr=0.3,0.1

Type RM Length L Ch R = 1 ,828.33  ,50.77,43.78,31.08
XS GIS Cut Line= 4
      345164.294     5423647.316      345168.009     5423651.144
      345249.904     5423738.293      345378.862     5423831.031
#Sta/Elev= 20
       0       6    5.33    5.83   34.89    3.74   41.92    3.62   48.13    2.46
   54.75    1.29   55.06    1.26   58.59     .97   59.77    1.01   70.65    1.35
   73.94    1.44   94.38       2  103.58    2.17  124.92    2.21  212.31    2.46
  225.59    2.55  247.57    4.18  248.51    4.31   278.1       5  283.77       6
#Mann= 3 , 0 , 0
       0    .055       0   54.75    .035       0   70.65    .055       0
Bank Sta=54.75,70.65
XS Rating Curve= 0 ,0
Exp/Cntr=0.3,0.1

Type RM Length L Ch R = 1 ,784.55  ,56.66,44.7,40.93
XS GIS Cut Line= 5
      345140.972     5423686.402       345141.44     5423687.378
      345158.944     5423719.864      345265.845     5423765.156
      345371.196     5423846.325
#Sta/Elev= 22
       0       6    1.08    5.79    1.41    5.77   14.55    3.66   15.48    3.56
   28.65    3.08   37.98    2.97   50.24    2.91   55.27    2.09   58.77    1.47
   61.54     .98   71.65    1.27   77.13    1.42  107.56    2.06  154.08    2.23
  194.93    2.34  219.57    2.52  245.66    4.48   253.7    4.66  257.47     4.7
  276.33       5  287.08       6
#Mann= 3 , 0 , 0
       0    .045       0   58.77    .035       0   71.65    .045       0
Bank Sta=58.77,71.65
XS Rating Curve= 0 ,0
Exp/Cntr=0.3,0.1

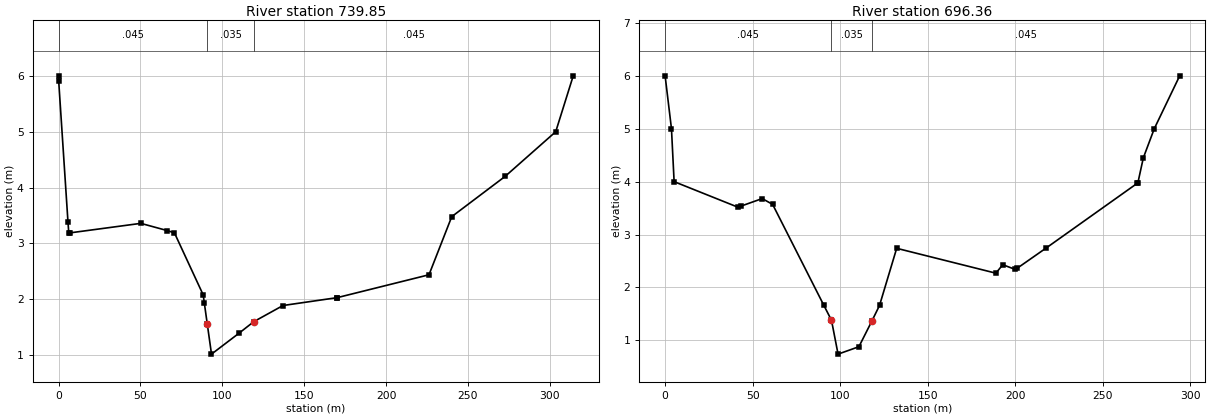
Type RM Length L Ch R = 1 ,739.85  ,37.83,43.49,53.15
XS GIS Cut Line= 4
      345076.712     5423735.284      345137.039     5423763.084
      345236.439     5423792.134      345351.066      5423879.91
#Sta/Elev= 22
       0       6     .02    5.91    5.71    3.38    6.21    3.18    6.96    3.19
   50.21    3.36   66.42    3.23   70.74    3.19   88.31    2.08   89.02    1.93
    90.8   1.558   93.38    1.02     110    1.39  119.17     1.6  137.07    1.89
  169.98    2.03  170.06    2.03  226.25    2.44  240.15    3.48  272.74     4.2
  303.67       5  314.36       6
#Mann= 3 , 0 , 0
       0    .045       0    90.8    .035       0  119.17    .045       0
Bank Sta=90.8,119.17
XS Rating Curve= 0 ,0
Exp/Cntr=0.3,0.1

Type RM Length L Ch R = 1 ,696.36  ,64.23,36.99,20.23
XS GIS Cut Line= 4
      345063.287     5423758.789      345096.278     5423783.749
      345132.515     5423802.491      345321.259     5423898.327
#Sta/Elev= 24
       0       6    3.63       5    5.14       4   41.37    3.52   43.54    3.54
   55.45    3.68    61.4    3.57   90.68    1.66   95.01    1.38   98.76     .74
  110.67     .88  117.99    1.36  122.44    1.66  132.24    2.74  188.88    2.27
  192.82    2.43  200.02    2.34  200.92    2.36  217.79    2.75  269.67    3.97
  269.99    3.98  273.09    4.45  279.33       5  293.85       6
#Mann= 3 , 0 , 0
       0    .045       0   95.01    .035       0  117.99    .045       0
Bank Sta=95.01,117.99
XS Rating Curve= 0 ,0
Exp/Cntr=0.3,0.1

River Reach=CornerB         ,M001
Reach XY= 20
345136.4133300785423837.49328613345139.4481201175423844.47027588
  345142.1796875 5423855.6940918345137.3206787115423895.59008789
345137.320678711  5423939.878479345137.0172729495423962.32592773
345129.7332763675423988.41369629345120.9318847665424022.99511719
345105.1063232425424059.30529785345087.5034790045424088.42651367
345067.7761230475424120.88427734345050.7802734385424167.29632568
345034.0878906255424218.25830078345016.4049072275424264.61590576
345006.3895263675424295.25390625345000.3195190435424321.03808594
344990.9110717775424338.63232422344964.2033081055424383.83068848
344945.9935302735424425.99572754344935.674499512 5424460.5770874

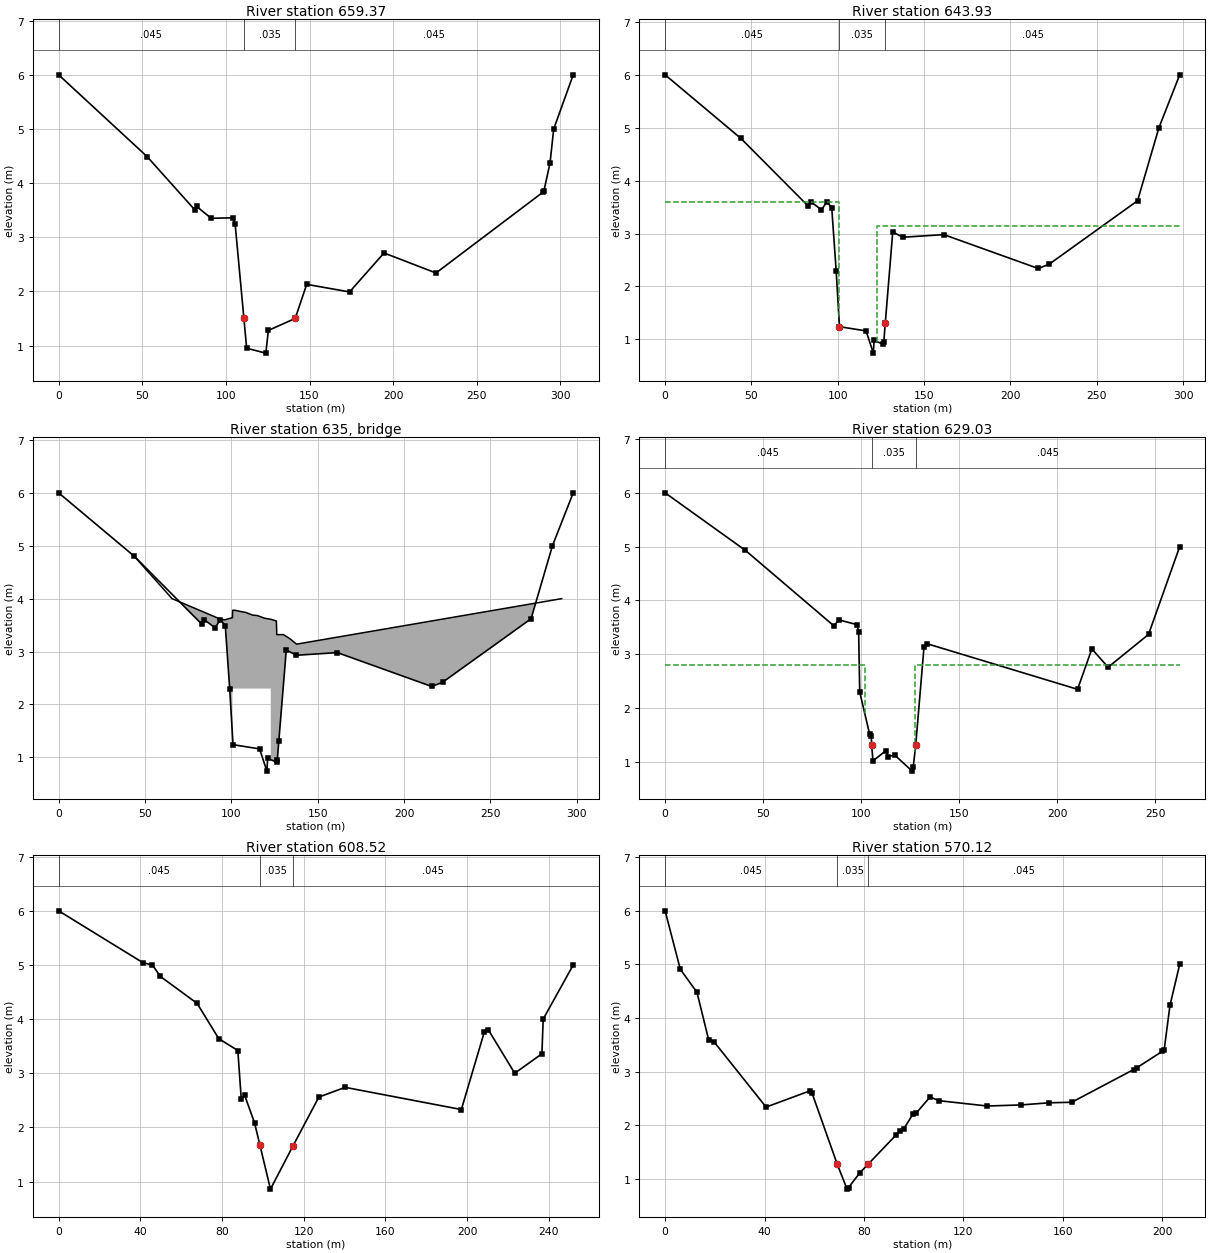
Type RM Length L Ch R = 1 ,659.37  ,6.01,15.44,16.77
XS GIS Cut Line= 6
      345019.923     5423888.005      345062.738     5423875.777
      345130.858       5423844.8      345159.361     5423841.647
      345204.919     5423855.768      345306.953     5423901.466
#Sta/Elev= 21
       0       6   52.88    4.49   81.27    3.51   82.46    3.57   91.21    3.35
  104.43    3.36  105.52    3.24  110.73   1.506   112.4     .95  123.84     .86
  125.39    1.28   141.4     1.5  148.29    2.13  173.91    1.99  194.51    2.71
  225.58    2.34  289.42    3.83  290.06    3.85  293.74    4.37  295.96       5
  307.62       6
#Mann= 3 , 0 , 0
       0    .045       0  110.73    .035       0   141.4    .045       0
Bank Sta=110.73,141.4
XS Rating Curve= 0 ,0
Exp/Cntr=0.3,0.1

Type RM Length L Ch R = 1 ,643.93  ,18.5,18.5,18.5
XS GIS Cut Line= 6
      345020.207     5423888.515      345062.663     5423877.635
      345112.553     5423854.966       345156.37     5423856.481
      345202.613     5423864.663      345299.799     5423913.027
#Sta/Elev= 23
       0       6   43.83     4.8   82.83    3.52   84.39     3.6   90.55    3.45
   93.71     3.6   96.49    3.49   99.05     2.3  100.98    1.24  116.38    1.16
  120.59     .74  121.03     .98  126.17     .91  126.63     .95  127.49   1.304
  131.82    3.03  137.63    2.93   161.4    2.98  216.04    2.34  222.38    2.42
  273.59    3.62  285.96       5  297.99       6
#Mann= 3 , 0 , 0
       0    .045       0  100.98    .035       0  127.49    .045       0
#XS Ineff= 2 , 0
       0  100.64     3.6  122.85       0    3.14
Permanent Ineff=
       F       F
Bank Sta=100.98,127.49
XS Rating Curve= 0 ,0
Exp/Cntr=0.5,0.3

Type RM Length L Ch R = 3 ,635     ,,,
Node Photo=..\..\..\Corner Brook\Windshield Survey\CB photos\P1000637.JPG
BEGIN DESCRIPTION:
Main Street (Structure #2106)
END DESCRIPTION:
Bridge Culvert--1,0,-1,-1, 0
Deck Dist Width WeirC Skew NumUp NumDn MinLoCord MaxHiCord MaxSubmerge Is_Ogee
0.6,17.2,1.4,0, 22, 23, 3.14, , 0.98, 0, 0,0,,
   43.83   65.68   93.87   96.18  100.64  100.65  100.78  102.15  104.91  108.27
  112.25  115.06  119.25  122.84  122.85  125.95   126.1  126.33  130.19  134.06
  137.78  291.32
     4.8       4    3.61     3.6    3.64    3.64    3.78    3.78    3.76    3.74
    3.69    3.68    3.63    3.61    3.61    3.58    3.58    3.32    3.32    3.24
    3.14       4
                                      .5     2.3     2.3     2.3     2.3     2.3
     2.3     2.3     2.3     2.3      .5
                
   53.24    67.7      98  101.66  101.83  102.08  102.09  105.03  107.56  108.29
  111.66  114.33  117.57  119.22  124.09  127.39   127.4  128.38  132.75  132.95
  135.22  162.87  269.35
    4.52       4     3.7     3.7    3.78    3.78    3.78    3.78    3.78    3.75
    3.73    3.72     3.7    3.68    3.64    3.58    3.58    3.58    3.54    3.33
    3.33       3       4
                                              .5     2.3     2.3     2.3     2.3
     2.3     2.3     2.3     2.3     2.3     2.3      .5
                        
Pier Skew, UpSta & Num, DnSta & Num=  ,74.08, 2 ,75.34, 2 , 0 , 0 , 0 ,,
      .6      .6
       0     2.3
      .6      .6
       0     2.3
BR Coef=-1 , 0 , 0 ,, 0 ,,,0.8,-1,,0,
WSPro=,,,, 1 ,,,, 0 ,,,, 0 ,,,,-1 ,-1 ,-1 , 0 , 0 , 0 , 0 , 0
BC Design=,, 0 ,, 0 ,,,,,,
BC Use User HTab Curves=0
BC User HTab FreeFlow(D)= 0

Type RM Length L Ch R = 1 ,629.03  ,19.38,20.51,16.71
XS GIS Cut Line= 6
      345020.547     5423889.083      345060.955     5423882.403
      345089.695     5423872.316       345168.66     5423875.915
      345255.616     5423916.628      345265.717     5423928.885
#Sta/Elev= 24
       0       6   40.96    4.93   86.01    3.53   88.63    3.64    97.9    3.55
   98.68    3.41   99.22     2.3  104.25    1.52  105.05    1.49  105.33    1.32
  105.96    1.02  112.56    1.21  113.76     1.1     117    1.13     126     .83
  126.52     .91  127.79    1.32  131.98    3.13  133.29     3.2  210.29    2.35
  217.57     3.1  225.88    2.76  246.48    3.37  262.36       5
#Mann= 3 , 0 , 0
       0    .045       0  105.33    .035       0  127.79    .045       0
#XS Ineff= 2 , 0
       0  102.08     2.8   127.4       0     2.8
Permanent Ineff=
       F       F
Bank Sta=105.33,127.79
XS Rating Curve= 0 ,0
Exp/Cntr=0.5,0.3

Type RM Length L Ch R = 1 ,608.52  ,41.15,38.4,36.15
XS GIS Cut Line= 6
      345020.472     5423889.988      345061.819     5423890.967
      345102.693     5423890.907      345177.941      5423897.73
      345254.053     5423918.189      345265.011     5423928.885
#Sta/Elev= 22
       0       6   41.36    5.04   45.94       5   49.74    4.79    67.8    4.29
   78.37    3.64   87.72    3.42   89.41    2.52      91     2.6   95.94    2.08
   98.56   1.668   103.7     .86  114.64   1.652  127.39    2.56  140.25    2.74
  197.16    2.33  208.45    3.77   210.4     3.8  223.29       3   236.6    3.36
  237.21       4  251.92       5
#Mann= 3 , 0 , 0
       0    .045       0   98.56    .035       0  114.64    .045       0
Bank Sta=98.56,114.64
XS Rating Curve= 0 ,0
Exp/Cntr=0.3,0.1

Type RM Length L Ch R = 1 ,570.12  ,24.66,34.29,42.16
XS GIS Cut Line= 3
      345060.639     5423923.096      345070.954     5423931.842
      345264.424     5423933.617
#Sta/Elev= 30
       0       6    6.11    4.91   12.82    4.48   17.49     3.6   19.63    3.56
   40.62    2.34    58.1    2.64   59.04    2.61    69.2    1.28    73.2     .81
   73.78     .84   78.27    1.11   81.71   1.277   92.91    1.82   94.33    1.89
   95.97    1.93   99.84    2.22  101.05    2.23  106.61    2.53  110.05    2.46
  129.57    2.36  143.11    2.38  154.45    2.42  163.57    2.43  188.48    3.04
  189.63    3.07  200.02    3.38  200.77    3.41   203.1    4.24     207       5
#Mann= 3 , 0 , 0
       0    .045       0    69.2    .035       0   81.71    .045       0
Bank Sta=69.2,81.71
XS Rating Curve= 0 ,0
Exp/Cntr=0.3,0.1

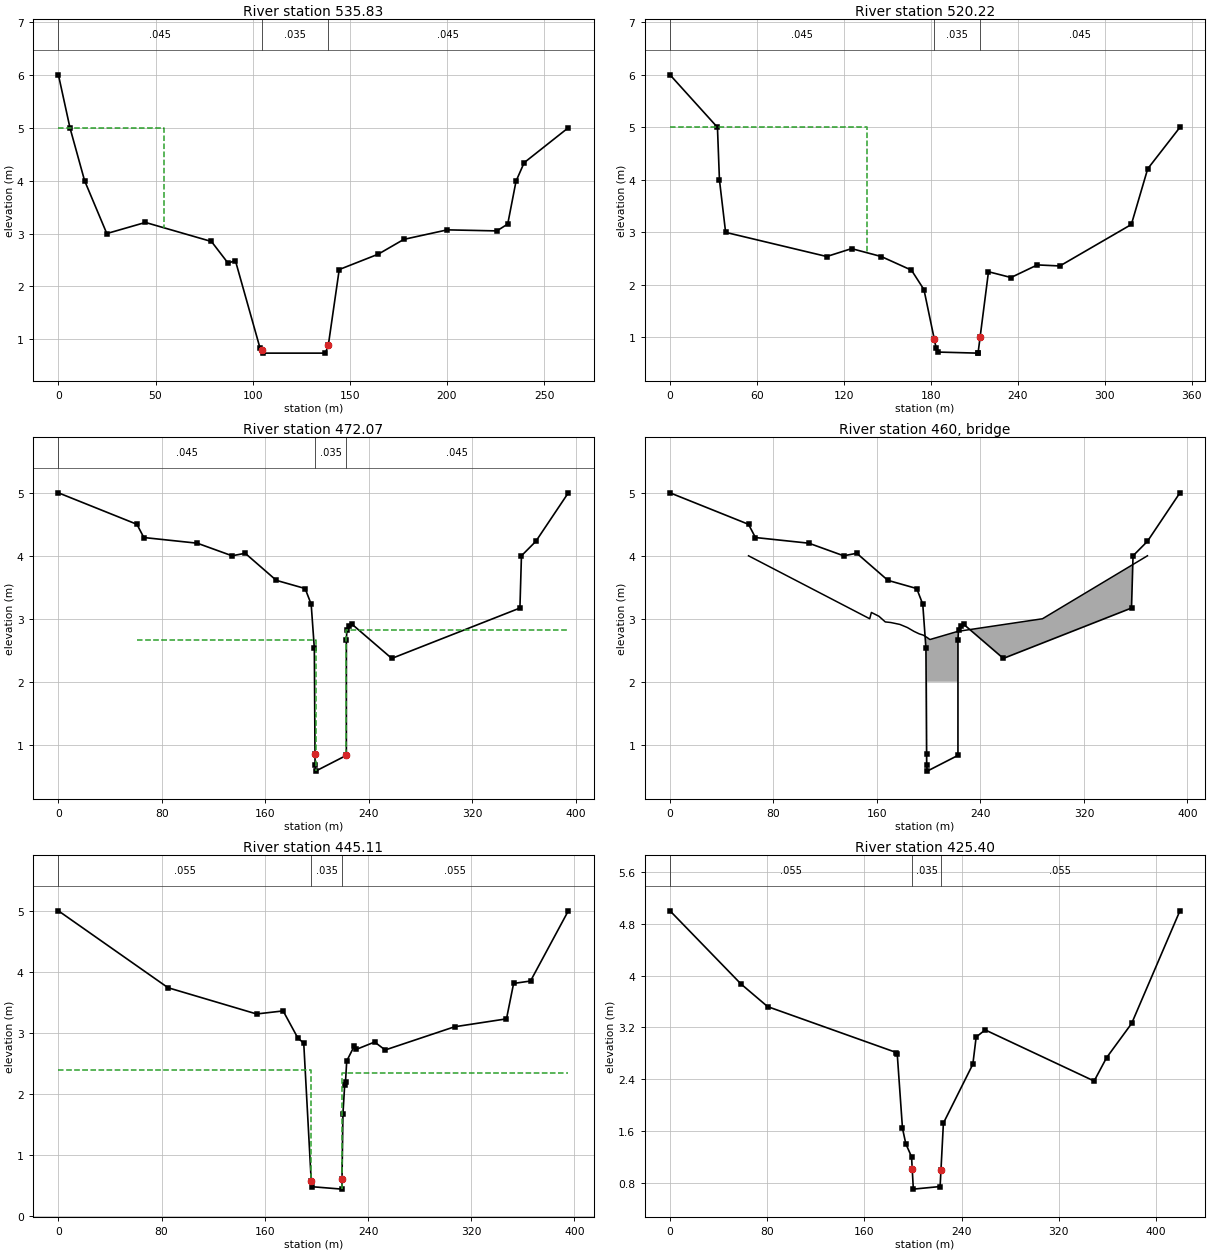
Type RM Length L Ch R = 1 ,535.83  ,15.48,15.61,15.92
XS GIS Cut Line= 6
      345041.667     5423921.564      345048.939     5423951.247
      345097.825      5423955.91      345179.627     5423978.872
      345254.305     5423970.477      345277.023      5423969.84
#Sta/Elev= 22
       0       6    5.94       5   13.47       4   24.91       3   44.79    3.21
   78.78    2.85   87.35    2.44    91.1    2.49  103.75     .84  104.68     .79
  105.54     .74  137.47     .74  138.99      .9  144.57    2.32  164.63    2.61
  177.83    2.89  200.21    3.07  225.72    3.05  231.31    3.18  235.59    3.99
  239.78    4.34  262.51       5
#Mann= 3 , 0 , 0
       0    .045       0  104.68    .035       0  138.99    .045       0
#XS Ineff= 2 , 0
       0    54.3       5               0
Permanent Ineff=
       F       F
Bank Sta=104.68,138.99
XS Rating Curve= 0 ,0
Exp/Cntr=0.3,0.1

Type RM Length L Ch R = 1 ,520.22  ,48.43,48.15,48.46
XS GIS Cut Line= 6
      344948.158     5423933.212      344970.145     5423938.241
      344987.893     5423961.271      345093.136     5423970.747
      345200.729     5424001.107      345276.787     5423972.194
#Sta/Elev= 22
       0       6   32.75       5   34.12       4   38.38       3  108.19    2.54
  125.31    2.69  145.78    2.54  166.66    2.28  175.28    1.91  182.41    .966
  183.66      .8  185.21     .72  212.24      .7  212.62      .7  214.06    1.01
  219.82    2.25  235.36    2.14  253.53    2.38  269.09    2.36  318.43    3.15
  329.71    4.21  351.95       5
#Mann= 3 , 0 , 0
       0    .045       0  182.41    .035       0  214.06    .045       0
#XS Ineff= 2 , 0
       0   135.9       5               0
Permanent Ineff=
       F       F
Bank Sta=182.41,214.06
XS Rating Curve= 0 ,0
Exp/Cntr=0.3,0.1

Type RM Length L Ch R = 1 ,472.07  ,32.1,32.1,32.1
Node Photo=..\..\..\Corner Brook\Windshield Survey\CB photos\Google\2105B US.jpg
XS GIS Cut Line= 6
      344913.183     5424005.048      344973.871     5424005.016
      345091.797     5424012.044      345176.198      5424044.35
      345267.404      5424085.01      345291.031       5424093.5
#Sta/Elev= 23
       0       5   60.69     4.5   66.02    4.29  107.34     4.2  134.23       4
  144.38    4.04  168.43    3.61  190.71    3.48  195.39    3.23  197.83    2.53
  198.34    .845  198.39     .68  198.84     .58  222.58     .83  222.59    2.67
  223.01    2.82  224.66    2.89  227.14    2.91  257.68    2.37  356.74    3.17
  357.92       4  369.06    4.23  394.16       5
#Mann= 3 , 0 , 0
       0    .045       0  198.34    .035       0  222.58    .045       0
#XS Ineff= 2 , 0
   60.69  198.89    2.67  222.52   60.69    2.82
Permanent Ineff=
       F       F
Bank Sta=198.34,222.58
XS Rating Curve= 0 ,0
Exp/Cntr=0.5,0.3

Type RM Length L Ch R = 3 ,460     ,,,
Node Photo=..\..\..\Corner Brook\Windshield Survey\CB photos\P1000633.JPG
BEGIN DESCRIPTION:
Lewin Parkway (Structure 2105B)
END DESCRIPTION:
Bridge Culvert--1,0,-1,-1, 0
Deck Dist Width WeirC Skew NumUp NumDn MinLoCord MaxHiCord MaxSubmerge Is_Ogee
2.1,28.4,1.67,0, 18, 21, 3.52, , 0.98, 0, 0,0,,
   60.69  154.38  155.66  161.48  166.39  170.71  177.69  183.54  188.55  192.66
  195.76  198.89   198.9  200.91  222.51  222.52  287.92  369.06
       4       3     3.1    3.04    2.95    2.94    2.91    2.86     2.8    2.76
    2.74     2.7     2.7    2.67     2.8     2.8       3       4
                                                                                
              .5       2       2       2      .5
   84.98  111.44  178.67  179.95  189.33   191.7  194.32  194.33  196.06  196.07
  201.39  206.22  212.11  217.14   219.7  219.71  220.77  220.78  223.51  226.06
  312.21
    3.74    3.53       3     3.1     2.8     2.8     3.3    3.74    3.74    3.74
    3.74    3.69    3.66    3.57    3.55    3.55    3.54    3.12    2.99    2.69
       3
                                                                      .5       2
       2       2       2       2       2      .5
        
BR Coef=-1 , 0 , 0 ,, 0 ,,,0.8,-1,,0,
WSPro=,,,, 1 ,,,, 0 ,,,, 0 ,,,,-1 ,-1 ,-1 , 0 , 0 , 0 , 0 , 0
BC Design=,, 0 ,, 0 ,,,,,,
BC Use User HTab Curves=0
BC User HTab FreeFlow(D)= 0

Type RM Length L Ch R = 1 ,445.11  ,13.64,19.71,23.59
Node Photo=..\..\..\Corner Brook\Windshield Survey\CB photos\Google\2105B DS.jpg
XS GIS Cut Line= 6
      344911.858     5424005.842       344946.03     5424012.989
      344965.103     5424028.872      345070.715      5424038.18
      345202.291     5424089.296      345290.375       5424094.5
#Sta/Elev= 23
       0       5   84.98    3.74  153.59    3.31  174.18    3.36  185.48    2.92
  190.16    2.83  195.96    .571  196.22     .48   219.7     .44  219.81    .603
  220.54    1.67  221.87    2.14  222.53     2.2  223.48    2.54  229.23    2.78
  230.94    2.73  245.11    2.85  253.29    2.72  307.04     3.1  347.31    3.23
  352.82    3.81  365.94    3.85  395.24       5
#Mann= 3 , 0 , 0
       0    .055       0  195.96    .035       0  219.81    .055       0
#XS Ineff= 2 , 0
       0  196.07     2.4   219.7       0    2.35
Permanent Ineff=
       F       F
Bank Sta=195.96,219.81
XS Rating Curve= 0 ,0
Exp/Cntr=0.5,0.3

Type RM Length L Ch R = 1 ,425.40  ,33.23,23.41,23.54
XS GIS Cut Line= 6
      344912.125       5424006.5      344941.527     5424014.313
      344951.749     5424040.729      345053.649     5424047.601
      345212.438     5424119.444      345291.579     5424095.917
#Sta/Elev= 20
       0       5   58.39    3.87   80.33    3.52  186.34    2.81  186.98    2.79
   191.3    1.64  194.05     1.4  198.77     1.2  199.32   1.012  200.23      .7
  222.27     .74  222.95     .99  224.98    1.72   249.2    2.63  251.93    3.05
  259.35    3.16  349.01    2.37  359.22    2.73  379.88    3.26   419.6       5
#Mann= 3 , 0 , 0
       0    .055       0  199.32    .035       0  222.95    .055       0
Bank Sta=199.32,222.95
XS Rating Curve= 0 ,0
Exp/Cntr=0.3,0.1

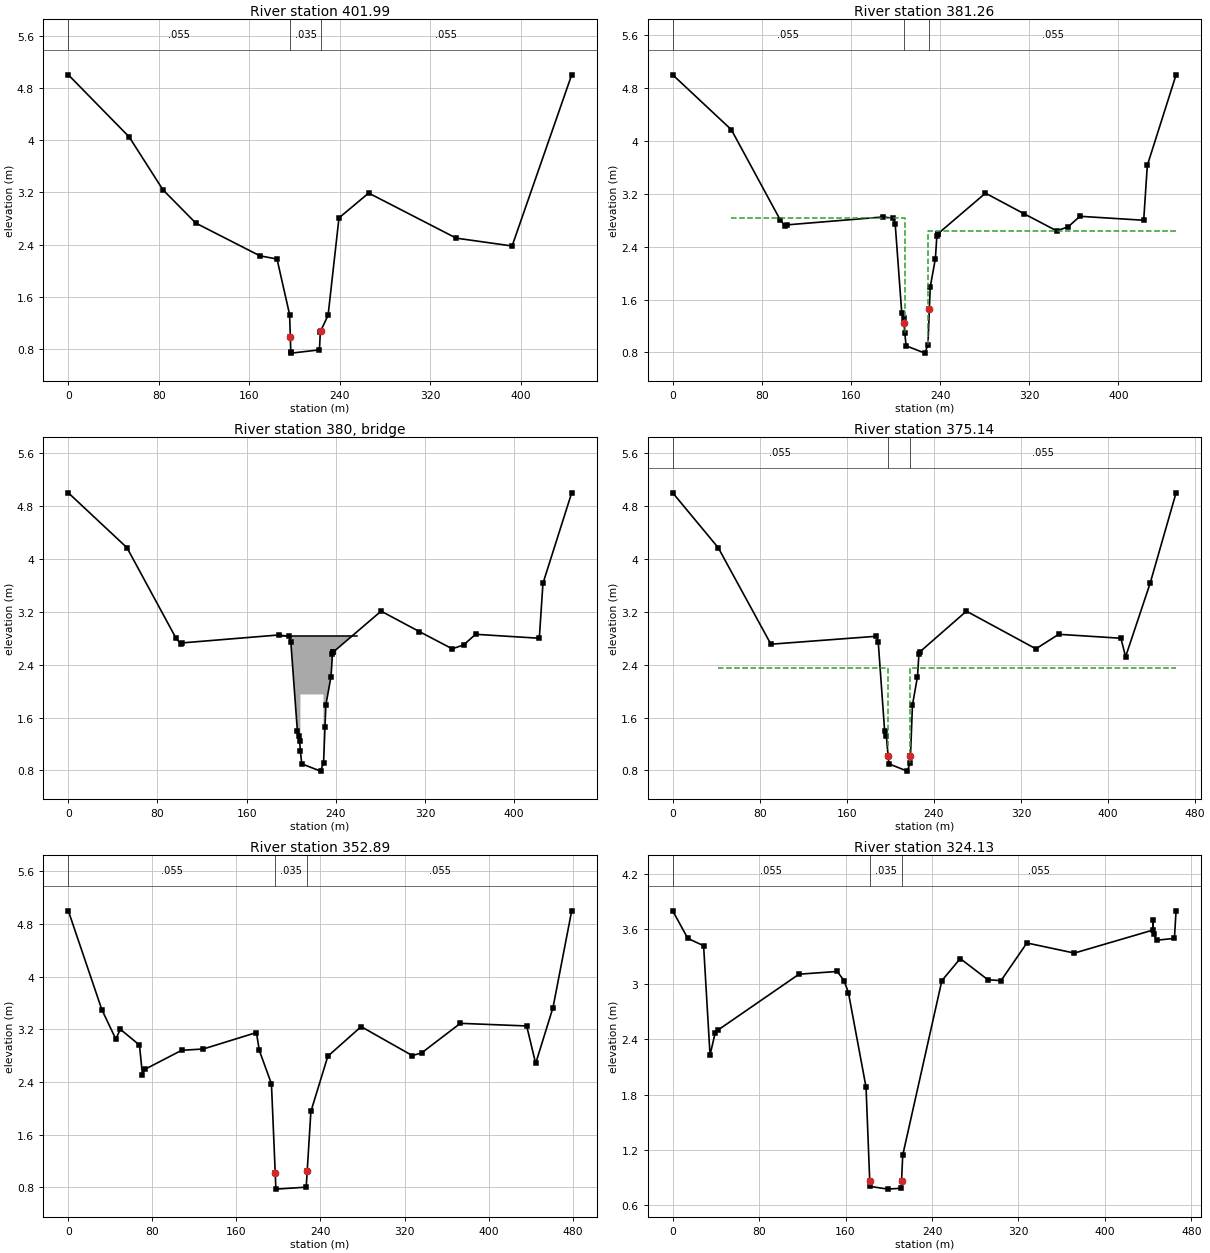
Type RM Length L Ch R = 1 ,401.99  ,24.6,26.85,18.25
XS GIS Cut Line= 6
      344906.719        5424013.      344937.818     5424017.489
      344991.758     5424070.715      345073.029      5424083.21
       345178.68     5424136.311      345306.112     5424115.619
#Sta/Elev= 19
       0       5   53.76    4.05   83.64    3.24  112.73    2.73  169.29    2.23
   184.5    2.18  195.62    1.33  196.24    .993  196.67     .76  197.16     .74
     222     .79  222.78    1.06  223.12    1.08  229.65    1.32  239.27    2.81
  265.52    3.19  342.96     2.5  392.33    2.38  445.01       5
#Mann= 3 , 0 , 0
       0    .055       0  196.24    .035       0  223.12    .055       0
Bank Sta=196.24,223.12
XS Rating Curve= 0 ,0
Exp/Cntr=0.3,0.1

Type RM Length L Ch R = 1 ,381.26  ,7.2,7.2,7.2
XS GIS Cut Line= 6
      344906.781       5424015.5      344934.904     5424020.931
      344938.538     5424044.632      344979.135     5424077.939
      345210.052     5424152.158       345309.16     5424121.075
#Sta/Elev= 29
       0       5   52.62    4.17   96.34    2.81  101.04    2.71  102.31    2.73
  189.03    2.85  197.87    2.83  199.63    2.75  205.53     1.4  207.13    1.32
   207.5    1.25  208.28    1.09  209.47      .9  226.38     .79  229.06     .92
  230.32    1.46   231.1    1.79  235.72    2.22  237.03    2.56  237.63    2.59
  237.64    2.59  280.68    3.21   315.1     2.9  344.56    2.64  354.82     2.7
  365.44    2.86  422.65     2.8  425.91    3.63  451.71       5
#Mann= 3 , 0 , 0
       0    .055       0   207.5    .035       0  230.32    .055       0
#XS Ineff= 2 , 0
   52.62  208.28    2.84  228.98   52.62    2.64
Permanent Ineff=
       F       F
Bank Sta=207.5,230.32
XS Rating Curve= 0 ,0
Exp/Cntr=0.5,0.3

Type RM Length L Ch R = 3 ,380     ,,,
Node Photo=..\..\..\Corner Brook\Windshield Survey\CB photos\P1000624.JPG
BEGIN DESCRIPTION:
Corner Brook Pulp & Paper #3 - Foot Bridge (Structure #2104)
END DESCRIPTION:
Bridge Culvert--1,0,-1,-1, 0
Deck Dist Width WeirC Skew NumUp NumDn MinLoCord MaxHiCord MaxSubmerge Is_Ogee
1.3,4,1.67,0, 6, 6, 2.64, , 0.98, 0, 0,0,,
  189.03  208.28  208.29  228.97  228.98  258.65
    2.84    2.84    2.84    2.84    2.84    2.84
      .9      .9    1.95    1.95      .9      .9
  178.22  197.47  197.48  218.16  218.17  247.84
    2.84    2.84    2.84    2.84    2.84    2.84
      .9      .9    1.95    1.95      .9      .9
BR Coef=-1 , 0 , 0 ,, 0 ,,,0.8,-1,,0,
WSPro=,,,, 1 ,,,, 0 ,,,, 0 ,,,,-1 ,-1 ,-1 , 0 , 0 , 0 , 0 , 0
BC Design=,, 0 ,, 0 ,,,,,,
BC Use User HTab Curves=0
BC User HTab FreeFlow(D)= 0

Type RM Length L Ch R = 1 ,375.14  ,22.33,22.25,22.11
XS GIS Cut Line= 6
       344904.25       5424018.5      344926.692     5424022.519
      344929.243     5424041.353      344961.126     5424079.461
      345210.563     5424161.925      345313.322     5424129.032
#Sta/Elev= 23
       0       5   41.81    4.17   90.23    2.71  187.06    2.83  188.82    2.75
  194.72     1.4  196.32    1.32  197.94   1.015  198.66      .9  215.57     .79
  218.25     .92  218.48   1.019  220.29    1.79  224.91    2.22  226.22    2.56
  226.82    2.59  269.87    3.21  333.75    2.64  354.63    2.86  411.84     2.8
  416.13    2.52  438.65    3.63  462.52       5
#Mann= 3 , 0 , 0
       0    .055       0  197.94    .035       0  218.48    .055       0
#XS Ineff= 2 , 0
   41.81  197.47    2.35  218.17   41.81    2.35
Permanent Ineff=
       F       F
Bank Sta=197.94,218.48
XS Rating Curve= 0 ,0
Exp/Cntr=0.5,0.3

Type RM Length L Ch R = 1 ,352.89  ,29.06,28.77,28.44
Node Photo=..\..\..\Corner Brook\Windshield Survey\CB photos\P1000622.JPG
BEGIN DESCRIPTION:
Grade change in stream
END DESCRIPTION:
XS GIS Cut Line= 5
      344892.938       5424029.5      344899.236      5424060.72
      344968.628     5424104.451      345216.814     5424179.417
       345318.23     5424148.638
#Sta/Elev= 26
       0       5   31.85     3.5   45.19    3.05   49.47     3.2   67.71    2.96
   70.52    2.51   72.78    2.59  107.82    2.88  128.46     2.9  179.05    3.15
  181.74    2.88  193.33    2.37  196.94   1.014  197.56     .77  226.41      .8
  227.35   1.042  230.87    1.95     247    2.79   278.7    3.24   327.4     2.8
  336.24    2.84  373.13    3.29  436.28    3.25  444.82    2.68  461.33    3.53
  479.12       5
#Mann= 3 , 0 , 0
       0    .055       0  196.94    .035       0  227.35    .055       0
Bank Sta=196.94,227.35
XS Rating Curve= 0 ,0
Exp/Cntr=0.3,0.1

Type RM Length L Ch R = 1 ,324.13  ,31.82,31.21,30.62
XS GIS Cut Line= 4
344888.6082763675424061.96929932344962.3762817385424133.18768311
345220.5648803715424209.40411377345308.7117309575424176.29370117
#Sta/Elev= 29
       0     3.8   13.94     3.5   28.59    3.42   34.54    2.23   39.29    2.47
   41.68     2.5  116.89    3.11  152.25    3.14  158.58    3.04  162.62    2.91
  178.94    1.88  182.35     .86  182.56      .8  199.09     .77  211.49     .78
   211.8    .859   212.9    1.14  249.12    3.04  266.15    3.28   291.7    3.05
  303.88    3.04  327.81    3.45  371.74    3.34  444.33    3.59  444.45     3.7
  445.07    3.55  447.87    3.48  464.37     3.5   465.9     3.8
#Mann= 3 , 0 , 0
       0    .055       0  182.35    .035       0   211.8    .055       0
Bank Sta=182.35,211.8
XS Rating Curve= 0 ,0
Exp/Cntr=0.3,0.1

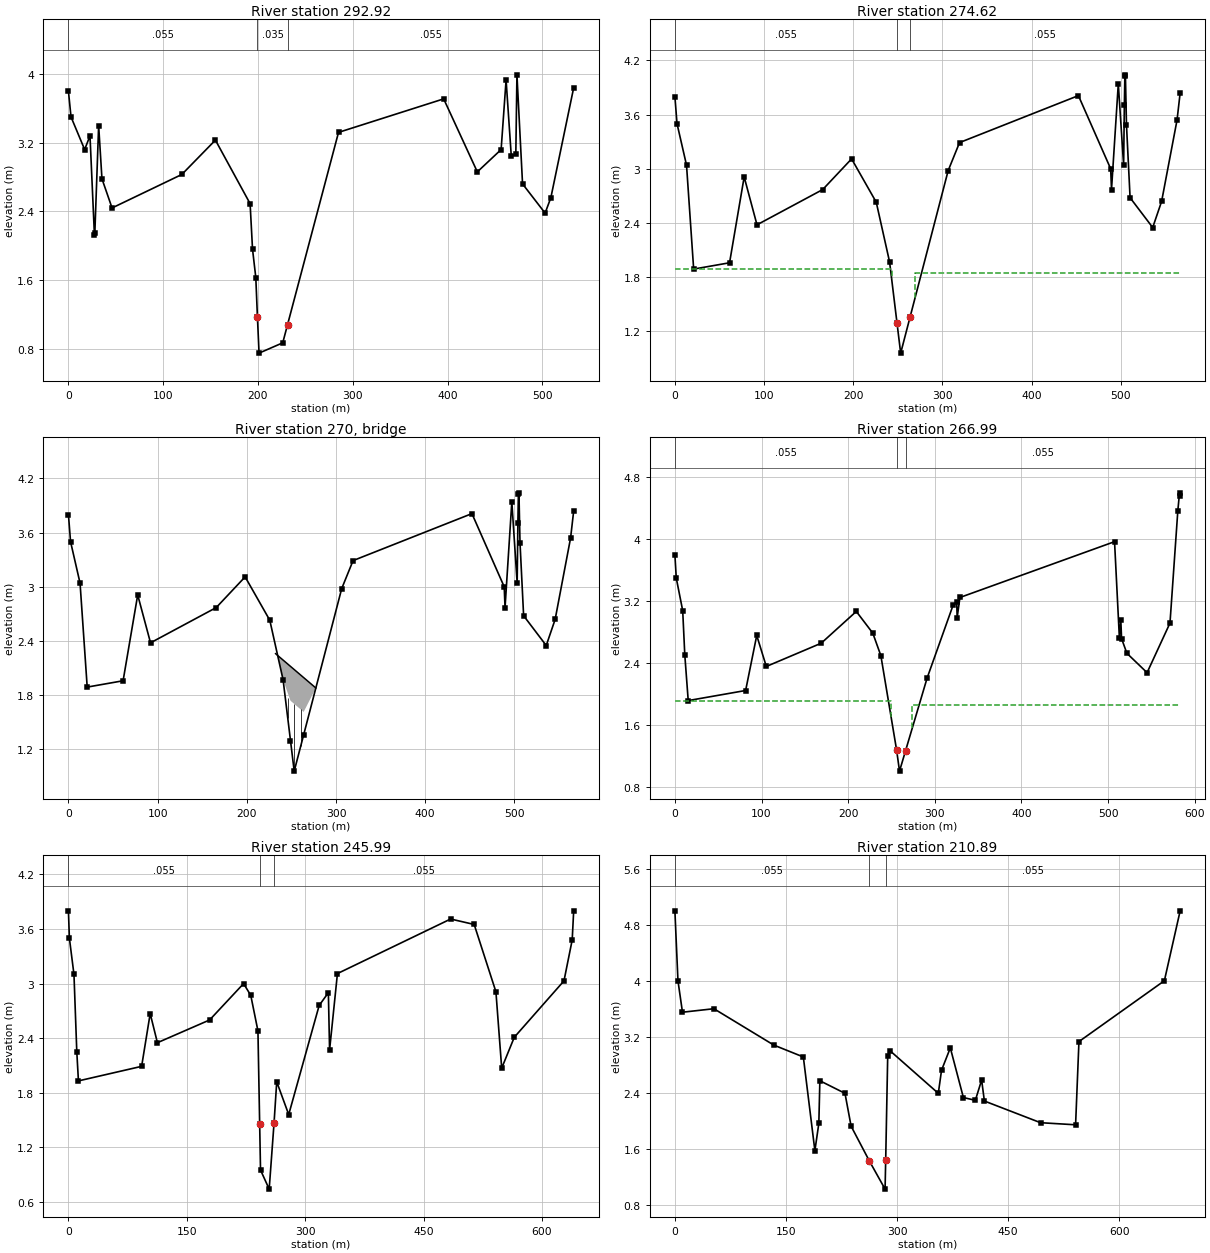
Type RM Length L Ch R = 1 ,292.92  ,27.57,18.3,8.5
XS GIS Cut Line= 6
 344882.333923345424066.41009521344951.7260742195424163.86712646
345107.3892822275424207.59771729345131.3881225595424222.67687988
345275.7416992195424249.74768066345338.8267211915424206.36010742
#Sta/Elev= 30
       0     3.8    2.73     3.5   17.11    3.12   22.75    3.28   27.45    2.12
   27.87    2.15   31.89     3.4   35.37    2.78   46.02    2.44  119.64    2.83
  155.08    3.23  191.69    2.49  194.24    1.96   197.7    1.63  199.44   1.165
  201.12     .75  226.12     .87  231.16    1.08  284.97    3.32  395.93    3.71
  431.43    2.86  456.54    3.12  461.77    3.93  467.28    3.04  472.05    3.07
  473.22    3.99  479.15    2.72  502.95    2.38  509.01    2.56   533.1    3.84
#Mann= 3 , 0 , 0
       0    .055       0  199.44    .035       0  231.16    .055       0
Bank Sta=199.44,231.16
XS Rating Curve= 0 ,0
Exp/Cntr=0.3,0.1

Type RM Length L Ch R = 1 ,274.62  ,7.58,7.62,7.75
XS GIS Cut Line= 6
344852.3264770515424074.53149414344959.4033203135424200.96429443
345105.0242919925424212.23687744345130.6458740235424224.16027832
345276.4838867195424252.34350586345341.0532836915424208.77050781
#Sta/Elev= 30
       0     3.8    2.37     3.5   13.04    3.04   21.04    1.89   61.28    1.96
   77.66    2.91   92.03    2.38  165.68    2.77  198.09    3.11  225.74    2.63
  240.67    1.97  248.95   1.298  253.11     .96  263.72   1.362  306.36    2.98
   319.1    3.29  452.36    3.81  488.54       3  489.47    2.77  497.08    3.94
  503.06    3.04  503.88    3.71  504.45    4.03  505.06    4.04  506.24    3.49
   510.3    2.68  535.66    2.35  545.66    2.64  562.95    3.54  566.43    3.84
#Mann= 3 , 0 , 0
       0    .055       0  248.95    .035       0  263.72    .055       0
#XS Ineff= 2 , 0
       0  242.99    1.89  269.06       0    1.85
Permanent Ineff=
       F       F
Bank Sta=248.95,263.72
XS Rating Curve= 0 ,0
Exp/Cntr=0.5,0.3

Type RM Length L Ch R = 3 ,270     ,,,
Node Photo=..\..\..\Corner Brook\Windshield Survey\CB photos\P1000620.JPG
BEGIN DESCRIPTION:
Corner Brook Pulp & Paper #2 - Abandoned Travelway (Structure # 2103)
END DESCRIPTION:
Bridge Culvert--1,0,-1,-1, 0
Deck Dist Width WeirC Skew NumUp NumDn MinLoCord MaxHiCord MaxSubmerge Is_Ogee
1.1,5.5,1.67,0, 2, 2, 1.85, , 0.98, 0, 0,0,,
  232.22   277.4
    2.26    1.88
    1.88     1.5
  232.22  282.27
    2.26    1.88
    1.88     1.5
Pier Skew, UpSta & Num, DnSta & Num=  ,245.86, 2 ,252.02, 2 , 0 , 0 , 0 ,,
      .3      .3
       0       2
      .3      .3
       0       2
Pier Skew, UpSta & Num, DnSta & Num=  ,253.11, 2 ,259.27, 2 , 0 , 0 , 0 ,,
      .3      .3
       0       2
      .3      .3
       0       2
Pier Skew, UpSta & Num, DnSta & Num=  ,260.36, 2 ,266.52, 2 , 0 , 0 , 0 ,,
      .3      .3
       0       2
      .3      .3
       0       2
BR Coef=-1 , 1 , 1 ,1.05, 0 ,,,0.8,-1,1.2,0,
WSPro=,,,, 1 ,,,, 0 ,,,, 0 ,,,,-1 ,-1 ,-1 , 0 , 0 , 0 , 0 , 0
BC Design=,, 0 ,, 0 ,,,,,,
BC Use User HTab Curves=0
BC User HTab FreeFlow(D)= 0

Type RM Length L Ch R = 1 ,266.99  ,14.92,21,27.42
XS GIS Cut Line= 6
344846.0750732425424077.03027344344952.7946777345424207.91009521
345099.0991210945424219.18267822345128.7905273445424228.05389404
345277.4114990235424261.79968262345351.0726928715424221.00811768
#Sta/Elev= 30
       0     3.8    1.59     3.5    9.01    3.08   11.42    2.51   15.37    1.92
   81.64    2.05   94.47    2.76  105.52    2.36  168.87    2.66  209.39    3.07
  228.44    2.79  237.74     2.5   255.9   1.283  259.27    1.01  266.33   1.276
  291.11    2.21  321.09    3.15  325.31    3.19   325.8    2.99     329    3.25
  507.48    3.97  513.06    2.73  514.72    2.96  515.57    2.72  521.74    2.53
  545.03    2.28  571.47    2.92  580.53    4.37  582.49     4.6  583.21    4.56
#Mann= 3 , 0 , 0
       0    .055       0   255.9    .035       0  266.33    .055       0
#XS Ineff= 2 , 0
       0  249.59    1.92  273.93       0    1.86
Permanent Ineff=
       F       F
Bank Sta=255.9,266.33
XS Rating Curve= 0 ,0
Exp/Cntr=0.5,0.3

Type RM Length L Ch R = 1 ,245.99  ,31.94,35.1,38.27
XS GIS Cut Line= 5
      344843.574      5424078.28      344954.227     5424218.843
       345109.89     5424250.704      345296.811     5424309.428
      345384.333      5424248.83
#Sta/Elev= 30
       0     3.8     1.2     3.5    7.02     3.1    10.6    2.25   12.67    1.93
   92.75    2.09  103.58    2.67  112.74    2.35  178.89     2.6  221.94       3
  231.03    2.87  240.11    2.48  242.29   1.458  243.38     .95  254.36     .74
  260.54    1.47  263.91    1.92   279.1    1.56  317.69    2.76  329.35     2.9
  330.88    2.27  340.82    3.11  484.25    3.71  514.08    3.65  541.63    2.91
  548.95    2.07  564.92    2.41  627.86    3.03  638.27    3.48  640.16     3.8
#Mann= 3 , 0 , 0
       0    .055       0  242.29    .035       0  260.54    .055       0
Bank Sta=242.29,260.54
XS Rating Curve= 0 ,0
Exp/Cntr=0.3,0.1

Type RM Length L Ch R = 1 ,210.89  ,38.68,35.99,33.1
XS GIS Cut Line= 6
      344842.324     5424080.779      344906.715      5424214.47
      344933.596     5424244.456      345101.138     5424290.061
      345303.688     5424320.673      345404.963     5424265.697
#Sta/Elev= 28
       0       5    4.13       4   10.23    3.55   52.68     3.6  133.57    3.08
  173.47    2.91  189.06    1.57   194.4    1.96  195.79    2.57  229.71    2.39
  237.99    1.92  262.78    1.42  283.86    1.02   284.7   1.438  287.41    2.92
  290.45       3  355.75    2.39  360.11    2.72  371.98    3.04  389.61    2.33
  405.78    2.29  414.27    2.58  417.98    2.28  493.81    1.97  541.16    1.94
  545.69    3.13  661.06       4  682.38       5
#Mann= 3 , 0 , 0
       0    .055       0  262.78    .035       0   284.7    .055       0
Bank Sta=262.78,284.7
XS Rating Curve= 0 ,0
Exp/Cntr=0.3,0.1