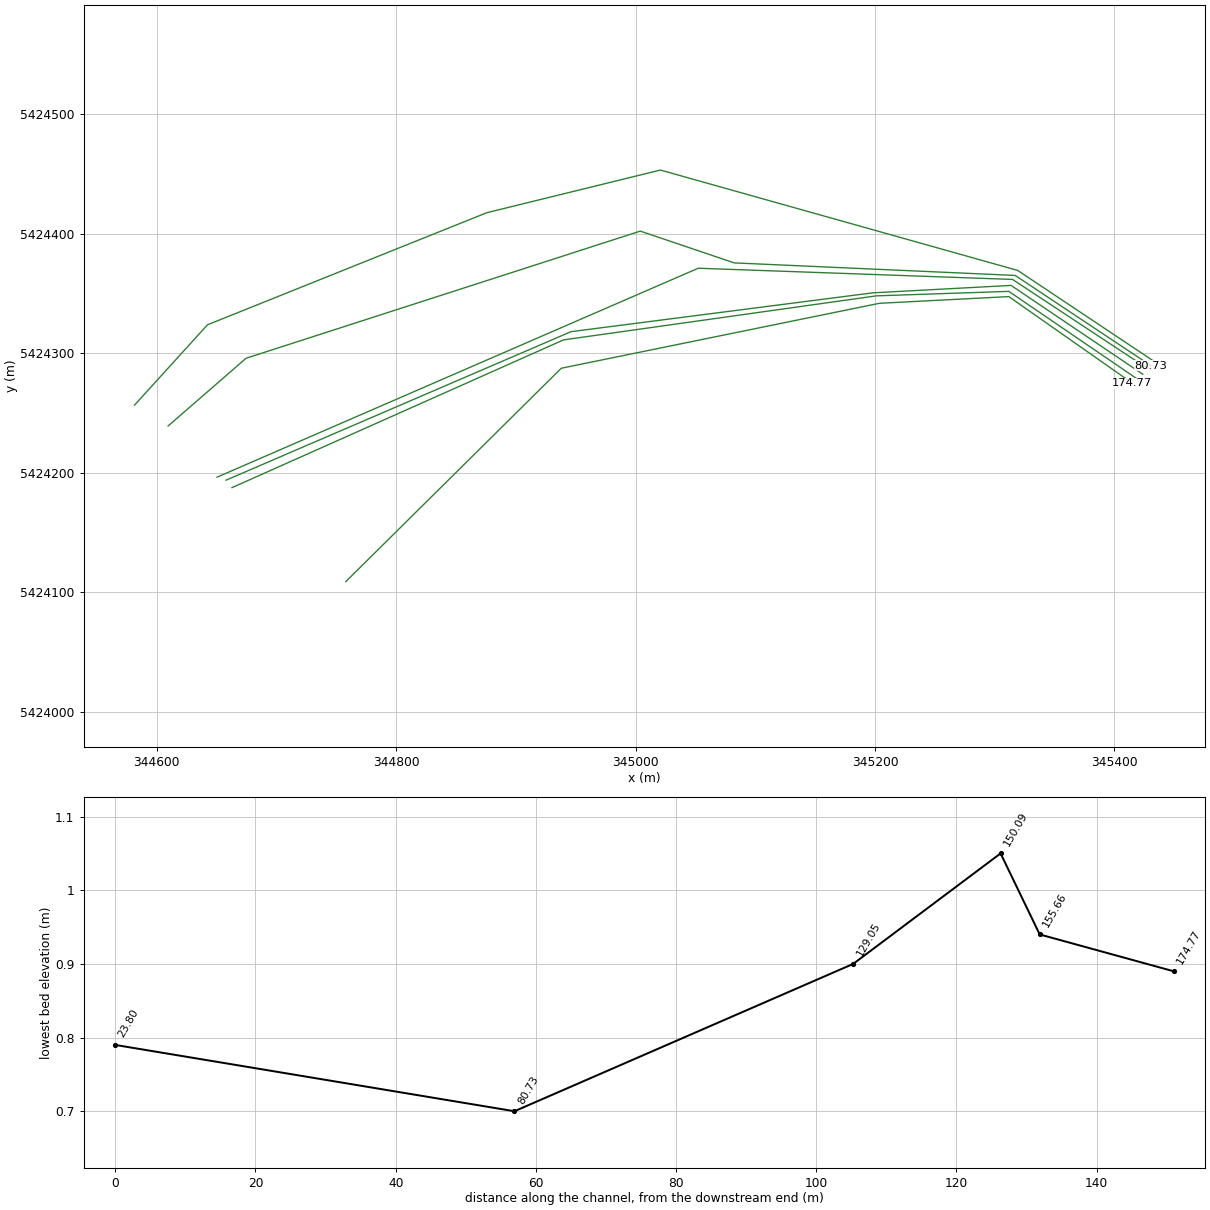
HEC-RAS study Corner_Brook2.prj: Corner_Brook2

--- Corner_Brook2.g01 (geometry) --- (continued)

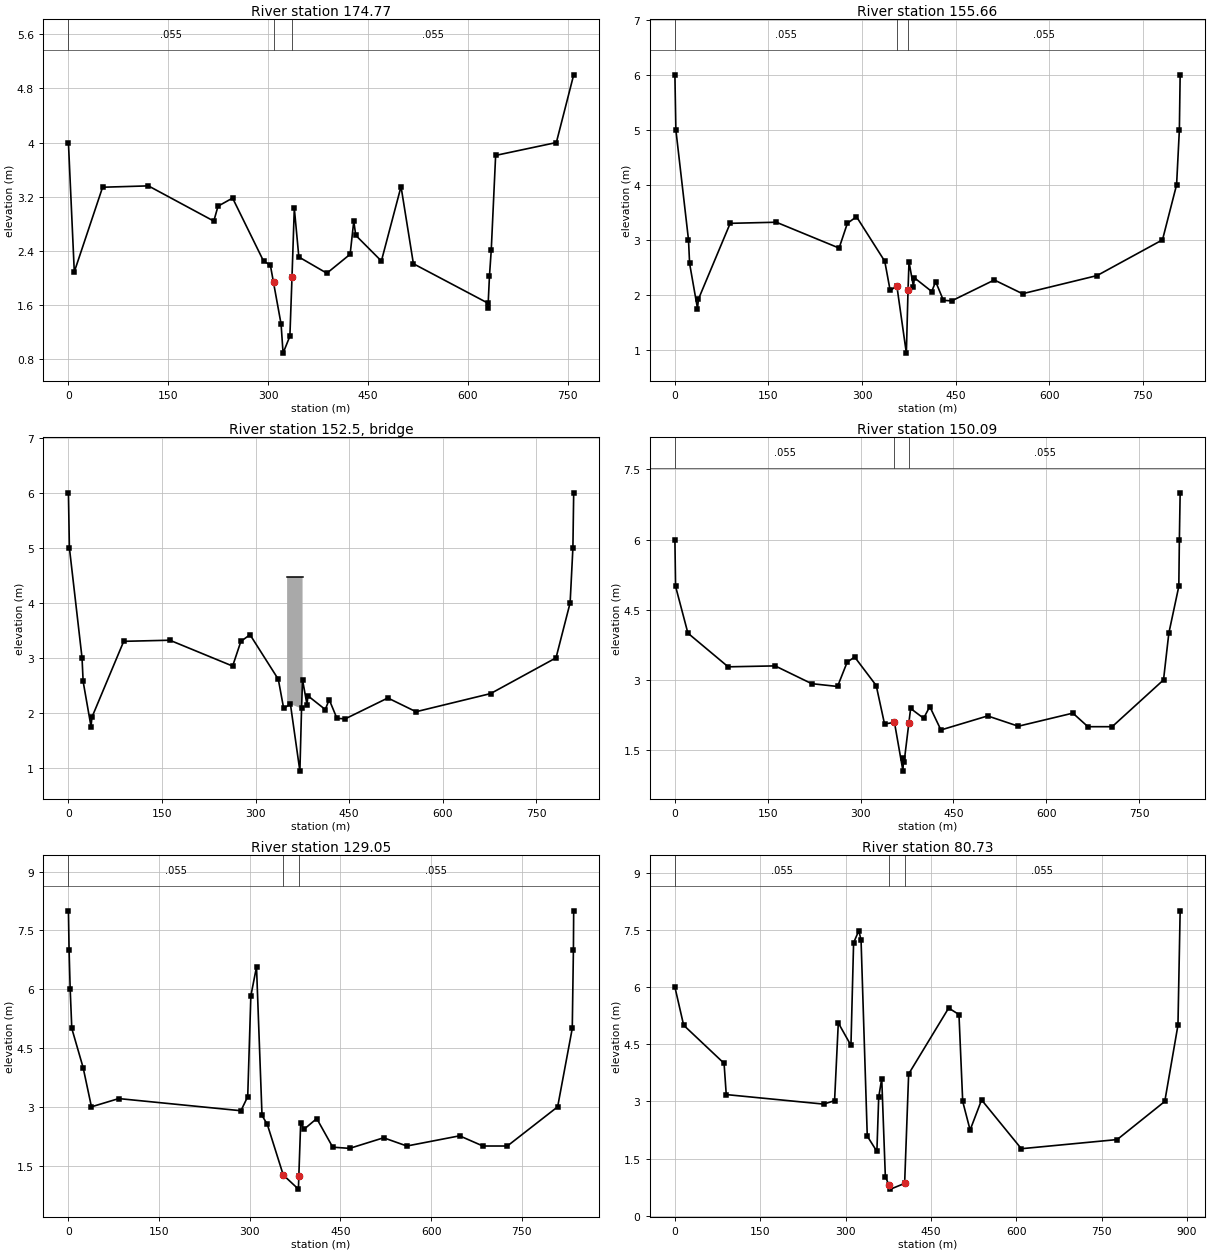
Type RM Length L Ch R = 1 ,174.77  ,22.25,19.11,16.6
XS GIS Cut Line= 5
      344757.928     5424108.891      344937.972     5424287.562
      345203.663     5424341.913      345311.815     5424347.536
      345414.965     5424275.068
#Sta/Elev= 30
       0       4    8.81    2.09   51.34    3.34  120.15    3.36  218.42    2.84
  224.78    3.06  246.67    3.18  293.16    2.25   303.4    2.19  308.15   1.934
  319.52    1.32  322.52     .89  332.76    1.14  335.93    2.01  339.41    3.03
  346.21    2.31   388.3    2.07  423.29    2.35  428.78    2.84  431.71    2.63
  470.25    2.25  499.77    3.35  518.36    2.21  629.98    1.63  630.35    1.55
  632.66    2.03  635.32    2.41  641.92    3.81  733.15       4   759.2       5
#Mann= 3 , 0 , 0
       0    .055       0  308.15    .035       0  335.93    .055       0
Bank Sta=308.15,335.93
XS Rating Curve= 0 ,0
Exp/Cntr=0.3,0.1

Type RM Length L Ch R = 1 ,155.66  ,6.01,5.58,5.11
XS GIS Cut Line= 5
      344662.905     5424187.607      344939.848     5424311.302
      345201.162     5424348.161      345311.815     5424351.909
      345420.591     5424277.567
#Sta/Elev= 30
       0       6    1.54       5    21.8       3   23.57    2.57   36.22    1.75
   37.68    1.92   88.59     3.3   162.5    3.32  263.15    2.85  276.38     3.3
  291.02    3.42  336.33    2.61  344.93    2.08  355.72    2.16  370.92     .94
  373.59    2.08  375.16     2.6  382.29    2.15  383.76    2.31  411.58    2.06
  417.88    2.24  430.26     1.9  443.51    1.89  511.86    2.27  557.05    2.02
  676.56    2.35  781.39       3  803.97       4  808.43       5  809.68       6
#Mann= 3 , 0 , 0
       0    .055       0  355.72    .035       0  373.59    .055       0
#XS Ineff= 2 , 0
       0  355.72    2.08  373.59       0    1.89
Permanent Ineff=
       F       F
Bank Sta=355.72,373.59
XS Rating Curve= 0 ,0
Exp/Cntr=0.4,0.2

Type RM Length L Ch R = 3 ,152.5   ,,,
Node Photo=..\..\..\Corner Brook\Windshield Survey\CB photos\P1000611.JPG
BEGIN DESCRIPTION:
Corner Brook Pulp & Paper #1 - Walkway and pipe rack (Structure # 2101)
END DESCRIPTION:
Bridge Culvert--1,0,-1,-1, 0
Deck Dist Width WeirC Skew NumUp NumDn MinLoCord MaxHiCord MaxSubmerge Is_Ogee
2,2.5,1.67,0, 2, 2, 4.47, , 0.98, 0, 0,0,,
  350.42  375.19
    4.47    4.47
    2.09    2.09
  353.58  378.36
    4.47    4.47
    2.09    2.09
BR Coef=-1 , 0 , 0 ,, 0 ,,,0.8,-1,,0,
WSPro=,,,, 1 ,,,, 0 ,,,, 0 ,,,,-1 ,-1 ,-1 , 0 , 0 , 0 , 0 , 0
BC Design=,, 0 ,, 0 ,,,,,,
BC Use User HTab Curves=0
BC User HTab FreeFlow(D)= 0

Type RM Length L Ch R = 1 ,150.09  ,8.19,21.03,33.59
XS GIS Cut Line= 5
      344657.904     5424193.854      344946.099     5424318.174
      345198.037     5424350.659       345313.69     5424356.907
      345423.717     5424282.565
#Sta/Elev= 30
       0       6     1.1       5   21.03       4   86.09    3.28  161.96     3.3
  221.01    2.92  262.85    2.86   278.4    3.38  290.49    3.49  325.33    2.88
  338.75    2.06  354.83    2.09  368.61    1.05  369.24    1.32  370.41    1.24
  378.07   2.077  380.93    2.39  401.95    2.18   411.9    2.43  429.89    1.93
  505.42    2.23  554.96    2.01  643.15    2.29  667.43       2  706.63       2
  789.62       3  798.21       4  814.33       5  815.24       6   816.5       7
#Mann= 3 , 0 , 0
       0    .055       0  354.83    .035       0  378.07    .055       0
#XS Ineff= 2 , 0
       0  354.83    2.06  378.07       0    1.91
Permanent Ineff=
       F       F
Bank Sta=354.83,378.07
XS Rating Curve= 0 ,0
Exp/Cntr=0.4,0.2

Type RM Length L Ch R = 1 ,129.05  ,48.12,48.32,47.32
XS GIS Cut Line= 5
      344650.402     5424196.353      344946.099     5424325.046
      345052.376     5424371.275       345314.94     5424361.904
      345427.468     5424287.562
#Sta/Elev= 30
       0       8    1.08       7     2.9       6    5.57       5   24.33       4
   38.08       3   83.26    3.21  285.42     2.9  296.64    3.26  301.83    5.83
   311.2    6.57   320.3    2.78  329.09    2.55  355.45    1.26  380.53      .9
  381.21   1.234  384.24    2.58  390.04    2.43  410.86     2.7  437.31    1.97
  465.34    1.94   521.5    2.21  559.94       2  647.23    2.26  685.77       2
  726.23       2  809.44       3  833.62       5  835.52       7  835.98       8
#Mann= 3 , 0 , 0
       0    .055       0  355.45    .035       0  381.21    .055       0
Bank Sta=355.45,381.21
XS Rating Curve= 0 ,0
Exp/Cntr=0.3,0.1

Type RM Length L Ch R = 1 ,80.73   ,61.44,56.94,50.51
XS GIS Cut Line= 6
      344609.509     5424239.208      344674.667     5424295.925
      345003.964     5424402.357      345082.434     5424375.749
      345317.145     5424365.246      345430.647     5424289.623
#Sta/Elev= 30
       0       6   15.38       5   86.42       4   90.25    3.18  261.49    2.93
  280.63    3.02  287.18    5.06   309.4    4.47  314.06    7.16  323.23    7.48
  327.16    7.23   338.1    2.09  354.99    1.69  358.19    3.11  363.51     3.6
  369.86    1.03  376.11     .81  378.91      .7  403.76     .85  410.81    3.72
  481.14    5.45  499.25    5.28  505.82       3  518.84    2.25     539    3.04
  608.87    1.76  777.28       2  860.94       3  884.12       5  887.98       8
#Mann= 3 , 0 , 0
       0    .055       0  376.11    .035       0  403.76    .055       0
Bank Sta=376.11,403.76
XS Rating Curve= 0 ,0
Exp/Cntr=0.3,0.1

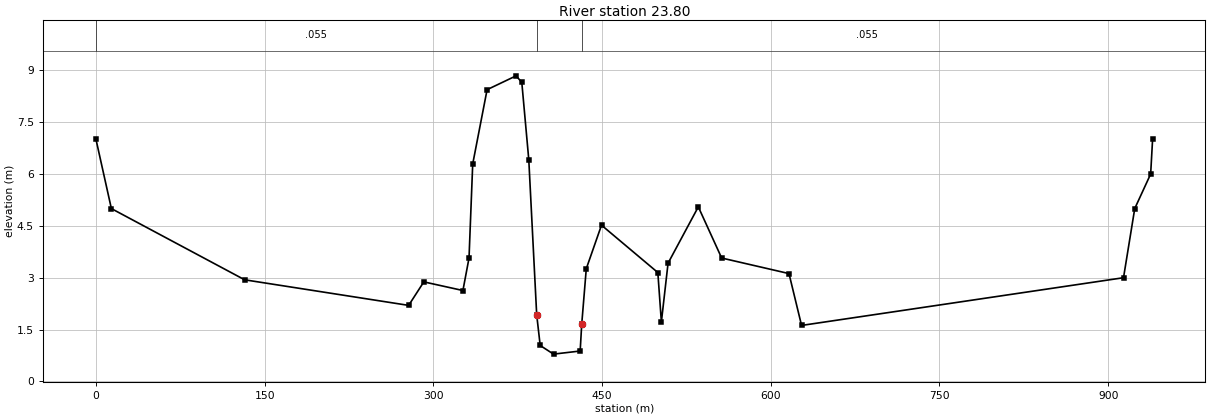
Type RM Length L Ch R = 1 ,23.80   ,26,23.8,24.26
XS GIS Cut Line= 6
      344581.484     5424256.713      344642.438     5424323.933
      344875.748     5424417.761      345020.779     5424453.472
      345319.247     5424369.447       345433.45     5424293.124
#Sta/Elev= 30
       0       7   13.67       5  132.18    2.94  278.01     2.2   291.5    2.88
  326.26    2.63  331.69    3.57  334.97    6.29  347.76    8.44  373.57    8.84
  378.62    8.65  384.84    6.41  391.86    1.93  394.97    1.04  406.83     .79
  430.52     .88  431.89    1.65  435.95    3.26  449.49    4.52  499.58    3.15
  502.73    1.72  508.67    3.42  535.57    5.05  556.33    3.57   616.2    3.12
  627.38    1.62  913.66       3  923.64       5  937.79       6  939.51       7
#Mann= 3 , 0 , 0
       0    .055       0  391.86    .035       0  431.89    .055       0
Bank Sta=391.86,431.89
XS Rating Curve= 0 ,0
Exp/Cntr=0.3,0.1

Chan Stop Cuts=-1
Use User Specified Reach Order=0
Composite Channel Slope=5

--- Corner_Brook2.g02 (geometry) ---

Geom Title=CB_with_below_waterline_ratingcurve
Program Version=4.10
BEGIN GEOM DESCRIPTION:
Created based on a TIN with 1 z tolerance
END GEOM DESCRIPTION:

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
River Reach=BellsB          ,TR001

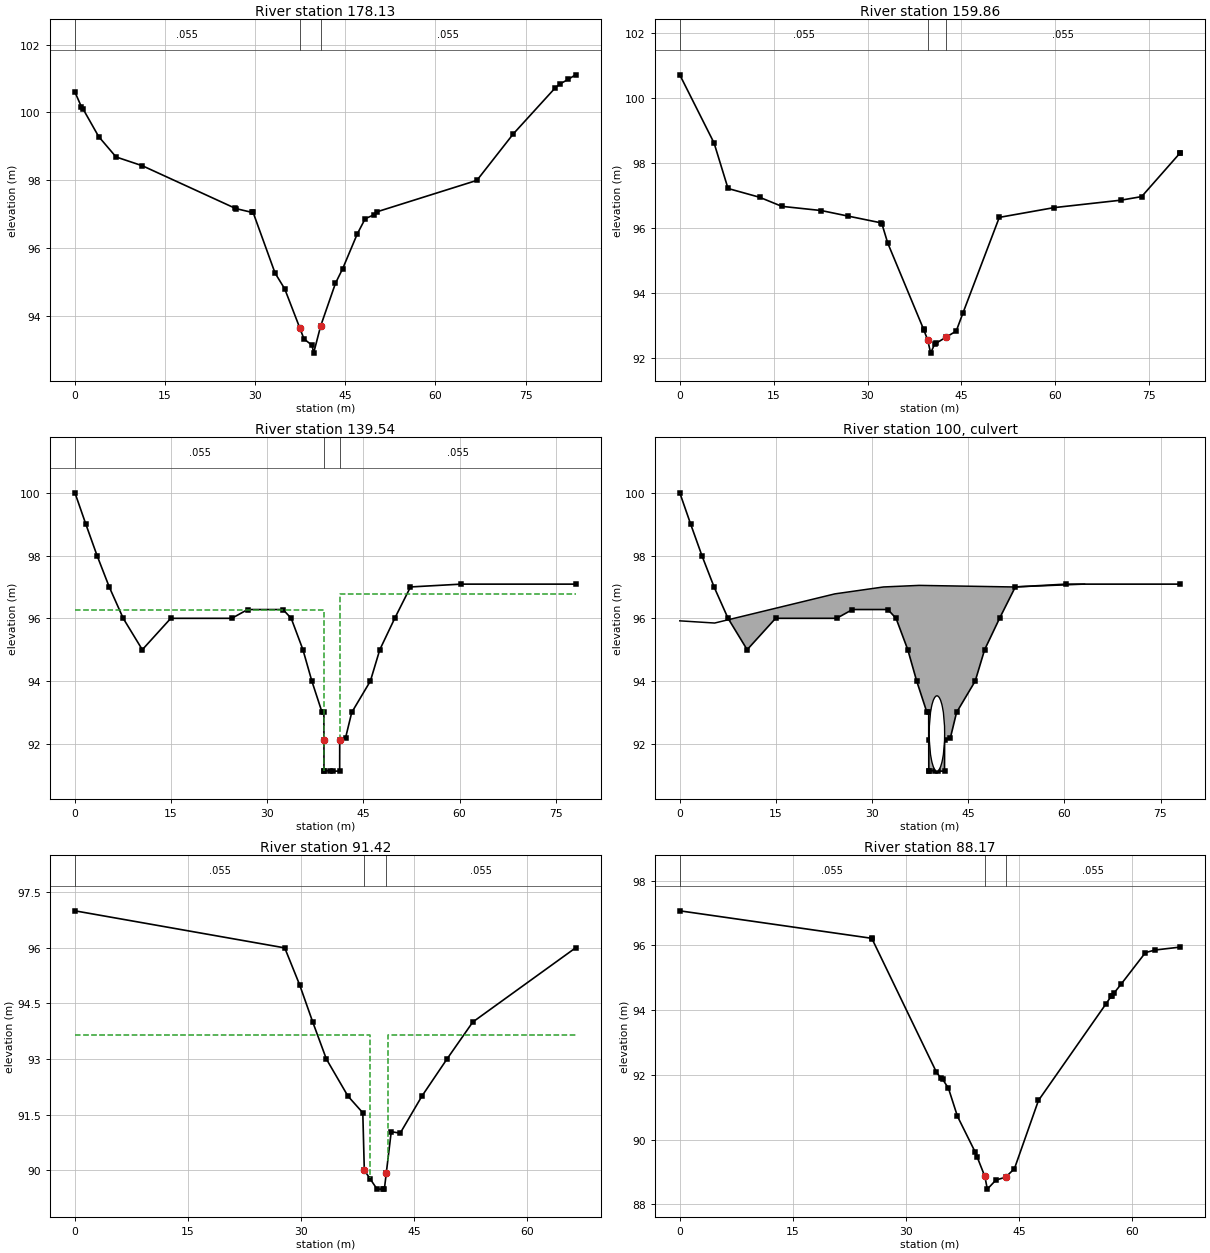
Type RM Length L Ch R = 1 ,178.13  ,18.25,18.27,18.06
XS GIS Cut Line= 6
344234.4996948245422720.95068359344238.9260864265422731.27270508
344238.0407104495422749.41009521344253.2380981455422758.25750732
344279.2062988285422758.69989014344288.9442749025422755.16088867
#Sta/Elev= 29
       0   100.6    1.07  100.17    1.36   100.1    3.95   99.29    6.84   98.69
   11.23   98.43   26.64   97.18   26.75   97.17   29.39   97.06   29.64   97.06
    33.3   95.27   34.92    94.8    37.4   93.66   38.11   93.33   39.46   93.14
   39.72   92.91   40.89  93.708   43.36   94.97   44.56    95.4   46.98   96.42
    48.3   96.87   49.69   96.98   50.19   97.07   66.89      98   72.95   99.37
    79.9  100.72   80.71  100.84   82.12  100.98   83.31  101.11
#Mann= 3 , 0 , 0
       0    .055       0    37.4    .035       0   40.89    .055       0
Bank Sta=37.4,40.89
XS Rating Curve= 0 ,0
Exp/Cntr=0.3,0.1

Type RM Length L Ch R = 1 ,159.86  ,19.69,20.32,20.7
XS GIS Cut Line= 2
344199.8156738285422748.48608398344269.362304688 5422788.0244751
#Sta/Elev= 25
       0  100.72    5.48   98.62    7.71   97.22   12.75   96.95   16.31   96.67
   22.63   96.54   26.89   96.37   32.21   96.16   32.29   96.14   33.23   95.54
   38.95   92.89      39   92.86   39.61   92.56   40.09   92.15   40.73   92.43
      41   92.46   42.58  92.644   44.18   92.83   45.24   93.38   51.06   96.33
   59.79   96.63    70.5   96.86   73.81   96.97   79.98   98.32      80   98.32
#Mann= 3 , 0 , 0
       0    .055       0   39.61    .035       0   42.58    .055       0
Bank Sta=39.61,42.58
XS Rating Curve= 0 ,0
Exp/Cntr=0.3,0.1

Type RM Length L Ch R = 1 ,139.54  ,49.06,48.13,33.83
Node Photo=..\..\..\..\Corner Brook\Windshield Survey\CB photos\P1000709.JPG
XS GIS Cut Line= 5
       344187.04     5422775.179      344200.338      5422782.01
      344217.269     5422780.434      344217.269     5422780.434
      344255.016     5422806.982
#Sta/Elev= 30
       0     100     1.7      99    3.45      98    5.35      97    7.53      96
   10.51      95   14.95      96   24.47      96   26.94   96.28   32.46   96.28
   33.74      96   35.57      95   36.96      94   38.56      93   38.84   93.02
  38.845   92.11   38.85   91.14   38.92   91.14   39.81   91.14   40.26   91.13
    41.3   91.13   41.31   92.11   42.23    92.2   43.18      93   46.09      94
   47.56      95   49.89      96   52.35      97   60.24   97.09    78.1   97.09
#Mann= 3 , 0 , 0
       0    .055       0  38.845    .035       0   41.31    .055       0
#XS Ineff= 2 , 0
       0   38.92   96.28   41.32       0   96.78
Permanent Ineff=
       F       F
Bank Sta=38.845,41.31
XS Rating Curve= 0 ,0
Exp/Cntr=0.5,0.3

Type RM Length L Ch R = 2 ,100     ,,,
Node Photo=..\..\..\..\Corner Brook\Windshield Survey\CB photos\P1000708.JPG
BEGIN DESCRIPTION:
O'Connell Drive/Mount Batten Road (Structure #2130)
END DESCRIPTION:
Bridge Culvert--1,0,-1,-1, 0
Deck Dist Width WeirC Skew NumUp NumDn MinLoCord MaxHiCord MaxSubmerge Is_Ogee
12,19.2,1.67,0, 7, 8, 95, , 0.98, 0, 0.73,0.57,,
       0    5.44    24.2   31.78   37.33   52.04   63.15
   95.92   95.85   96.78      97   97.05      97   97.09
                                                        
       0   19.48   28.32   36.51   40.19   45.24   49.91   66.38
      97   95.92   95.85      96      96   95.71   95.42      97
                                                                
BR Coef=-1 , 0 , 0 ,, 0 ,,,0.8,-1,,0,
WSPro=,,,, 1 ,,,, 0 ,,,, 0 ,,,,-1 ,-1 ,-1 , 0 , 0 , 0 , 0 , 0
Culvert=1,2.4,,44.2,0.03,0.7,1,2,2,91.13,40.12,89.49,40.27,Culvert #1  , 0 ,1.4
Culvert Bottom n=0.03
BC Design=,, 0 ,, 0 ,,,,,,
BC Use User HTab Curves=0
BC User HTab FreeFlow(D)= 0

Type RM Length L Ch R = 1 ,91.42   ,3.23,3.25,0.95
Node Photo=..\..\..\..\Corner Brook\Windshield Survey\CB photos\P1000713.JPG
XS GIS Cut Line= 6
344176.3275146485422793.74768066344187.5899047855422816.60327148
344192.6146850595422823.52929688344201.1046752935422826.99230957
344212.5405273445422816.77648926344218.2583007815422811.40887451
#Sta/Elev= 19
       0      97   27.82      96    29.8      95   31.53      94   33.34      93
    36.2      92   38.17   91.55   38.37      90   39.17  89.759   40.06   89.49
   40.82   89.49   41.03   89.49   41.29  89.933   41.94   91.04   43.13      91
   46.01      92   49.33      93   52.76      94   66.38      96
#Mann= 3 , 0 , 0
       0    .055       0   38.37    .035       0   41.29    .055       0
#XS Ineff= 2 , 0
       0   39.07   93.65   41.47       0   93.65
Permanent Ineff=
       F       F
Bank Sta=38.37,41.29
XS Rating Curve= 0 ,0
Exp/Cntr=0.5,0.3

Type RM Length L Ch R = 1 ,88.17   ,2.5,4.05,10.03
XS GIS Cut Line= 6
344174.2482910165422796.34509277344185.5106811525422819.20068359
344190.5355224615422826.12652588344199.0255126955422829.58947754
344210.4613037115422819.37371826344216.1790771485422814.00610352
#Sta/Elev= 24
       0   97.07   25.47   96.22   25.48   96.21   34.04   92.08   34.66   91.89
   34.86   91.86   35.62   91.59   36.82   90.72   39.14   89.63   39.42   89.47
   40.45  88.864   40.78   88.47   41.92   88.75   43.21   88.84   44.37    89.1
   47.56   91.21    56.5   94.19   57.23   94.44   57.28   94.45   57.55   94.52
   58.54   94.81   61.75   95.78   63.05   95.86   66.38   95.95
#Mann= 3 , 0 , 0
       0    .055       0   40.45    .035       0   43.21    .055       0
Bank Sta=40.45,43.21
XS Rating Curve= 0 ,0
Exp/Cntr=0.3,0.1

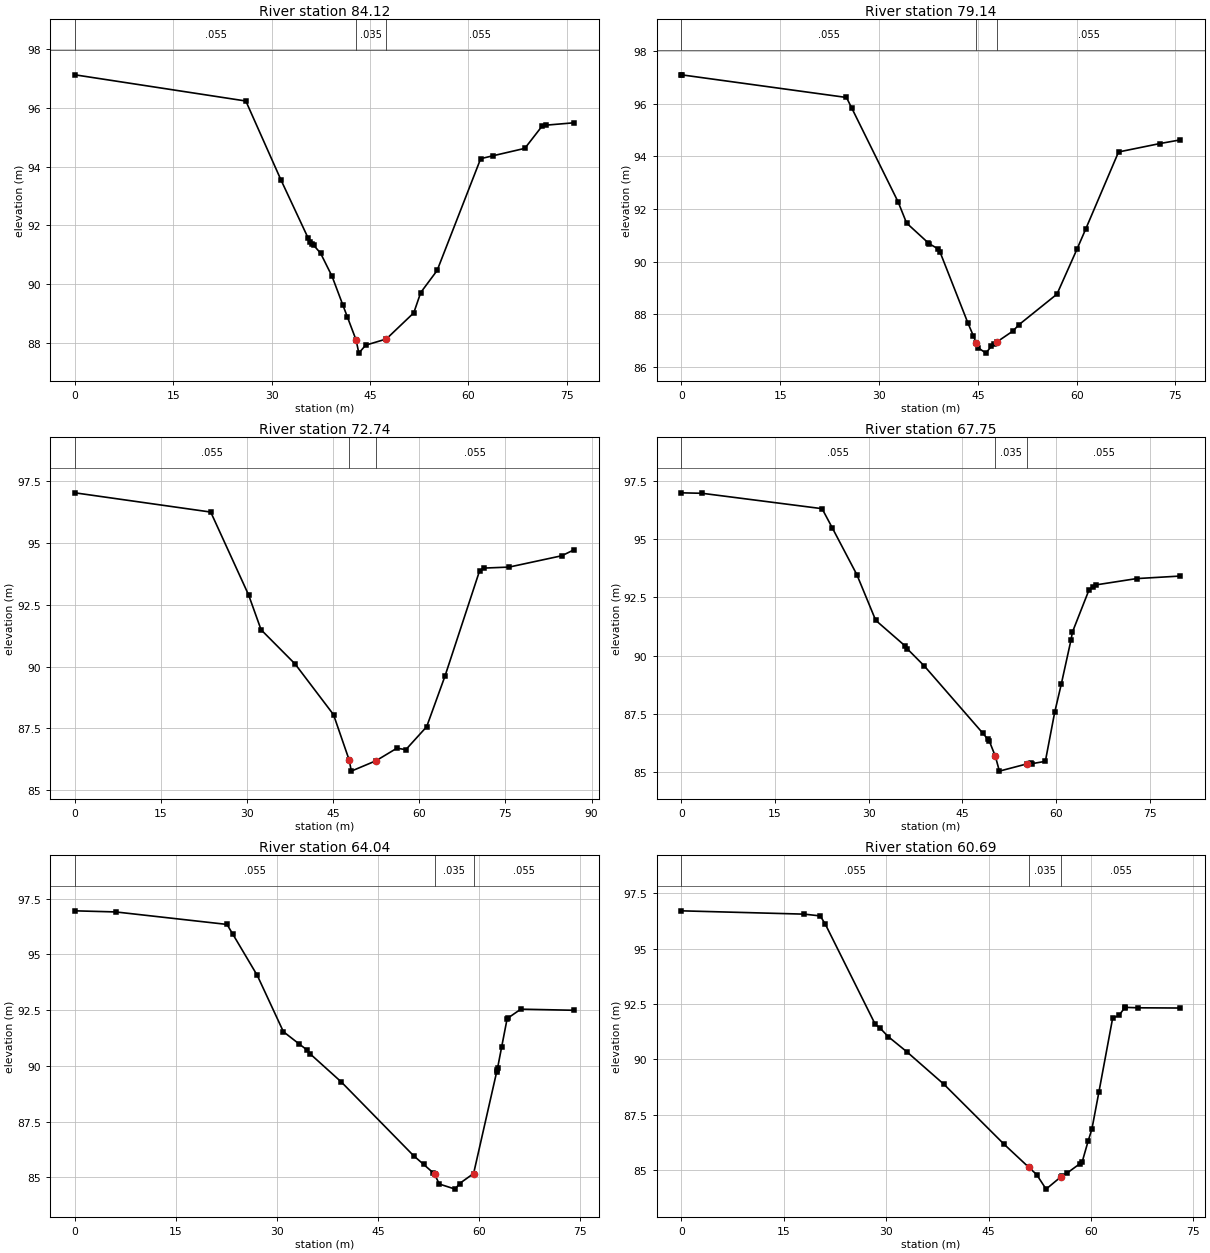
Type RM Length L Ch R = 1 ,84.12   ,3.03,4.98,8.8
XS GIS Cut Line= 6
344172.6889038095422796.34509277344187.4166870125422824.04870605
344193.3076782235422831.49407959344199.372070313 5422834.0914917
344213.0603027345422825.26068115344222.7633056645422817.64227295
#Sta/Elev= 24
       0   97.12   26.05   96.23   31.38   93.56   35.51   91.59   35.77   91.44
    36.2   91.36   36.38   91.33   37.44   91.06    39.2   90.27   40.87   89.28
   41.55   88.88   42.87  88.102   43.28   87.66   44.32   87.93   47.47   88.14
   51.66   89.03   52.72   89.72   55.22   90.47   61.86   94.27   63.76   94.37
   68.59   94.62    71.2   95.37   71.88   95.41   76.09   95.49
#Mann= 3 , 0 , 0
       0    .055       0   42.87    .035       0   47.47    .055       0
Bank Sta=42.87,47.47
XS Rating Curve= 0 ,0
Exp/Cntr=0.3,0.1

Type RM Length L Ch R = 1 ,79.14   ,5.7,6.39,8.69
XS GIS Cut Line= 6
344172.5156860355422797.38391113344184.6442871095422820.23950195
344189.4959106455422830.80151367344192.6146850595422836.86169434
 344198.505676275422838.07373047344222.416687012 5422829.4163208
#Sta/Elev= 26
       0    97.1     .01    97.1   25.05   96.24   25.87   95.83    32.9   92.27
   34.18   91.47    37.5   90.71   37.59   90.69   38.88    90.5   39.24   90.38
   43.48   87.68   44.31   87.19   44.77    86.9   45.02   86.74   46.21   86.53
   47.05   86.79   47.47   86.88   47.98   86.97   50.33   87.37   51.24   87.61
   57.01   88.77   60.07   90.49   61.37   91.24   66.36   94.17   72.64   94.49
   75.76   94.63
#Mann= 3 , 0 , 0
       0    .055       0   44.77    .035       0   47.98    .055       0
Bank Sta=44.77,47.98
XS Rating Curve= 0 ,0
Exp/Cntr=0.3,0.1

Type RM Length L Ch R = 1 ,72.74   ,2.71,4.99,10
XS GIS Cut Line= 6
344171.8225097665422799.11547852344184.1245117195422820.93212891
344188.6295166025422839.97851563344193.3076782235422843.78771973
344216.6989135745422842.22930908344227.2681274415422834.95709229
#Sta/Elev= 18
       0   97.04   23.65   96.26   30.25    92.9   32.42   91.49   38.36    90.1
   45.04   88.05   47.79  86.196   48.14   85.76   52.44   86.18   56.09   86.69
   57.64   86.63   61.27   87.56   64.46   89.61   70.49   93.88   71.28   93.99
   75.63   94.03   84.82   94.49   86.94   94.73
#Mann= 3 , 0 , 0
       0    .055       0   47.79    .035       0   52.44    .055       0
Bank Sta=47.79,52.44
XS Rating Curve= 0 ,0
Exp/Cntr=0.3,0.1

Type RM Length L Ch R = 1 ,67.75   ,2.94,3.71,5.31
XS GIS Cut Line= 5
344170.9561157235422800.32751465344182.3919067385422821.62469482
344188.1096801765422845.86547852344201.4512939455422856.25427246
344215.1395263675422858.85168457
#Sta/Elev= 27
       0   96.98    3.31   96.96   22.52    96.3   24.17   95.47   28.09   93.47
   31.11   91.51   35.87    90.4   36.19   90.28    38.9   89.55   48.29   86.66
   49.08    86.4   49.29   86.34   50.28   85.67   50.92   85.04   55.32   85.35
   55.94   85.37   56.12   85.36   58.28   85.46   59.78   87.57   60.83   88.77
   62.39   90.67   62.61      91   65.25    92.8   65.99   92.96   66.38   93.03
   72.89    93.3   79.92   93.41
#Mann= 3 , 0 , 0
       0    .055       0   50.28    .035       0   55.32    .055       0
Bank Sta=50.28,55.32
XS Rating Curve= 0 ,0
Exp/Cntr=0.3,0.1

Type RM Length L Ch R = 1 ,64.04   ,3.68,3.35,4.35
XS GIS Cut Line= 5
344169.7432861335422800.50048828344180.4859008795422821.27832031
344182.5651245125422830.97467041344185.8572998055422847.59692383
344200.5848999025422866.29711914
#Sta/Elev= 26
       0   96.95    6.05    96.9   22.56   96.34   23.39   95.92   27.06   94.05
   30.93   91.53   33.31   90.97    34.4   90.72   34.92   90.53   39.51   89.28
   50.25   85.97   51.74   85.58   53.17    85.2   53.39   85.13   54.06    84.7
   56.42   84.47   57.07   84.72   59.16   85.17   62.57   89.71   62.64   89.81
   62.73   89.92   63.32   90.84   64.14   92.12    64.2   92.13   66.17   92.54
   74.06   92.49
#Mann= 3 , 0 , 0
       0    .055       0   53.39    .035       0   59.16    .055       0
Bank Sta=53.39,59.16
XS Rating Curve= 0 ,0
Exp/Cntr=0.3,0.1

Type RM Length L Ch R = 1 ,60.69   ,4.56,3.94,4.31
XS GIS Cut Line= 5
344164.1987304695422804.13671875344179.4462890635422833.39868164
 344182.738281255422847.25067139344187.9362792975422857.12011719
344197.6392822275422868.20172119
#Sta/Elev= 27
       0   96.71   18.01   96.56   20.34   96.48   21.09    96.1    28.4   91.58
   29.05   91.43   30.29   91.03      33   90.35   38.48   88.87   47.23   86.18
   50.88   85.13   52.04    84.8   53.43   84.14   55.58   84.69   55.79   84.72
   56.44   84.85   58.39   85.29   58.71   85.36   59.59   86.31   60.14   86.85
   61.16   88.51   63.18   91.86   64.13   91.99   64.96   92.34   65.02   92.35
   66.87   92.33   73.12   92.32
#Mann= 3 , 0 , 0
       0    .055       0   50.88    .035       0   55.58    .055       0
Bank Sta=50.88,55.58
XS Rating Curve= 0 ,0
Exp/Cntr=0.3,0.1

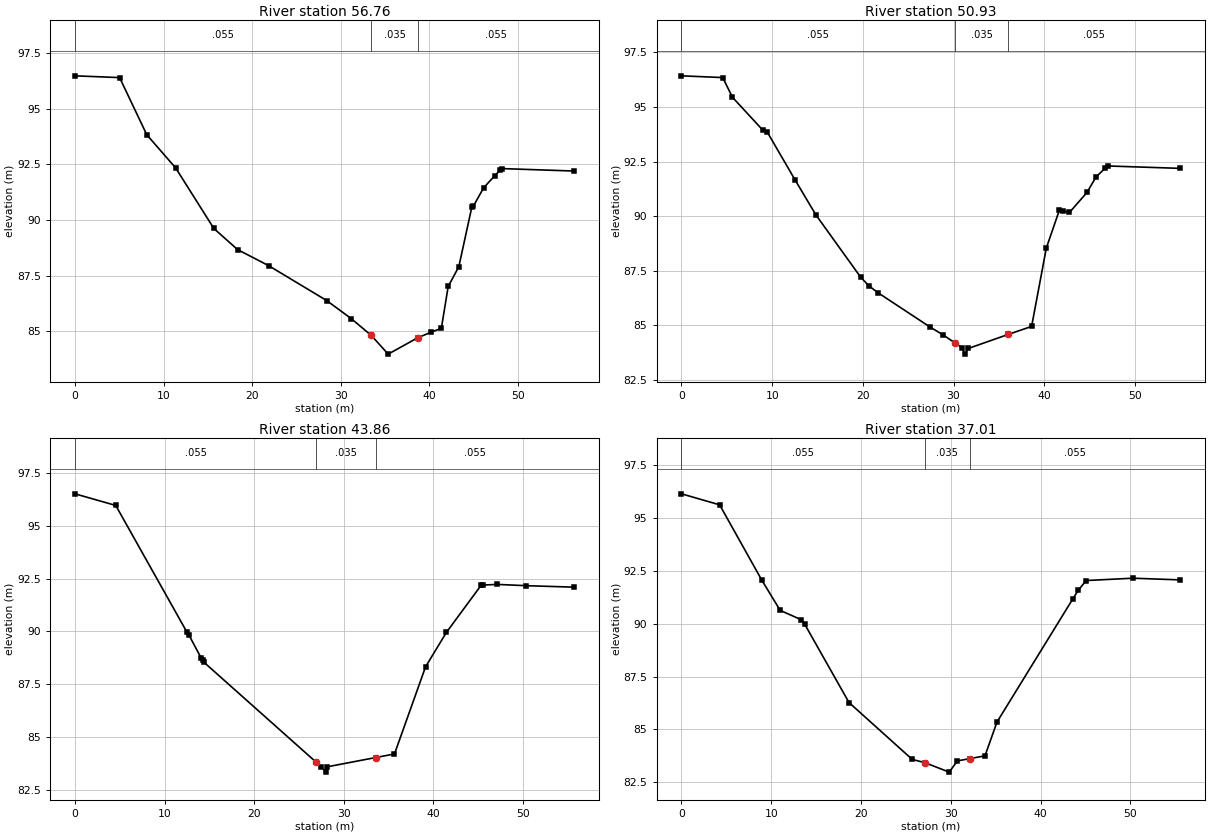
Type RM Length L Ch R = 1 ,56.76   ,7.72,5.83,4.41
XS GIS Cut Line= 4
344158.3076782235422827.16552734 344178.579895025422847.07751465
344186.7235107425422864.21929932344193.4810791025422870.10632324
#Sta/Elev= 23
       0   96.48    5.04    96.4    8.11   93.83   11.37   92.34   15.68   89.62
   18.36   88.67   21.86   87.95   28.42   86.38   31.19   85.57   33.47   84.81
   35.37   83.97   38.73   84.71   40.25   84.96   41.38   85.13   42.15   87.01
   43.35    87.9   44.82   90.58   44.99   90.62   46.16   91.45   47.39   91.98
   47.99   92.23   48.26   92.31   56.36    92.2
#Mann= 3 , 0 , 0
       0    .055       0   33.47    .035       0   38.73    .055       0
Bank Sta=33.47,38.73
XS Rating Curve= 0 ,0
Exp/Cntr=0.3,0.1

Type RM Length L Ch R = 1 ,50.93   ,7.48,7.07,7.18
XS GIS Cut Line= 3
344154.1492919925422830.97467041344182.045288086 5422862.4876709
344192.0949096685422870.62567139
#Sta/Elev= 27
       0   96.43    4.55   96.35    5.62   95.45    8.95   93.95    9.45   93.86
   12.53   91.66   14.82   90.06   19.75   87.21   20.66   86.81   21.68   86.49
   27.38   84.93   28.89   84.55   30.17  84.189   30.91   83.98   31.27   83.68
   31.63   83.94   36.01   84.58   38.61   84.95   40.23   88.54   41.68   90.29
   42.09   90.24   42.78   90.17   44.72   91.09   45.71    91.8    46.7   92.19
   47.04    92.3   55.02   92.19
#Mann= 3 , 0 , 0
       0    .055       0   30.17    .035       0   36.01    .055       0
Bank Sta=30.17,36.01
XS Rating Curve= 0 ,0
Exp/Cntr=0.3,0.1

Type RM Length L Ch R = 1 ,43.86   ,6.35,6.86,7.11
XS GIS Cut Line= 3
344148.4312744145422837.38128662344180.3126831055422869.93310547
344188.4562988285422875.99328613
#Sta/Elev= 20
       0   96.52    4.55   95.97   12.51   89.96   12.71   89.84   14.08   88.75
   14.25   88.65   14.38   88.55   26.94  83.804   27.48    83.6   27.99   83.34
   28.14   83.59   33.56   84.03   35.67    84.2   39.14   88.33   41.47   89.96
   45.36    92.2   45.56    92.2   47.15   92.23   50.35   92.17   55.71    92.1
#Mann= 3 , 0 , 0
       0    .055       0   26.94    .035       0   33.56    .055       0
Bank Sta=26.94,33.56
XS Rating Curve= 0 ,0
Exp/Cntr=0.3,0.1

Type RM Length L Ch R = 1 ,37.01   ,27.23,24.86,22.79
XS GIS Cut Line= 3
344145.4793090825422841.12591553344173.7730712895422874.27587891
 344184.958923345422878.58673096
#Sta/Elev= 19
       0   96.14    4.25   95.62    8.93   92.07   10.99   90.63   13.32   90.19
   13.73   89.97   18.66   86.27    25.7   83.58   27.09   83.43   29.82   82.98
   30.72   83.51   32.12   83.62    33.8   83.75   35.14   85.35   43.58   91.17
   44.18   91.57   45.06   92.04   50.26   92.15   55.57   92.07
#Mann= 3 , 0 , 0
       0    .055       0   27.09    .035       0   32.12    .055       0
Bank Sta=27.09,32.12
XS Rating Curve= 0 ,0
Exp/Cntr=0.3,0.1