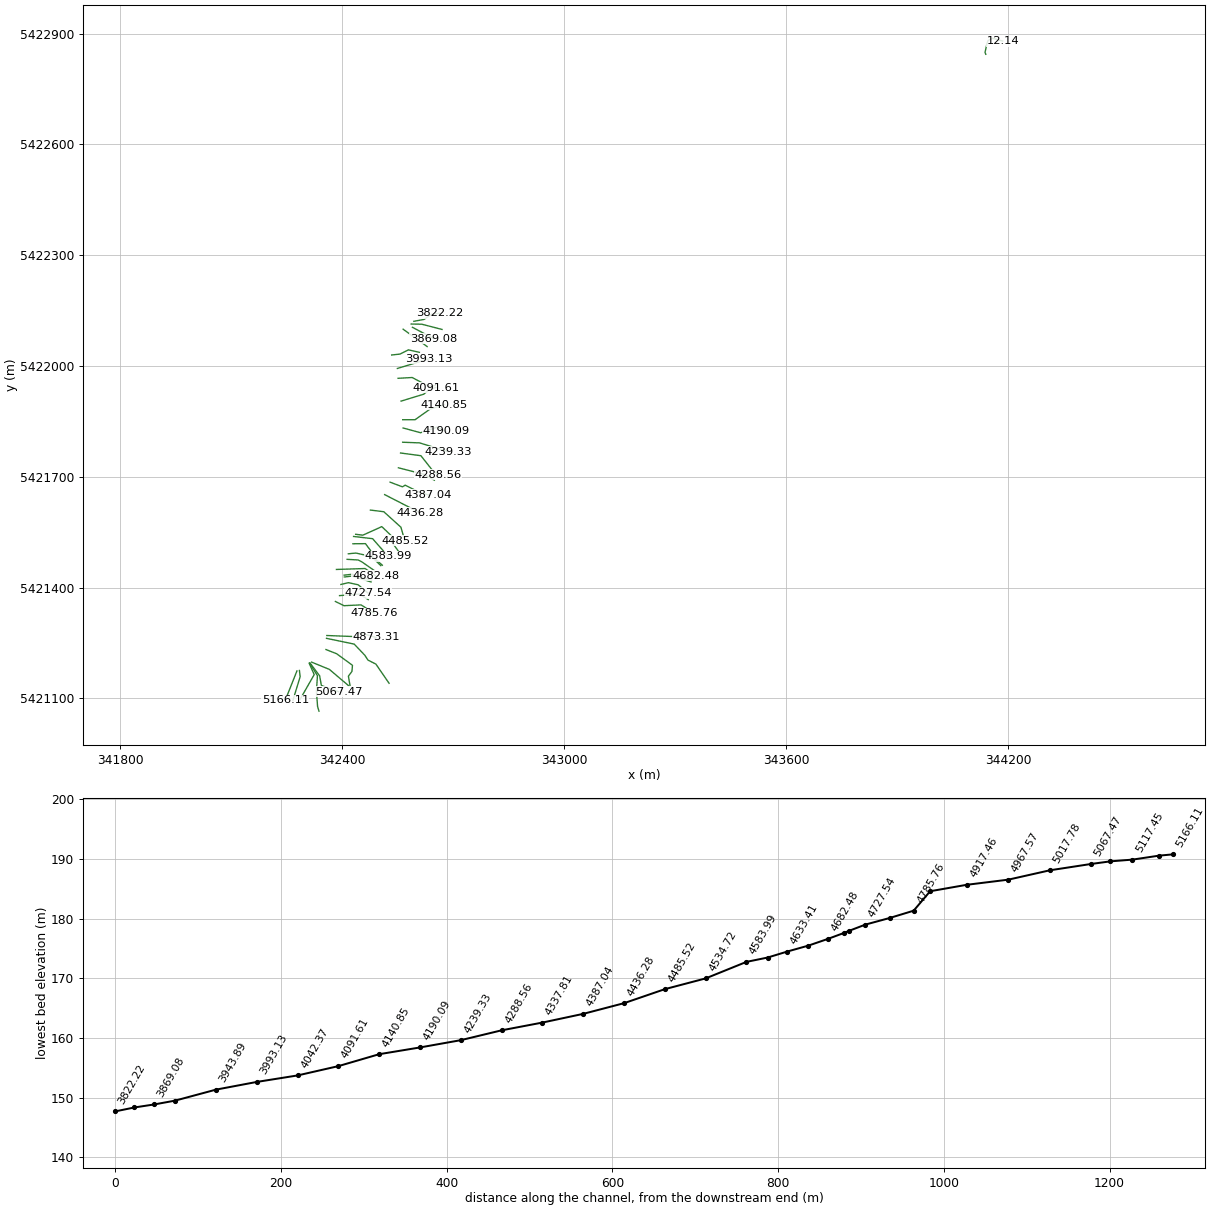
HEC-RAS study Corner_Brook2.prj: Corner_Brook2

--- Corner_Brook2.g02 (geometry) --- (continued)

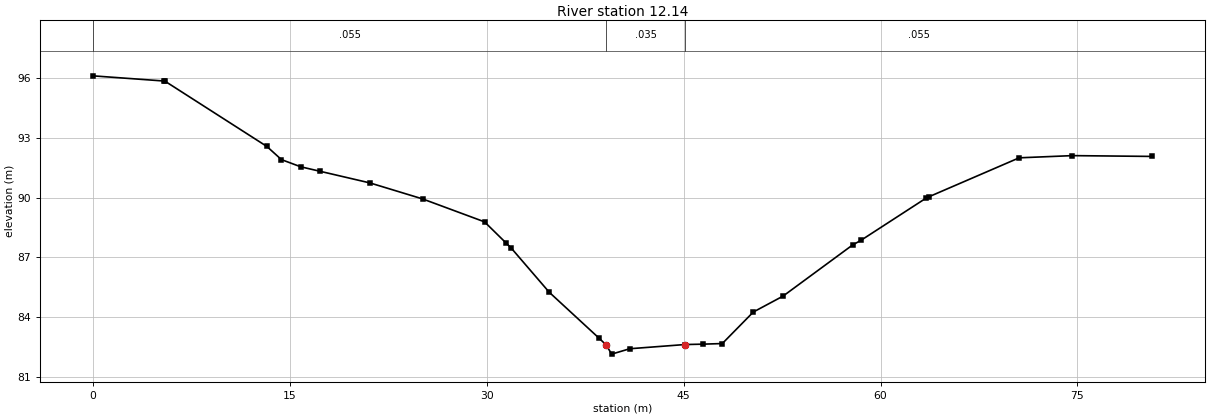
Type RM Length L Ch R = 1 ,12.14   ,4.7,12.15,6.96
XS GIS Cut Line= 6
344139.0648803715422843.84472656344136.9857177735422848.86608887
344142.5302734385422874.31890869344145.1292724615422880.89849854
344157.6044921885422887.30487061344184.6342773445422879.51330566
#Sta/Elev= 29
       0    96.1    5.43   95.84    5.48   95.84   13.26   92.56   14.37    91.9
   15.84   91.54   17.28   91.32   21.12   90.73   25.12   89.93   29.84   88.78
   31.48   87.72   31.88   87.46   34.77   85.25   38.56   82.95   39.11  82.606
   39.52   82.15    40.9   82.42   45.09   82.63   46.48   82.65   47.95   82.68
   50.31   84.26   52.58   85.06   57.87   87.62    58.5   87.85   63.47   89.97
   63.73   90.05   70.56   91.99   74.61    92.1   80.71   92.06
#Mann= 3 , 0 , 0
       0    .055       0   39.11    .035       0   45.09    .055       0
Bank Sta=39.11,45.09
XS Rating Curve= 0 ,0
Exp/Cntr=0.3,0.1

River Reach=BellsB          ,M002

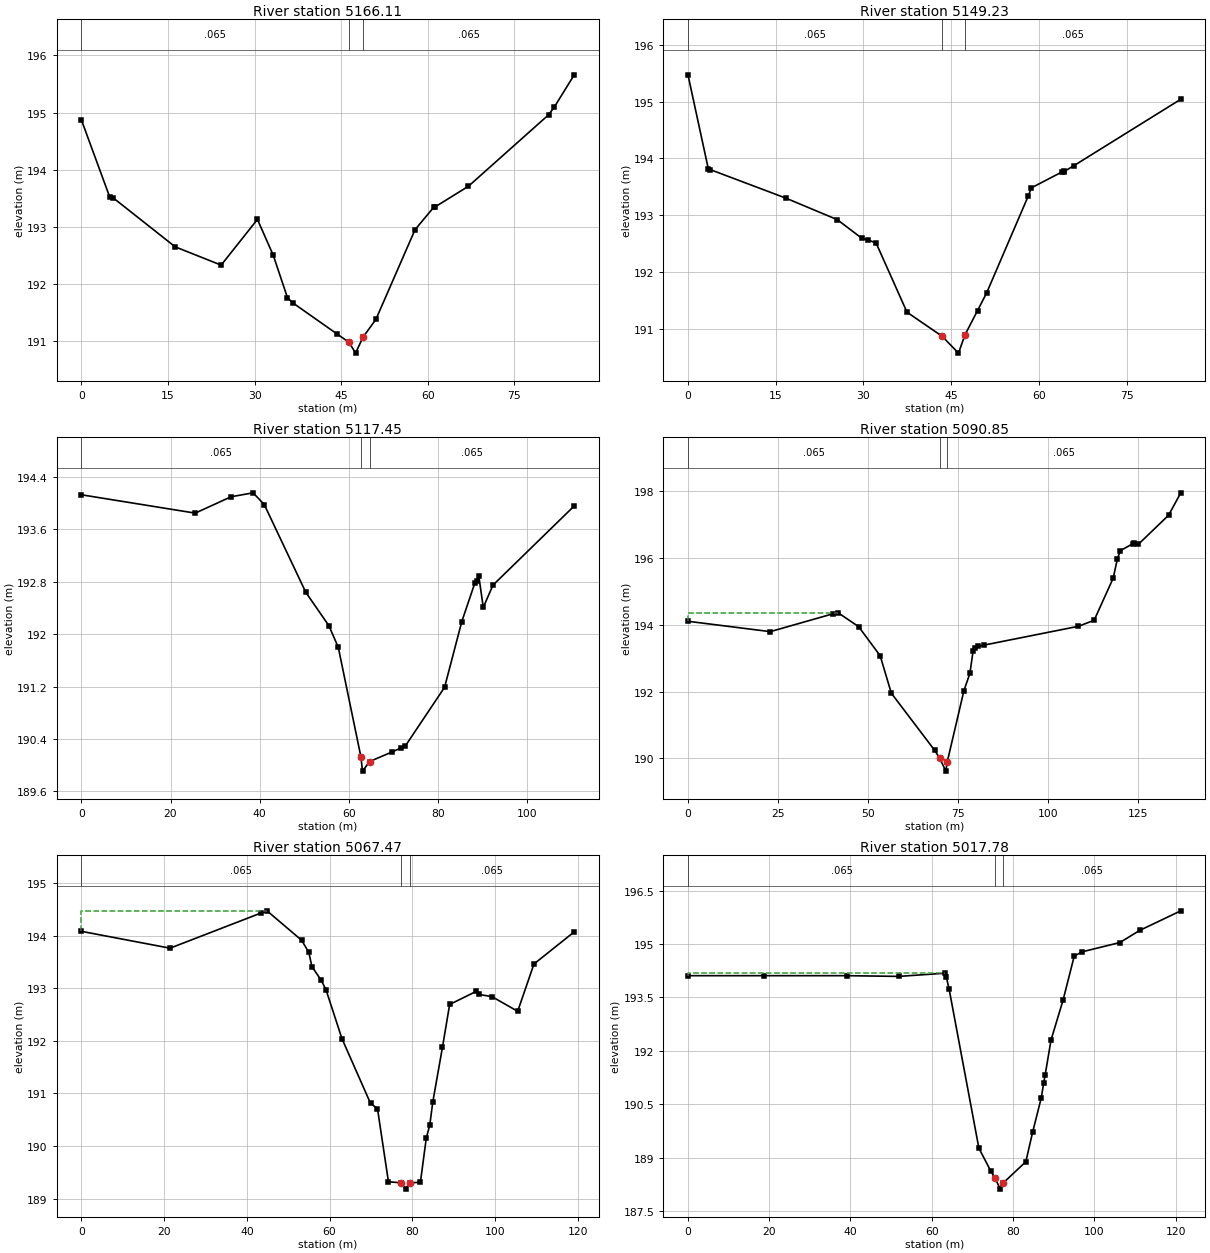
Type RM Length L Ch R = 1 ,5166.11 ,15.85,16.88,18.06
XS GIS Cut Line= 2
342277.9199218755421174.32928467342246.3927001955421094.99212646
#Sta/Elev= 21
       0  194.87    4.87  193.53    5.46  193.51   16.24  192.65    24.2  192.33
   30.49  193.13   33.24   192.5   35.69  191.76   36.61  191.67   44.35  191.12
   46.35  190.98   47.49  190.79   48.76 191.067   51.01  191.38   57.79  192.95
   61.01  193.34   61.28  193.35   67.04  193.71   80.92  194.96   81.94   195.1
   85.37  195.66
#Mann= 3 , 0 , 0
       0    .065       0   46.35     .04       0   48.76    .065       0
Bank Sta=46.35,48.76
XS Rating Curve= 0 ,0
Exp/Cntr=0.3,0.1

Type RM Length L Ch R = 1 ,5149.23 ,31.28,31.78,26.26
XS GIS Cut Line= 3
342284.6198730475421175.58990479342286.6940917975421159.00872803
 342266.990295415421094.41052246
#Sta/Elev= 21
       0  195.47    3.49  193.81    3.84   193.8   16.71   193.3   25.53  192.92
   29.75  192.59   30.83  192.56   32.16  192.51   37.45  191.29   43.45 190.867
   46.25  190.57   47.35  190.89   49.51  191.32   51.06  191.63   58.15  193.33
   58.71  193.48   63.94  193.76   64.25  193.76   64.35  193.77   65.97  193.87
   84.25  195.04
#Mann= 3 , 0 , 0
       0    .065       0   43.45     .04       0   47.35    .065       0
Bank Sta=43.45,47.35
XS Rating Curve= 0 ,0
Exp/Cntr=0.3,0.1

Type RM Length L Ch R = 1 ,5117.45 ,19.84,26.6,30.57
XS GIS Cut Line= 3
342310.9426879885421195.21392822342324.6160888675421164.53149414
342286.500915527  5421097.578125
#Sta/Elev= 22
       0  194.13   25.55  193.85   33.59   194.1   38.54  194.16   41.05  193.98
   50.37  192.64   55.56  192.13   57.66   191.8   62.74 190.128    63.1  189.91
   64.68 190.056   69.63   190.2   71.63  190.26   72.67  190.29   81.52  191.19
   85.37  192.19   88.35  192.79    88.8  192.82    89.2  192.89   90.21  192.41
   92.38  192.75  110.63  193.96
#Mann= 3 , 0 , 0
       0    .065       0   62.74     .04       0   64.68    .065       0
Bank Sta=62.74,64.68
XS Rating Curve= 0 ,0
Exp/Cntr=0.3,0.1

Type RM Length L Ch R = 1 ,5090.85 ,11.72,23.38,30.25
XS GIS Cut Line= 5
342312.2744750985421195.62567139342333.3610839845421161.42669678
342330.595703125 5421119.2824707 342333.706909185421078.17468262
342337.5092773445421065.39331055
#Sta/Elev= 27
       0   194.1   22.87  193.79   40.18  194.32   41.65  194.36   47.43  193.94
   53.42  193.07   56.52  191.95   68.58  190.24   69.99     190   71.67  189.62
   72.07   189.9   76.71  192.03   78.35  192.54   79.25  193.21   79.73  193.31
   80.68  193.35   82.41  193.39  108.53  193.95  112.89  194.13  118.19  195.39
  119.36  195.97  120.17  196.21  123.64  196.42  123.87  196.44  125.17   196.4
  133.58  197.27  136.97  197.94
#Mann= 3 , 0 , 0
       0    .065       0   69.99     .04       0   72.07    .065       0
#XS Ineff= 2 , 0
       0   41.65  194.36               0
Permanent Ineff=
       F       F
Bank Sta=69.99,72.07
XS Rating Curve= 0 ,0
Exp/Cntr=0.3,0.1

Type RM Length L Ch R = 1 ,5067.47 ,48.56,49.69,45.53
XS GIS Cut Line= 4
342313.2647094735421195.98748779342339.321716309 5421161.1796875
342343.9644775395421135.16009521342390.2396850595421118.28967285
#Sta/Elev= 28
       0  194.08   21.43  193.76   43.48  194.43   44.88  194.47   53.25  193.91
   54.99  193.68   55.73  193.41   57.98  193.15   59.14  192.97      63  192.04
   69.91  190.81   71.59  190.71   74.24  189.32   77.36   189.3   78.38  189.18
   79.36   189.3   81.97  189.31   83.39  190.15   84.24   190.4   84.95  190.83
   87.31  191.88   89.04  192.69   95.49  192.94   96.14  192.88   99.25  192.84
  105.49  192.56  109.43  193.46  119.17  194.07
#Mann= 3 , 0 , 0
       0    .065       0   77.36     .04       0   79.36    .065       0
#XS Ineff= 2 , 0
       0   44.88  194.47               0
Permanent Ineff=
       F       F
Bank Sta=77.36,79.36
XS Rating Curve= 0 ,0
Exp/Cntr=0.3,0.1

Type RM Length L Ch R = 1 ,5017.78 ,49.08,50.21,50
XS GIS Cut Line= 3
 342317.392517095421198.30810547342365.3787231455421178.71252441
342418.3422851565421133.77050781
#Sta/Elev= 24
       0  194.11   18.61  194.11   39.21  194.11   51.83  194.09   63.38  194.18
   63.57  194.08   64.28  193.73    71.6  189.27   74.56  188.62   75.65  188.42
   76.84  188.12   77.65   188.3   83.16  188.89   84.81  189.71   86.95  190.68
   87.54  191.09   87.92  191.33   89.35   192.3   92.31  193.42   95.07  194.66
   97.02  194.78   106.3  195.04  111.18  195.38  121.29  195.93
#Mann= 3 , 0 , 0
       0    .065       0   75.65     .04       0   77.65    .065       0
#XS Ineff= 2 , 0
       0   63.38  194.18               0
Permanent Ineff=
       F       F
Bank Sta=75.65,77.65
XS Rating Curve= 0 ,0
Exp/Cntr=0.3,0.1

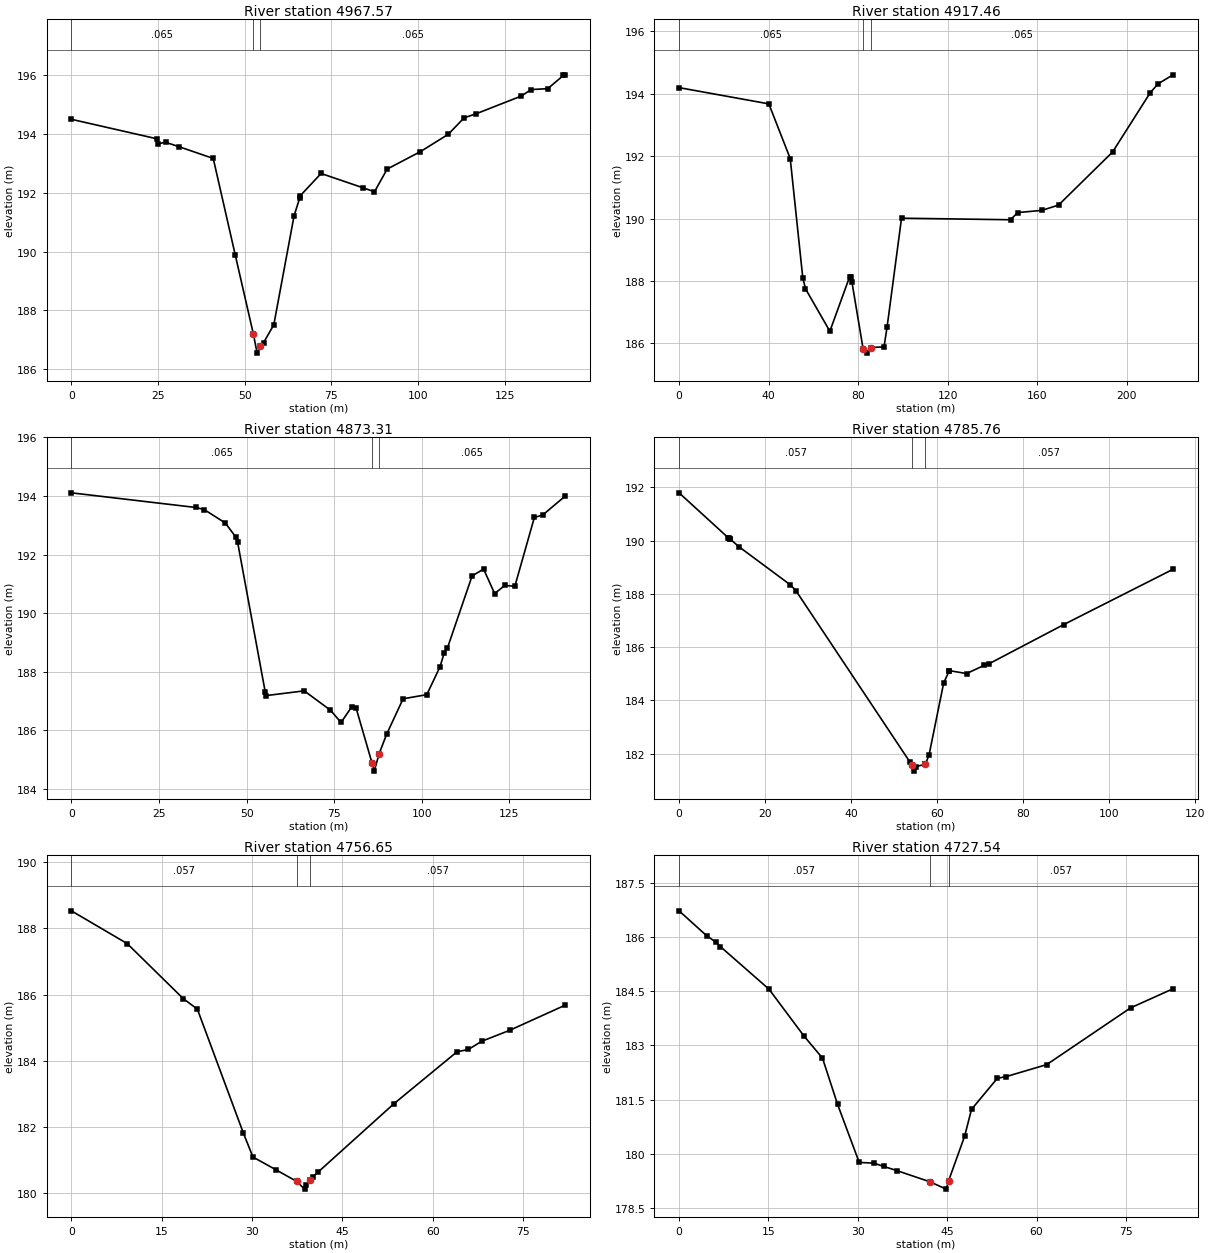
Type RM Length L Ch R = 1 ,4967.57 ,45.92,50.1,48.87
XS GIS Cut Line= 6
342356.3491210945421232.34228516342385.2438964845421220.99768066
342427.9514770515421189.73413086342426.5952758795421173.13287354
 342416.976684575421160.14831543342421.3626708985421134.88031006
#Sta/Elev= 28
       0  194.49   24.59  193.83    25.1  193.66   27.15  193.71   31.04  193.56
   40.92  193.16   47.29  189.87   52.49   187.2   53.57  186.55   54.49  186.78
   55.45  186.91   58.38  187.51   64.24  191.22   65.84  191.81   66.05   191.9
   72.02  192.65   83.97  192.17   87.42  192.03   91.08   192.8  100.63  193.39
  108.69  193.98  113.27  194.54  116.79  194.68  129.77  195.28   132.6   195.5
  137.39  195.53   141.9  195.98  142.43     196
#Mann= 3 , 0 , 0
       0    .065       0   52.49     .04       0   54.49    .065       0
Bank Sta=52.49,54.49
XS Rating Curve= 0 ,0
Exp/Cntr=0.3,0.1

Type RM Length L Ch R = 1 ,4917.46 ,19.17,44.16,54.69
XS GIS Cut Line= 6
342357.8818969735421262.62231445 342432.634704595421247.08508301
342461.317871094 5421216.9163208342469.8649291995421203.72247314
342491.2780761725421192.89349365342526.8798828135421141.00531006
#Sta/Elev= 23
       0  194.19   40.11  193.67   49.66  191.92   55.26  188.11   56.48  187.75
   67.37  186.39   76.23  188.14   76.67  188.12   77.24  187.96   82.26  185.81
   83.82  185.69   85.67  185.87   91.56  185.89   92.94  186.53   99.38  190.01
  148.09  189.96  151.23  190.19  162.06  190.26  169.52  190.43  193.67  192.13
  210.51  194.03  213.95  194.31  220.62   194.6
#Mann= 3 , 0 , 0
       0    .065       0   82.26     .04       0   85.67    .065       0
Bank Sta=82.26,85.67
XS Rating Curve= 0 ,0
Exp/Cntr=0.3,0.1

Type RM Length L Ch R = 1 ,4873.31 ,21.46,19.89,10.45
XS GIS Cut Line= 4
342358.6434936525421270.36907959342438.6124877935421267.15551758
342445.2736816415421278.15710449342491.5441284185421265.21850586
#Sta/Elev= 30
       0  194.11    35.5  193.61   37.89  193.54   43.94  193.08   46.92   192.6
   47.42  192.44   55.33  187.31   55.68  187.19   66.45  187.35   73.94  186.69
   76.96  186.27   80.03  186.81   81.22  186.78   85.82  184.88   86.44  184.61
   87.82   185.2   89.97  185.87   94.68  187.08  101.43  187.22   105.2  188.17
  106.36  188.63  107.34  188.82  114.35  191.27  117.64  191.51  120.79  190.67
   123.7  190.95  126.56  190.92  132.13  193.27  134.49  193.35  140.94     194
#Mann= 3 , 0 , 0
       0    .065       0   85.82     .04       0   87.82    .065       0
Bank Sta=85.82,87.82
XS Rating Curve= 0 ,0
Exp/Cntr=0.3,0.1

Type RM Length L Ch R = 1 ,4785.76 ,29.07,29.11,29.57
XS GIS Cut Line= 4
342381.8477172855421362.48071289342405.0465087895421351.04650879
 342451.236511235421353.20410156342487.4505004885421330.52331543
#Sta/Elev= 23
       0  191.79   11.47   190.1   11.65  190.08   11.78  190.07   11.92  190.05
   13.91  189.77   25.86  188.34   27.17  188.12    53.6  181.71    54.2 181.581
   54.58  181.35    55.1  181.52    57.1   181.6   57.25   181.6   58.13  181.96
   61.53  184.66   62.79   185.1   62.85  185.12   66.84  185.01   70.98  185.32
    72.1  185.38   89.47  186.85  114.83  188.92
#Mann= 3 , 0 , 0
       0    .057       0    54.2     .04       0    57.1    .057       0
Bank Sta=54.2,57.1
XS Rating Curve= 0 ,0
Exp/Cntr=0.3,0.1

Type RM Length L Ch R = 1 ,4756.65 ,30.95,29.11,26.42
XS GIS Cut Line= 3
342393.0432739265421378.32452393342446.4367065435421382.54150391
342470.5885009775421367.50811768
#Sta/Elev= 19
       0  188.53    9.27  187.54   18.62  185.87   20.92  185.56   28.55  181.82
   30.15  181.09   33.92  180.71   37.43 180.352   38.72  180.12      39  180.25
   39.68   180.4   40.13   180.5      41  180.64   53.56   182.7   64.04  184.27
   65.91  184.34   68.17  184.59    72.8  184.92   82.01  185.68
#Mann= 3 , 0 , 0
       0    .057       0   37.43     .04       0   39.68    .057       0
Bank Sta=37.43,39.68
XS Rating Curve= 0 ,0
Exp/Cntr=0.3,0.1

Type RM Length L Ch R = 1 ,4727.54 ,19.26,20,19.72
XS GIS Cut Line= 4
342396.6063232425421408.54730225342417.0162963875421413.36407471
342443.3679199225421407.66790771342470.1505126955421385.22271729
#Sta/Elev= 22
       0  186.73    4.63  186.04    6.12  185.87    6.93  185.74   15.09  184.56
   20.97  183.26   24.07  182.65    26.6  181.37   30.23  179.76   32.67  179.74
   34.33  179.65   36.61  179.53   42.07 179.225   44.84  179.02   45.24 179.254
   47.93  180.49   49.08  181.23   53.41  182.09   54.95  182.14    61.7  182.47
   75.76  184.04   82.88  184.57
#Mann= 3 , 0 , 0
       0    .057       0   42.07    .037       0   45.24    .057       0
Bank Sta=42.07,45.24
XS Rating Curve= 0 ,0
Exp/Cntr=0.3,0.1

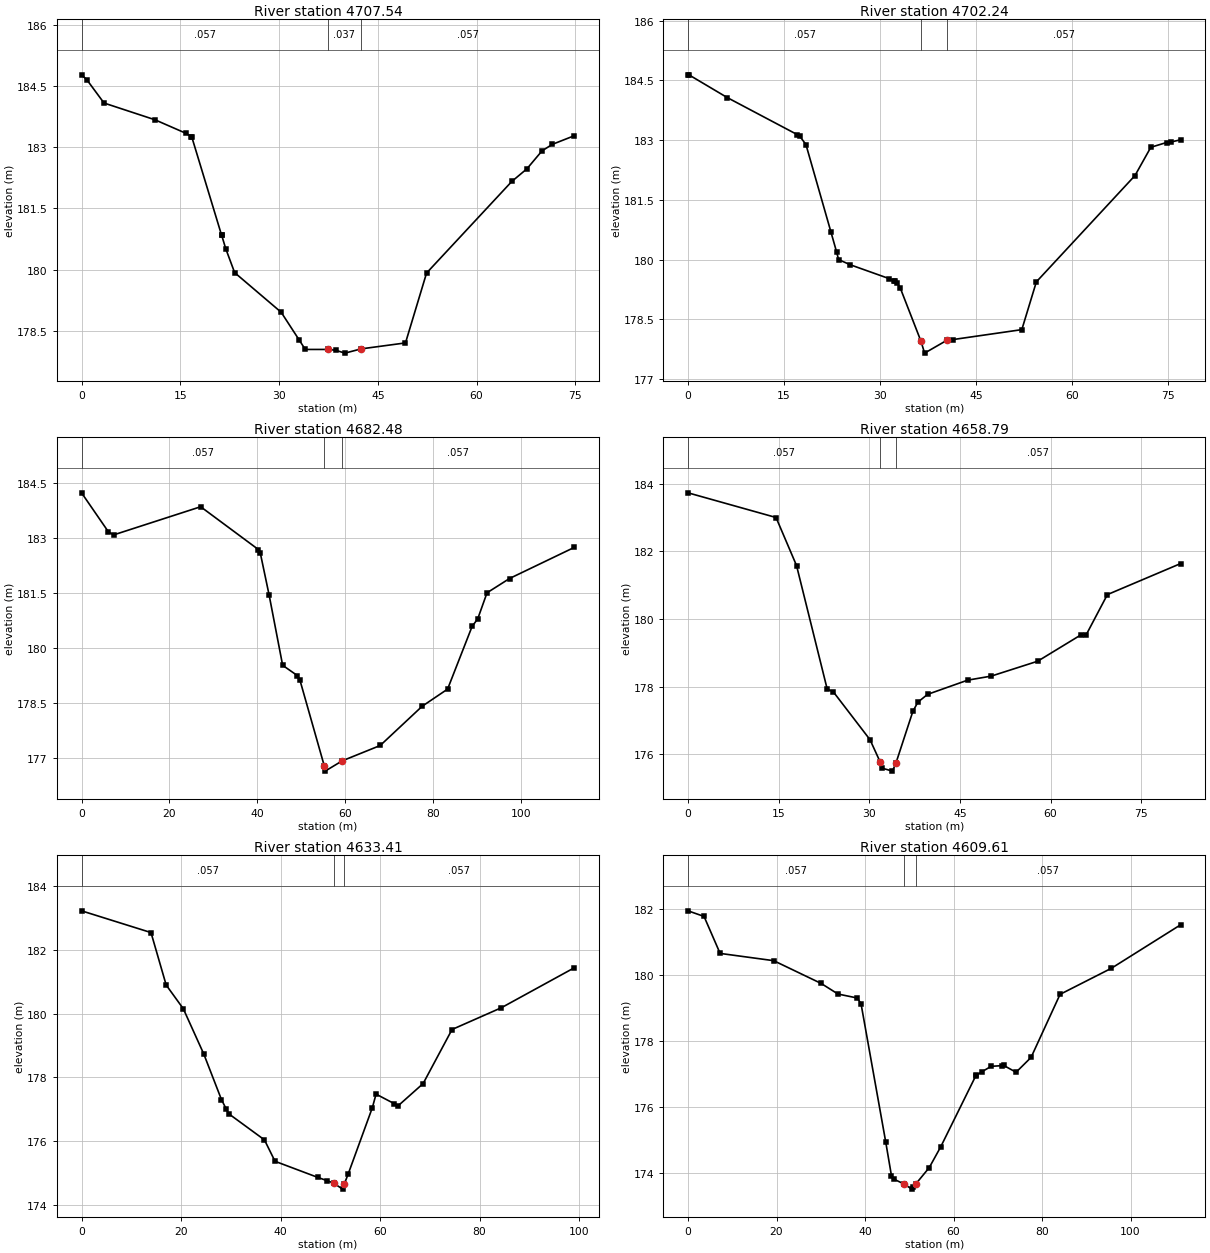
Type RM Length L Ch R = 1 ,4707.54 ,5.01,5.31,4.99
XS GIS Cut Line= 3
342405.9539184575421428.78527832342427.0795288095421431.20550537
342478.2404785165421415.30487061
#Sta/Elev= 25
       0  184.77      .8  184.65    3.41  184.08   11.15  183.67   15.84  183.34
   16.68  183.26   16.74  183.25   21.26  180.85   21.27  180.85   21.89  180.52
   23.25  179.93   30.32  178.96   33.06  178.28   33.98  178.05   37.37  178.05
    38.6  178.03      40  177.96   42.46 178.064    49.2  178.21    52.4  179.92
   65.34  182.16   67.64  182.47   69.94  182.91   71.52  183.07   74.84  183.28
#Mann= 3 , 0 , 0
       0    .057       0   37.37    .037       0   42.46    .057       0
Bank Sta=37.37,42.46
XS Rating Curve= 0 ,0
Exp/Cntr=0.3,0.1

Type RM Length L Ch R = 1 ,4702.24 ,16.74,19.76,23.42
XS GIS Cut Line= 3
342405.385681152 5421433.7454834342427.5565185555421436.28552246
342479.7224731455421420.07269287
#Sta/Elev= 26
       0  184.64     .14  184.64    6.11  184.07   17.04  183.14   17.44   183.1
   18.41  182.89   22.32  180.69    23.2  180.19   23.51     180   25.32  179.87
   31.43  179.52   32.12  179.47   32.25  179.47   32.66  179.41   33.13  179.29
   36.37  177.95   36.94  177.65   40.39  177.97   41.34  177.99   52.12  178.24
   54.39  179.44   69.79  182.11   72.26  182.82   74.72  182.94   75.35  182.95
   76.94  183.01
#Mann= 3 , 0 , 0
       0    .057       0   36.37    .037       0   40.39    .057       0
Bank Sta=36.37,40.39
XS Rating Curve= 0 ,0
Exp/Cntr=0.3,0.1

Type RM Length L Ch R = 1 ,4682.48 ,24.78,23.69,17.54
XS GIS Cut Line= 3
342384.6652832035421449.13708496342462.1015014655421451.67608643
342490.3955078135421431.71368408
#Sta/Elev= 21
       0  184.23    6.08  183.17    7.27  183.08    27.1  183.85   40.25  182.68
   40.66  182.59   42.69  181.43   45.75  179.52   49.09  179.24   49.65  179.13
   55.24 176.766   55.42  176.63   59.29  176.91   67.95  177.33   77.48   178.4
   83.28  178.87   88.85  180.58   90.14  180.79   92.25   181.5   97.37  181.89
  112.11  182.74
#Mann= 3 , 0 , 0
       0    .057       0   55.24    .037       0   59.29    .057       0
Bank Sta=55.24,59.29
XS Rating Curve= 0 ,0
Exp/Cntr=0.3,0.1

Type RM Length L Ch R = 1 ,4658.79 ,20.47,25.37,24.27
XS GIS Cut Line= 4
342413.6375122075421476.55328369342443.7119140635421474.82592773
 342454.427917485421468.95349121342486.5764770515421446.49951172
#Sta/Elev= 20
       0  183.73   14.57     183   17.96  181.58   23.03  177.93   24.07  177.84
   30.12  176.43   31.78  175.78   32.09  175.59   33.83   175.5    34.4  175.73
   37.22  177.27   38.05  177.54   39.65  177.77   46.28  178.19   50.19  178.31
   57.87  178.75   65.04  179.53    65.9  179.53   69.41  180.72   81.56  181.64
#Mann= 3 , 0 , 0
       0    .057       0   31.78    .037       0    34.4    .057       0
Bank Sta=31.78,34.4
XS Rating Curve= 0 ,0
Exp/Cntr=0.3,0.1

Type RM Length L Ch R = 1 ,4633.41 ,27.81,23.8,18.32
XS GIS Cut Line= 4
342416.7960815435421491.53570557342437.1434936525421493.58789063
342478.5769042975421484.43591309342504.669311523 5421459.3939209
#Sta/Elev= 24
       0  183.21   13.96  182.53   17.01  180.89   20.45  180.15   24.58  178.73
   28.12  177.31   29.03  177.03   29.55  176.87   36.76  176.05   38.89  175.38
   47.43  174.88   49.43  174.77   50.68 174.697   52.47  174.51   52.79  174.66
   53.59  174.98   58.46  177.06    59.2  177.48   62.88  177.18   63.67  177.12
   68.66  177.81   74.47   179.5   84.38  180.18   99.05  181.43
#Mann= 3 , 0 , 0
       0    .057       0   50.68    .037       0   52.79    .057       0
Bank Sta=50.68,52.79
XS Rating Curve= 0 ,0
Exp/Cntr=0.3,0.1

Type RM Length L Ch R = 1 ,4609.61 ,24.92,25.62,25.97
XS GIS Cut Line= 5
342429.1931152345421518.69750977342463.0698852545421519.04290771
342476.8972778325421500.38891602342476.5516967775421488.98931885
342508.7000732425421460.66271973
#Sta/Elev= 28
       0  181.93    3.62  181.76    7.25  180.64   19.36  180.42   30.09  179.73
   33.88  179.41   38.21  179.29   39.09  179.12   44.66  174.94   45.98   173.9
   46.55   173.8   48.75  173.66   50.58   173.5   50.82  173.55   51.53 173.666
    54.5  174.15    57.1  174.78   64.98  176.92   65.12  176.95   66.47  177.06
    68.5  177.22   70.92  177.24    71.3  177.25   74.13  177.04   77.52  177.49
   84.07   179.4   95.67  180.19  111.35  181.51
#Mann= 3 , 0 , 0
       0    .057       0   48.75    .037       0   51.53    .057       0
Bank Sta=48.75,51.53
XS Rating Curve= 0 ,0
Exp/Cntr=0.3,0.1

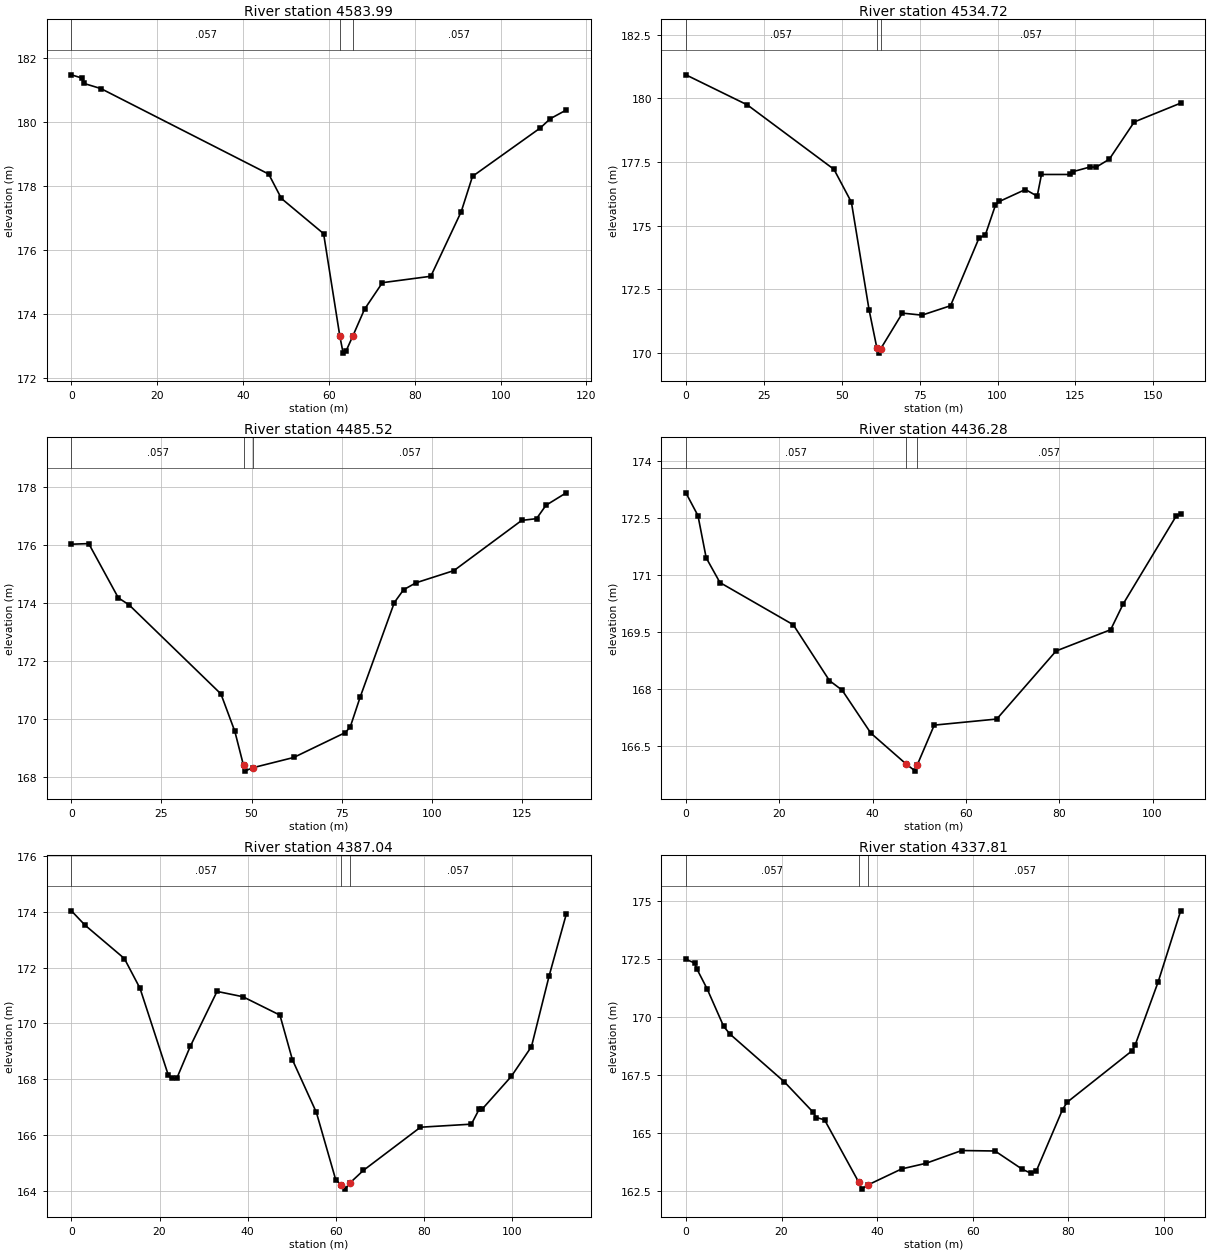
Type RM Length L Ch R = 1 ,4583.99 ,44.18,49.27,61.24
XS GIS Cut Line= 3
342431.0048828135421538.47949219342482.4049072275421532.46948242
342524.3275146485421484.73327637
#Sta/Elev= 19
       0  181.46    2.43  181.36    2.96  181.19    6.88  181.03   45.97  178.36
   48.92   177.6   58.76   176.5   62.54   173.3   63.31  172.77      64  172.84
   65.52  173.29   68.29  174.14   72.46  174.97   83.74  175.17   90.83  177.19
   93.45  178.29  109.24   179.8  111.57  180.09  115.28  180.36
#Mann= 3 , 0 , 0
       0    .057       0   62.54    .037       0   65.52    .057       0
Bank Sta=62.54,65.52
XS Rating Curve= 0 ,0
Exp/Cntr=0.3,0.1

Type RM Length L Ch R = 1 ,4534.72 ,52.34,49.2,34.25
XS GIS Cut Line= 6
342436.604125977 5421544.3560791  342456.17968755421542.00231934
342507.2526855475421565.09869385342533.8956909185421539.60070801
342533.8956909185421523.66491699342551.0834960945421500.07147217
#Sta/Elev= 25
       0  180.92   19.72  179.74   47.53  177.21   53.12  175.92   58.77  171.71
   61.31  170.19   61.87     170   62.56  170.18   69.48  171.57   75.77  171.49
   84.93  171.86   94.04  174.51    96.1  174.64   99.35  175.81  100.58  175.95
  108.94  176.42  112.74  176.16  114.11  177.01  123.21  177.01  124.19  177.12
  129.59   177.3   131.7   177.3  135.88  177.61  143.88  179.07  158.78  179.81
#Mann= 3 , 0 , 0
       0    .057       0   61.31    .037       0   62.56    .057       0
Bank Sta=61.31,62.56
XS Rating Curve= 0 ,0
Exp/Cntr=0.3,0.1

Type RM Length L Ch R = 1 ,4485.52 ,46.5,49.24,52.08
XS GIS Cut Line= 4
342476.4520874025421609.90167236342512.644287109 5421605.4152832
342558.8079223635421563.58587646 342569.720886235421526.56231689
#Sta/Elev= 21
       0  176.02    4.81  176.04   13.03  174.17      16  173.93   41.51  170.86
   45.37  169.57   47.78 168.396   48.08   168.2   50.46  168.32    61.7  168.67
   76.06  169.53   77.43  169.73   80.16  170.75   89.65  174.01   92.21  174.45
   95.66  174.69  106.19  175.11  125.01  176.84  129.12   176.9  131.74  177.36
  137.36  177.79
#Mann= 3 , 0 , 0
       0    .057       0   47.78    .037       0   50.46    .057       0
Bank Sta=47.78,50.46
XS Rating Curve= 0 ,0
Exp/Cntr=0.3,0.1

Type RM Length L Ch R = 1 ,4436.28 ,49.6,49.24,49.91
XS GIS Cut Line= 2
342514.9763183595421651.73468018342609.2982788095421603.30792236
#Sta/Elev= 18
       0  173.17    2.59  172.57    4.35  171.46     7.3  170.81   23.01   169.7
   30.77  168.23   33.48  167.98   39.63  166.85   47.26  166.03   49.18  165.85
   49.54 166.001   53.22  167.06   66.62  167.22   79.33  169.01   91.03  169.57
   93.72  170.25  105.12  172.57  106.03  172.61
#Mann= 3 , 0 , 0
       0    .057       0   47.26    .037       0   49.54    .057       0
Bank Sta=47.26,49.54
XS Rating Curve= 0 ,0
Exp/Cntr=0.3,0.1

Type RM Length L Ch R = 1 ,4387.04 ,46.3,49.24,50.07
XS GIS Cut Line= 5
342529.6284790045421685.46728516342563.0474853525421672.84527588
342570.367919922 5421677.3192749342608.3071289065421658.34008789
342632.8118896485421651.14147949
#Sta/Elev= 26
       0  174.04    3.06  173.53   12.01  172.33   15.57  171.26      22  168.14
   22.75  168.03    23.9  168.03   26.97  169.18   33.04  171.15    38.9  170.96
   47.31   170.3   50.14   168.7   55.58  166.81   59.96   164.4   61.19  164.21
   62.09  164.06   63.19  164.28   66.23  164.73    79.2  166.28   90.75  166.39
   92.49  166.92    93.2  166.93   99.79   168.1  104.38  169.17  108.41  171.72
  112.26  173.91
#Mann= 3 , 0 , 0
       0    .057       0   61.19    .037       0   63.19    .057       0
Bank Sta=61.19,63.19
XS Rating Curve= 0 ,0
Exp/Cntr=0.3,0.1

Type RM Length L Ch R = 1 ,4337.81 ,50.62,49.24,33.92
XS GIS Cut Line= 3
342552.150695801 5421724.3861084342620.3140869145421706.85028076
342649.2227172855421690.75970459
#Sta/Elev= 26
       0  172.48    1.81  172.33     2.3  172.07    4.45  171.21     7.9   169.6
    9.21  169.27   20.56  167.22   26.56  165.92   27.28  165.68      29  165.58
   36.17  162.89   36.78   162.6   38.17  162.79   45.13  163.47   50.19  163.71
   57.67  164.26   64.65  164.24   70.38  163.45   72.09  163.29   73.24  163.36
   78.76  166.02   79.74  166.34   93.36  168.56   93.97  168.81   98.79  171.53
  103.47  174.57
#Mann= 3 , 0 , 0
       0    .057       0   36.17    .037       0   38.17    .057       0
Bank Sta=36.17,38.17
XS Rating Curve= 0 ,0
Exp/Cntr=0.3,0.1

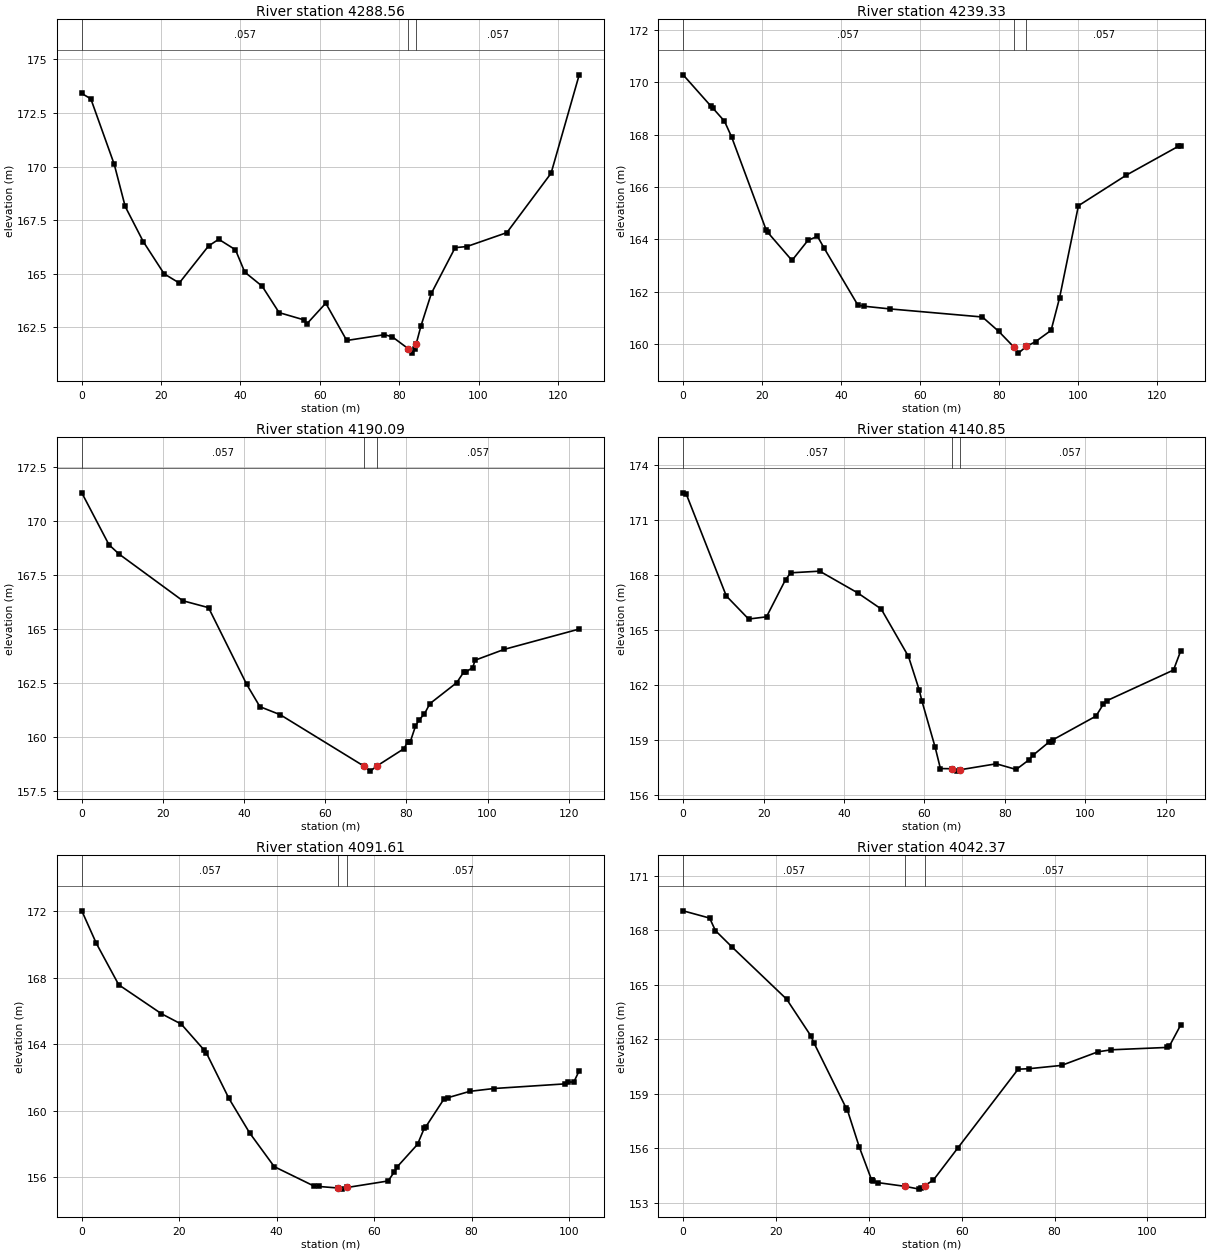
Type RM Length L Ch R = 1 ,4288.56 ,36.74,49.24,50.5
XS GIS Cut Line= 4
342557.9196777345421764.43530273342612.8831176765421757.08770752
342642.3812866215421719.70507813342659.7506713875421705.71130371
#Sta/Elev= 30
       0  173.41    2.28  173.16    8.19   170.1   10.94  168.14    15.5   166.5
   20.75     165   24.57  164.57   31.96   166.3   34.52  166.61   38.74  166.12
   41.07  165.08   45.47  164.42   49.73  163.19   56.02  162.85   56.71  162.66
    61.5  163.63   66.78  161.89   76.29  162.16   78.27  162.06   82.26  161.51
   83.35   161.3   83.93  161.48   84.26  161.71   85.48  162.56   88.12  164.09
   94.11  166.22   97.04  166.27  107.14  166.92  118.29  169.69  125.38  174.28
#Mann= 3 , 0 , 0
       0    .057       0   82.26    .037       0   84.26    .057       0
Bank Sta=82.26,84.26
XS Rating Curve= 0 ,0
Exp/Cntr=0.3,0.1

Type RM Length L Ch R = 1 ,4239.33 ,35.63,49.24,52.62
XS GIS Cut Line= 3
 342563.541076665421793.56671143342609.3999023445421791.84429932
342685.8198852545421768.18011475
#Sta/Elev= 27
       0  170.28    7.06  169.08    7.45  169.02   10.46  168.51   12.29   167.9
      21  164.36   21.37  164.27   27.55  163.19    31.6  163.96      34  164.11
   35.73  163.65   44.24  161.48   45.89  161.44   52.26  161.34   75.74  161.03
   79.88  160.48   83.64 159.892   84.87  159.65   86.89  159.91   86.94  159.91
    89.2  160.09   93.13  160.52   95.27  161.76  100.04  165.28  112.19  166.45
  125.33  167.55  125.89  167.58
#Mann= 3 , 0 , 0
       0    .057       0   83.64    .037       0   86.89    .057       0
Bank Sta=83.64,86.89
XS Rating Curve= 0 ,0
Exp/Cntr=0.3,0.1

Type RM Length L Ch R = 1 ,4190.09 ,49.91,49.24,55.65
XS GIS Cut Line= 4
342564.906494141 5421832.1138916342612.0805053715421819.24353027
342657.2094726565421834.66107178342680.4273071295421822.94030762
#Sta/Elev= 25
       0   171.3     6.7   168.9    9.17  168.47   24.89  166.31   31.24  165.99
   40.65  162.44    43.9  161.41    48.9  161.04   69.55  158.66   71.11  158.43
   72.75  158.67   79.42  159.47   80.37   159.8   80.91  159.76   82.23   160.5
   83.06  160.78   84.46  161.08    85.8  161.55   92.41  162.52   94.21  163.03
   94.72  163.02   96.35  163.22   96.94  163.56  104.11  164.06   122.6     165
#Mann= 3 , 0 , 0
       0    .057       0   69.55    .037       0   72.75    .057       0
Bank Sta=69.55,72.75
XS Rating Curve= 0 ,0
Exp/Cntr=0.3,0.1

Type RM Length L Ch R = 1 ,4140.85 ,50.08,49.24,44.09
XS GIS Cut Line= 4
342563.7938842775421854.57348633342597.0925292975421854.53430176
342637.4605102545421883.19732666342676.4578857425421895.42871094
#Sta/Elev= 30
       0  172.47     .75  172.42   10.73  166.85   16.28  165.59   20.73  165.71
   25.47  167.74   26.77  168.11   33.95   168.2   43.37  167.02   49.24  166.14
   56.03  163.55   58.71  161.72   59.35  161.14   62.68  158.59   63.97  157.44
   66.75  157.43   68.11   157.3   68.75  157.37   77.87   157.7   82.81  157.39
   85.91   157.9   87.02  158.17   90.89  158.87   91.77  158.89   92.05  159.02
  102.66   160.3  104.51  160.96  105.37  161.14  121.93  162.81  123.68  163.83
#Mann= 3 , 0 , 0
       0    .057       0   66.75    .037       0   68.75    .057       0
Bank Sta=66.75,68.75
XS Rating Curve= 0 ,0
Exp/Cntr=0.3,0.1

Type RM Length L Ch R = 1 ,4091.61 ,53.58,49.24,44.06
XS GIS Cut Line= 4
342559.2192993165421904.87329102342620.5538940435421923.62390137
342636.3096923835421936.57489014342653.1049194345421941.70928955
#Sta/Elev= 29
       0  172.01    2.98  170.06    7.58  167.57   16.36  165.83   20.41  165.21
   25.02  163.68   25.53   163.5   30.19  160.75   34.46  158.67    39.5  156.65
   47.62  155.49   48.62  155.46    52.5  155.37   53.43   155.3    54.5   155.4
   62.87  155.79   64.14  156.33   64.74  156.64   68.91  157.99   70.32  158.98
    70.6  159.04   74.29  160.69   75.26   160.8   79.61  161.17   84.53  161.34
    99.2  161.62    99.8  161.73  100.99  161.73  102.09  162.41
#Mann= 3 , 0 , 0
       0    .057       0    52.5    .037       0    54.5    .057       0
Bank Sta=52.5,54.5
XS Rating Curve= 0 ,0
Exp/Cntr=0.3,0.1

Type RM Length L Ch R = 1 ,4042.37 ,41.02,49.24,52.89
XS GIS Cut Line= 4
342551.3035278325421966.67669678342589.190124512 5421968.8046875
342634.6436767585421944.78930664342652.2474975595421947.19470215
#Sta/Elev= 28
       0  169.08    5.71  168.68    6.95  167.99   10.47   167.1   22.29  164.21
   27.55  162.17   28.19  161.79   35.12   158.2   35.35  158.12   37.95  156.05
   40.57  154.26   40.58  154.25   40.87  154.21   41.92   154.1   47.85  153.89
   50.85  153.74   51.24   153.8   52.05 153.935   53.89  154.24   59.22  156.03
   72.14  160.35   74.58  160.38    81.5  160.56   89.35  161.31    92.2  161.42
  104.19  161.55  104.71  161.62  107.12  162.77
#Mann= 3 , 0 , 0
       0    .057       0   47.85    .037       0   52.05    .057       0
Bank Sta=47.85,52.05
XS Rating Curve= 0 ,0
Exp/Cntr=0.3,0.1

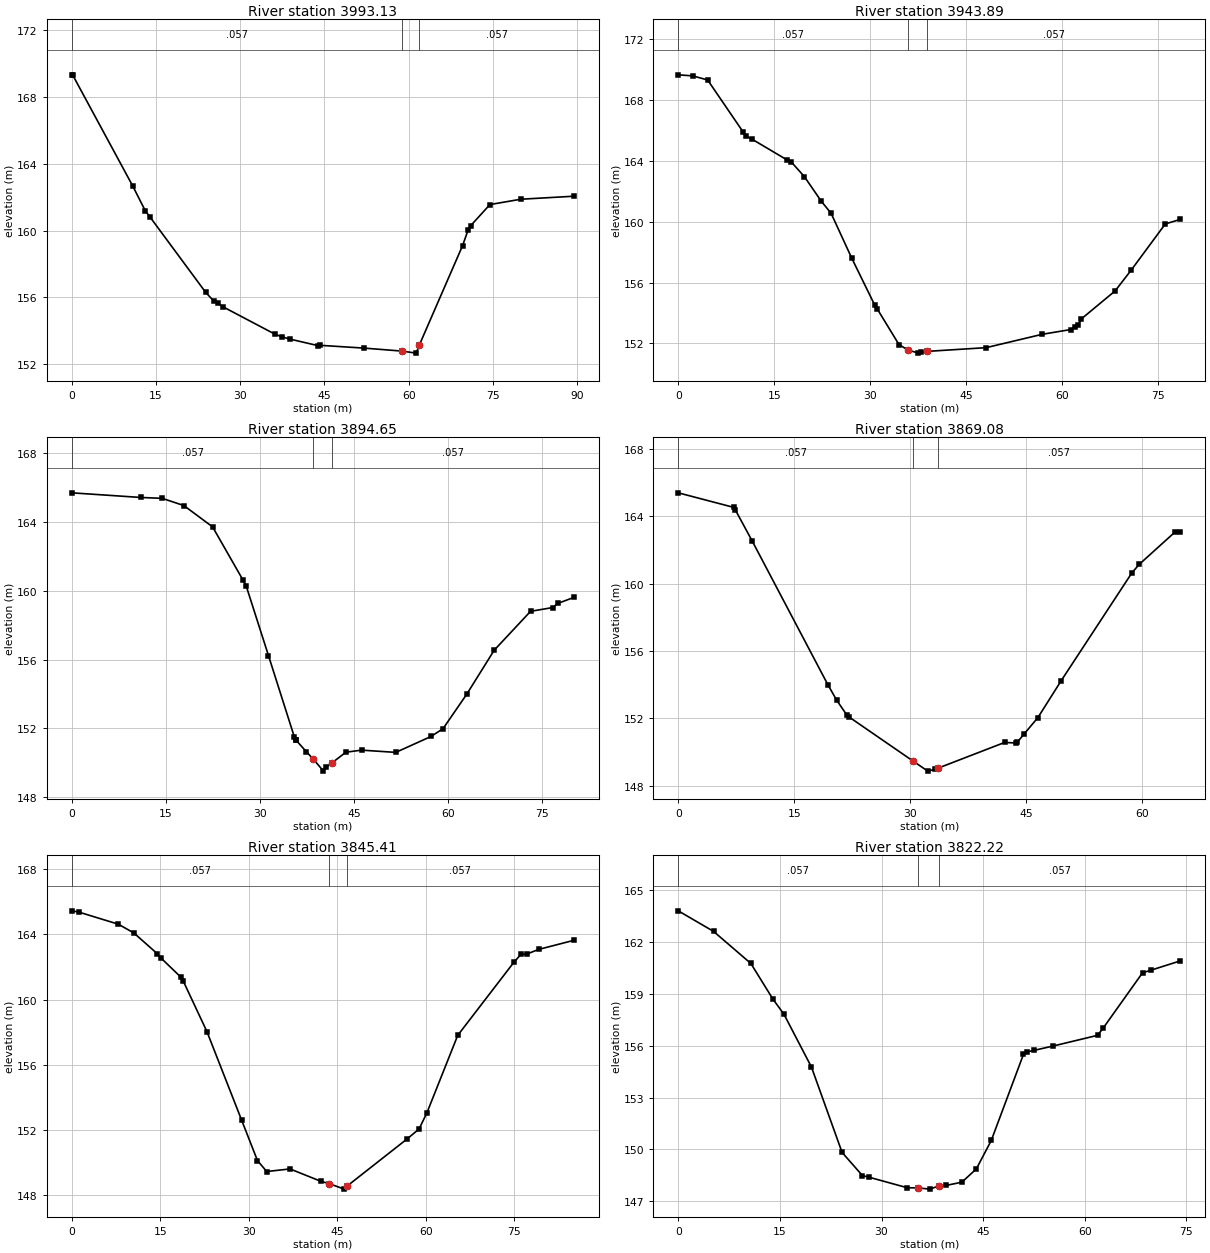
Type RM Length L Ch R = 1 ,3993.13 ,39.57,49.24,44.53
XS GIS Cut Line= 2
342549.3613281255421993.30548096342634.8760986335422019.35968018
#Sta/Elev= 24
       0  169.34     .21   169.3   10.86  162.67    13.1  161.18   13.96   160.8
   23.83   156.3   25.24  155.79   25.98  155.64   26.97  155.42   36.27  153.77
   37.41  153.63   38.86  153.49   43.84   153.1   44.13  153.12    52.1  152.95
   58.87  152.77   61.33  152.65   61.87  153.12   69.59   159.1   70.57  160.03
   71.05   160.3   74.46  161.56   79.99  161.88    89.4  162.06
#Mann= 3 , 0 , 0
       0    .057       0   58.87    .037       0   61.87    .057       0
Bank Sta=58.87,61.87
XS Rating Curve= 0 ,0
Exp/Cntr=0.3,0.1

Type RM Length L Ch R = 1 ,3943.89 ,52.3,49.24,36.01
XS GIS Cut Line= 4
342533.9439086915422029.79992676342556.2128906255422032.16729736
342579.2341308595422043.68389893342608.8457031255422036.94390869
#Sta/Elev= 30
       0  169.65    2.28  169.58     4.6  169.31   10.12  165.91   10.59  165.62
    11.5  165.43   16.96  164.07   17.68  163.92   19.72  162.96   22.39  161.33
    23.9  160.55   27.13   157.6   30.74   154.5   31.09  154.28   34.52  151.92
    35.9  151.57   37.55  151.36   37.94  151.42    38.9  151.47   39.11  151.48
   48.14  151.72   56.94   152.6   61.37  152.91   62.01  153.07   62.57  153.22
   63.03  153.61   68.31  155.45   70.83  156.82   76.15  159.85    78.5  160.15
#Mann= 3 , 0 , 0
       0    .057       0    35.9    .037       0    38.9    .057       0
Bank Sta=35.9,38.9
XS Rating Curve= 0 ,0
Exp/Cntr=0.3,0.1

Type RM Length L Ch R = 1 ,3894.65 ,23.67,25.58,25.02
XS GIS Cut Line= 2
342564.8654785165422099.50732422342629.7084960945422052.65228271
#Sta/Elev= 27
       0   165.7   11.01  165.43   14.41  165.38   17.86  164.96   22.44  163.72
   27.28  160.63   27.77  160.31   31.34  156.24   35.47   151.5   35.72  151.33
   35.76  151.31   37.35  150.66    38.5  150.21   40.11  149.52   40.52  149.74
    41.5  150.01   43.68  150.62   46.17  150.74   51.63  150.61   57.27  151.54
   59.16  151.99   62.95     154   67.31  156.55    73.1  158.81   76.62  159.03
   77.45  159.27      80  159.62
#Mann= 3 , 0 , 0
       0    .057       0    38.5    .037       0    41.5    .057       0
Bank Sta=38.5,41.5
XS Rating Curve= 0 ,0
Exp/Cntr=0.3,0.1

Type RM Length L Ch R = 1 ,3869.08 ,21.81,23.66,24.62
XS GIS Cut Line= 2
342589.9974975595422104.68969727 342647.380676275422074.29052734
#Sta/Elev= 22
       0  165.38    7.23  164.51    7.37  164.38    9.58  162.51   19.35     154
   20.49  153.08   21.79  152.21    22.1  152.08   30.33  149.48   32.28  148.87
   33.22  148.98   33.57  149.04   42.21  150.57    43.7  150.54   43.83  150.57
   44.73  151.07   46.51  152.04   49.54  154.24   58.66  160.62   59.61  161.13
   64.22  163.04   64.94  163.06
#Mann= 3 , 0 , 0
       0    .057       0   30.33    .037       0   33.57    .057       0
Bank Sta=30.33,33.57
XS Rating Curve= 0 ,0
Exp/Cntr=0.3,0.1

Type RM Length L Ch R = 1 ,3845.41 ,15.32,23.19,28.59
XS GIS Cut Line= 3
342586.6223144535422113.60931396342615.4235229495422113.07470703
342669.9196777345422098.91967773
#Sta/Elev= 26
       0  165.45    1.22  165.37    7.89  164.63   10.53  164.09   14.46  162.83
   15.19  162.53   18.52  161.37   18.91  161.13   22.91  158.04   28.81  152.59
   31.48  150.12   33.05  149.45   36.99  149.61   42.23  148.85   43.61  148.71
    46.2  148.37   46.61  148.54   56.88  151.46   58.87  152.06   60.21  153.06
   65.43  157.81   74.94  162.29   76.15  162.78   77.09  162.79   79.13  163.08
   85.11  163.64
#Mann= 3 , 0 , 0
       0    .057       0   43.61     .04       0   46.61    .057       0
Bank Sta=43.61,46.61
XS Rating Curve= 0 ,0
Exp/Cntr=0.3,0.1

Type RM Length L Ch R = 1 ,3822.22 ,25.21,26.04,26.17
XS GIS Cut Line= 4
342593.7999267585422120.92547607342621.454528809 5422126.1072998
342641.5040893555422139.92492676342662.9362792975422142.68847656
#Sta/Elev= 26
       0  163.78    5.22  162.59   10.72  160.74   13.96  158.69    15.6  157.81
   19.66  154.76   24.18  149.83   27.19  148.49   28.14   148.4    33.8  147.79
   35.43  147.78   37.13  147.71   38.44  147.89   39.48  147.92   41.86  148.11
      44  148.88    46.2  150.52   50.95  155.49   51.43  155.63   52.49  155.72
   55.29  155.97   61.88  156.59   62.72  157.01   68.52   160.2   69.75  160.35
    74.1  160.89
#Mann= 3 , 0 , 0
       0    .057       0   35.43     .04       0   38.44    .057       0
Bank Sta=35.43,38.44
XS Rating Curve= 0 ,0
Exp/Cntr=0.3,0.1