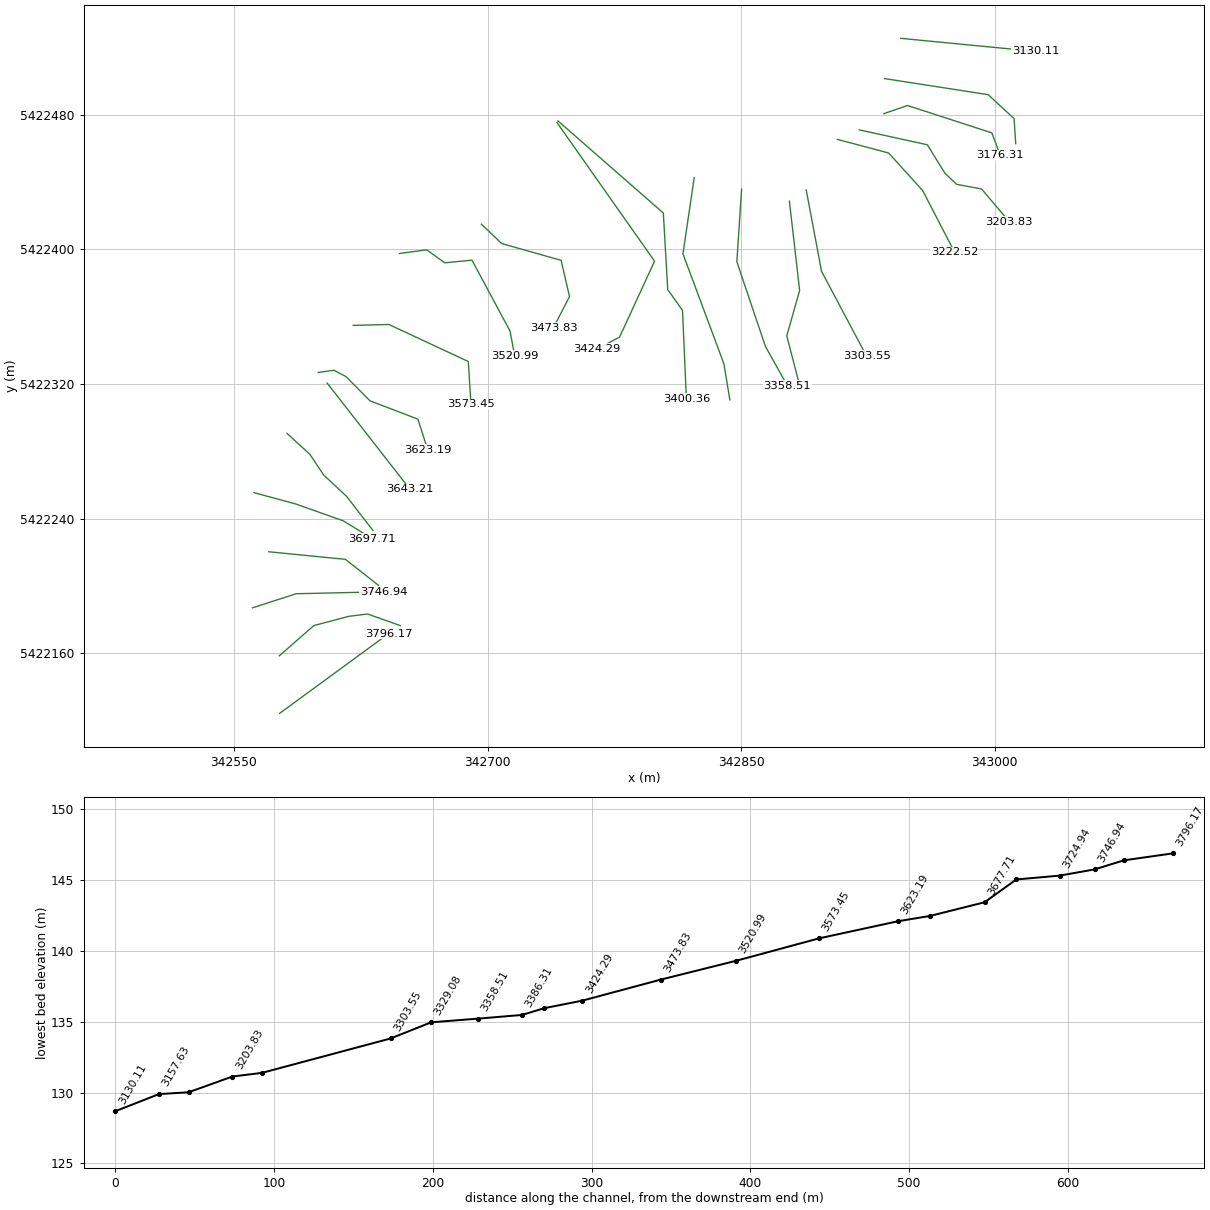
HEC-RAS study Corner_Brook2.prj: Corner_Brook2

--- Corner_Brook2.g02 (geometry) --- (continued)

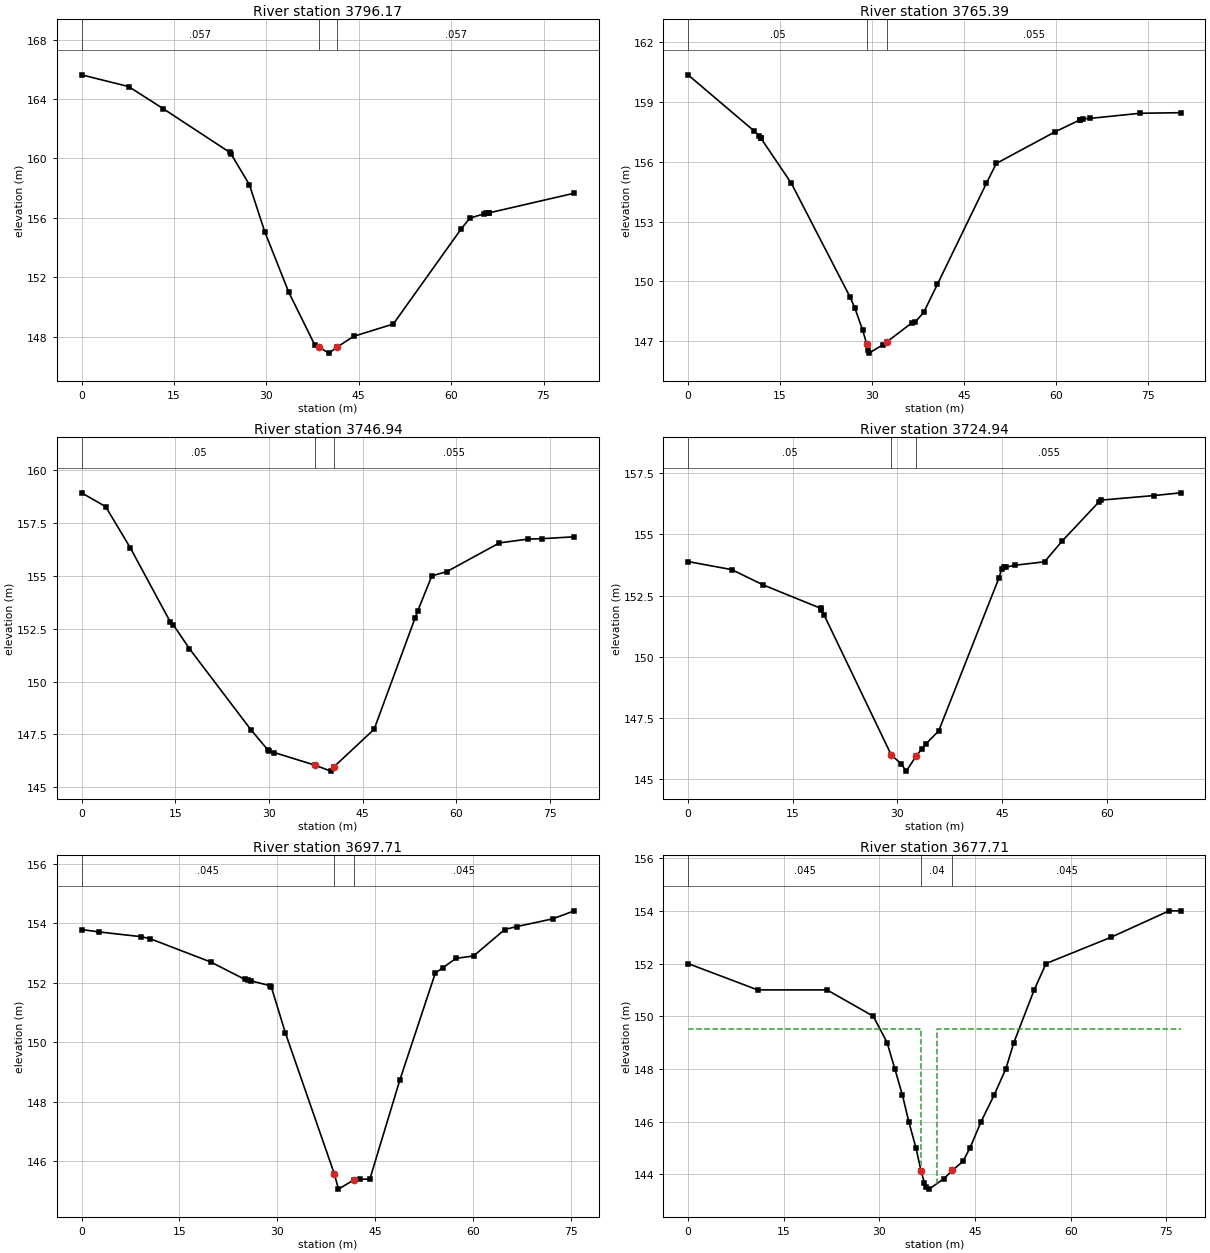
Type RM Length L Ch R = 1 ,3796.17 ,31.62,30.78,27.51
XS GIS Cut Line= 2
342577.0494995125422124.41027832342641.5092773445422171.79107666
#Sta/Elev= 21
       0  165.63    7.64  164.84   13.22  163.36   24.02  160.42   24.32  160.27
   27.25  158.23   29.74  155.07   33.64  150.99   37.85  147.45    38.5   147.3
   40.16  146.89    41.5   147.3   44.17  148.02   50.61  148.85   61.61  155.24
   63.03  155.98   65.27  156.26   65.61   156.3   66.11  156.34   66.21  156.34
      80  157.66
#Mann= 3 , 0 , 0
       0    .057       0    38.5     .04       0    41.5    .057       0
Bank Sta=38.5,41.5
XS Rating Curve= 0 ,0
Exp/Cntr=0.3,0.1

Type RM Length L Ch R = 1 ,3765.39 ,20.27,18.45,17.11
XS GIS Cut Line= 5
 342576.861511235422158.57891846342597.2567138675422176.54211426
342617.997680664 5422182.0690918342629.0595092775422183.45092773
342648.4177246095422176.54211426
#Sta/Elev= 27
       0  160.37   10.78  157.55   11.61  157.31   11.83  157.21    11.9  157.18
   16.84  154.93   26.43  149.21   27.18  148.68   28.47  147.56   29.15 146.844
   29.41  146.57   29.52   146.4   31.81  146.83   32.44  146.97    36.5  147.92
   37.06  147.97   38.42  148.44   40.67  149.86   48.64  154.92   50.26  155.92
   59.79   157.5   63.84   158.1   63.91   158.1   64.41  158.16   65.49  158.18
   73.68  158.44   80.34  158.47
#Mann= 3 , 0 , 0
       0     .05       0   29.15     .04       0   32.44    .055       0
Bank Sta=29.15,32.44
XS Rating Curve= 0 ,0
Exp/Cntr=0.3,0.1

Type RM Length L Ch R = 1 ,3746.94 ,22.98,22,21.23
XS GIS Cut Line= 3
342561.0084838875422187.10968018342586.7915039065422195.47210693
342638.5668945315422196.66247559
#Sta/Elev= 22
       0  158.93    3.85  158.28    7.82  156.32   14.17  152.84   14.72  152.67
   17.28  151.55   27.11  147.72   29.86  146.75   30.07  146.71   30.84  146.64
   37.39  146.04    39.9  145.76   40.39  145.96   46.84  147.74   53.38  152.99
   53.81  153.33   56.08     155   58.48   155.2    66.9  156.56   71.46  156.74
   73.79  156.76   78.89  156.85
#Mann= 3 , 0 , 0
       0     .05       0   37.39     .04       0   40.39    .055       0
Bank Sta=37.39,40.39
XS Rating Curve= 0 ,0
Exp/Cntr=0.3,0.1

Type RM Length L Ch R = 1 ,3724.94 ,27.76,27.24,26.33
XS GIS Cut Line= 3
342570.6392822275422220.41351318342615.9235229495422215.92272949
342635.6275024415422200.37768555
#Sta/Elev= 24
       0  153.89    6.26  153.56    10.8  152.93   18.99  151.98    19.1  151.92
   19.52  151.69   29.12  145.98   30.49  145.63   31.27  145.32   32.68 145.932
    33.5  146.23   34.03  146.42   35.91  146.96   44.52   153.2   44.95  153.59
    45.3  153.65   45.51  153.66   46.88  153.74   51.08  153.88   53.58  154.72
   58.88  156.33    59.1   156.4   66.82  156.59    70.6   156.7
#Mann= 3 , 0 , 0
       0     .05       0   29.12     .04       0   32.68    .055       0
Bank Sta=29.12,32.68
XS Rating Curve= 0 ,0
Exp/Cntr=0.3,0.1

Type RM Length L Ch R = 1 ,3697.71 ,22.04,20,17.15
Node Photo=..\..\..\..\Corner Brook\Windshield Survey\CB photos\P1000751.JPG
XS GIS Cut Line= 4
342561.8685302735422255.54052734342586.4251098635422248.84692383
342614.6818847665422238.80328369342631.7954711915422228.23028564
#Sta/Elev= 25
       0  153.79    2.65  153.71    9.11  153.55   10.53  153.48   19.78   152.7
   25.05  152.11   25.45  152.09   26.02  152.06    28.9   151.9   29.11  151.85
   31.24  150.32   38.75  145.57    39.4  145.05   41.75  145.36   42.76  145.38
   44.21  145.39    48.8  148.72   54.24  152.32   55.44  152.51   57.42  152.82
   60.11   152.9   64.89  153.79   66.74  153.89   72.25  154.15   75.56  154.42
#Mann= 3 , 0 , 0
       0    .045       0   38.75     .04       0   41.75    .045       0
Bank Sta=38.75,41.75
XS Rating Curve= 0 ,0
Exp/Cntr=0.3,0.1

Type RM Length L Ch R = 1 ,3677.71 ,34.81,34.51,34.92
Node Photo=..\..\..\..\Corner Brook\Windshield Survey\CB photos\P1000749.JPG
XS GIS Cut Line= 5
      342581.381     5422290.777       342594.88     5422278.356
      342603.139     5422265.964      342616.658     5422253.301
      342632.211     5422233.107
#Sta/Elev= 26
       0     152   10.91     151   21.78     151   29.05     150   31.21     149
   32.43     148   33.62     147   34.61     146   35.74     145   36.54  144.12
   37.06  143.68   37.33  143.53   37.79  143.44   40.14  143.84   41.43  144.15
   43.09  144.49    44.2     145   45.94     146   47.97     147   49.82     148
   51.08     149   54.27     151   56.13     152   66.35     153   75.42     154
   77.25     154
#Mann= 3 , 0 , 0
       0    .045       0   36.54     .04       0   41.43    .045       0
#XS Ineff= 2 , 0
       0   36.59   149.5   38.99       0   149.5
Permanent Ineff=
       F       F
Bank Sta=36.54,41.43
XS Rating Curve= 0 ,0
Exp/Cntr=0.5,0.3

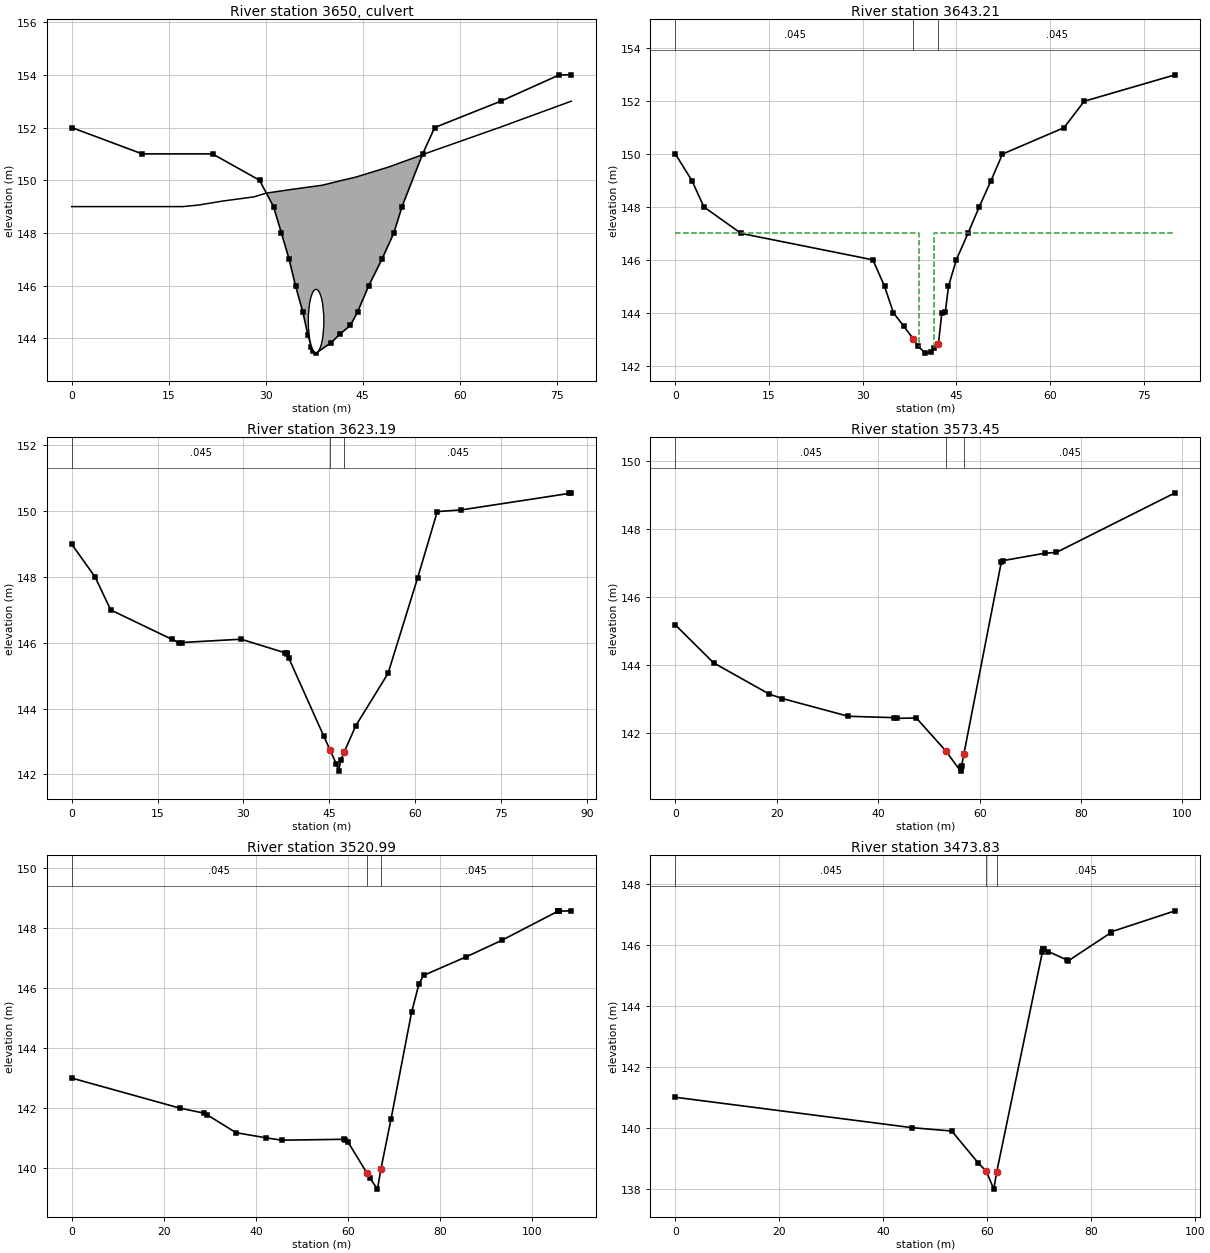
Type RM Length L Ch R = 2 ,3650    ,,,
Node Photo=..\..\..\..\Corner Brook\Windshield Survey\CB photos\P1000746.JPG
BEGIN DESCRIPTION:
Carberry's Road (Structure #2127)
END DESCRIPTION:
Bridge Culvert--1,0,-1,-1, 0
Deck Dist Width WeirC Skew NumUp NumDn MinLoCord MaxHiCord MaxSubmerge Is_Ogee
12.2,10.2,1.67,0, 15, 14, 149.44, , 0.98, 0, 0.62,0.76,,
       0   17.22   19.66   23.35   28.22   30.05   33.94   38.73   41.87   43.94
   48.86   54.62   55.37   66.12   77.25
     149     149  149.06  149.21  149.37  149.51  149.65  149.81     150  150.12
  150.49     151  151.07     152     153
                                                                                
                                        
       0   24.65   24.76   28.41   32.51   37.42      42   46.32   46.94   50.66
   56.34   60.32   71.97   80.01
     149     149     149  149.21  149.37  149.52   149.7  149.99     150   150.3
  150.67     151     152     153
                                                                                
                                
BR Coef=-1 , 0 , 0 ,, 0 ,,,0.8,-1,,0,
WSPro=,,,, 1 ,,,, 0 ,,,, 0 ,,,,-1 ,-1 ,-1 , 0 , 0 , 0 , 0 , 0
Culvert=1,2.4,,30.7,0.03,0.9,1,1,1,143.46,37.79,142.68,40.22,Culvert #1  , 0 ,2.1
Culvert Bottom n=0.03
BC Design=,, 0 ,, 0 ,,,,,,
BC Use User HTab Curves=0
BC User HTab FreeFlow(D)= 0

Type RM Length L Ch R = 1 ,3643.21 ,17.56,20,22.18
Node Photo=..\..\..\..\Corner Brook\Windshield Survey\CB photos\P1000748.JPG
XS GIS Cut Line= 2
 342605.160278325422320.60687256342654.2156982425422257.41229248
#Sta/Elev= 25
       0     150    2.63     149    4.56     148   10.51     147   31.62     146
   33.48     145    34.9     144   36.58  143.48   38.12     143   38.78  142.75
      40  142.47   40.99  142.53   41.34  142.65   42.11  142.82   42.66     144
   43.23  144.04   43.72     145   44.98     146   46.84     147   48.64     148
   50.54     149   52.36     150   62.22     151   65.46     152   80.01     153
#Mann= 3 , 0 , 0
       0    .045       0   38.12    .037       0   42.11    .045       0
#XS Ineff= 2 , 0
       0   39.02     147   41.42       0     147
Permanent Ineff=
       F       F
Bank Sta=38.12,42.11
XS Rating Curve= 0 ,0
Exp/Cntr=0.5,0.3

Type RM Length L Ch R = 1 ,3623.19 ,45.75,49.75,47.66
XS GIS Cut Line= 6
      342599.877     5422326.922      342609.182      5422328.25
      342616.302     5422324.453      342630.463     5422310.096
      342658.831     5422299.194      342664.661     5422280.874
#Sta/Elev= 24
       0     149     4.1     148    6.82     147   17.46  146.11   18.67  146.01
   19.27  146.01   29.59  146.11    37.2   145.7   37.57  145.69   37.63  145.67
   37.93  145.53   43.98  143.18   45.14 142.733   46.24  142.31   46.62   142.1
   46.98  142.44   47.61 142.689   49.61  143.48   55.24  145.07   60.42  147.98
   63.84  149.99   68.02  150.04    86.8  150.54   87.24  150.56
#Mann= 3 , 0 , 0
       0    .045       0   45.14    .037       0   47.61    .045       0
Bank Sta=45.14,47.61
XS Rating Curve= 0 ,0
Exp/Cntr=0.3,0.1

Type RM Length L Ch R = 1 ,3573.45 ,56.75,52.46,47.62
XS GIS Cut Line= 4
 342620.548889165422354.88171387342641.6436767585422355.42492676
342688.629272461 5422333.4296875342690.1923217775422307.91412354
#Sta/Elev= 19
       0  145.18    7.51  144.07   18.51  143.15    21.1  143.02    34.1   142.5
   43.12  142.46   43.71  142.44   47.51  142.45   53.28  141.49   56.23  140.89
   56.31  140.98   56.36     141   56.42  141.04   56.87 141.383   64.27  147.03
   64.62  147.07   72.98  147.29   75.11  147.31   98.54  149.06
#Mann= 3 , 0 , 0
       0    .045       0   53.28    .037       0   56.87    .045       0
Bank Sta=53.28,56.87
XS Rating Curve= 0 ,0
Exp/Cntr=0.3,0.1

Type RM Length L Ch R = 1 ,3520.99 ,56.39,47.15,45.97
XS GIS Cut Line= 6
      342647.911     5422397.571      342664.004     5422399.782
       342674.72     5422392.047      342690.795     5422393.634
      342713.301     5422351.502      342716.094     5422336.707
#Sta/Elev= 26
       0     143   23.44     142   28.74  141.83   29.46  141.77   35.68  141.18
   42.13  141.01   45.61  140.93   59.09  140.96   59.36  140.94   59.93  140.88
    64.1  139.83   64.72  139.67   66.37   139.3    67.1  139.96   69.33  141.65
   73.77  145.19   75.38  146.14   76.37  146.42   85.66  147.04   93.38  147.59
  105.57  148.56  105.61  148.56  105.62  148.56  105.67  148.56  105.81  148.56
  108.43  148.57
#Mann= 3 , 0 , 0
       0    .045       0    64.1    .037       0    67.1    .045       0
Bank Sta=64.1,67.1
XS Rating Curve= 0 ,0
Exp/Cntr=0.3,0.1

Type RM Length L Ch R = 1 ,3473.83 ,66.63,49.54,47.55
XS GIS Cut Line= 5
      342696.362     5422415.018      342708.325     5422403.506
      342743.513     5422393.535      342748.478     5422372.008
      342738.942     5422353.433
#Sta/Elev= 17
       0     141   45.55     140   53.17  139.89   58.27  138.84   59.84  138.56
   61.26  137.98   61.81 138.534   70.63  145.79   70.72  145.87   70.74  145.87
   70.86  145.88   71.77  145.79   75.27  145.52   75.63  145.49   83.78  146.41
   83.86  146.44   96.15  147.13
#Mann= 3 , 0 , 0
       0    .045       0   59.84    .037       0   61.81    .045       0
Bank Sta=59.84,61.81
XS Rating Curve= 0 ,0
Exp/Cntr=0.3,0.1

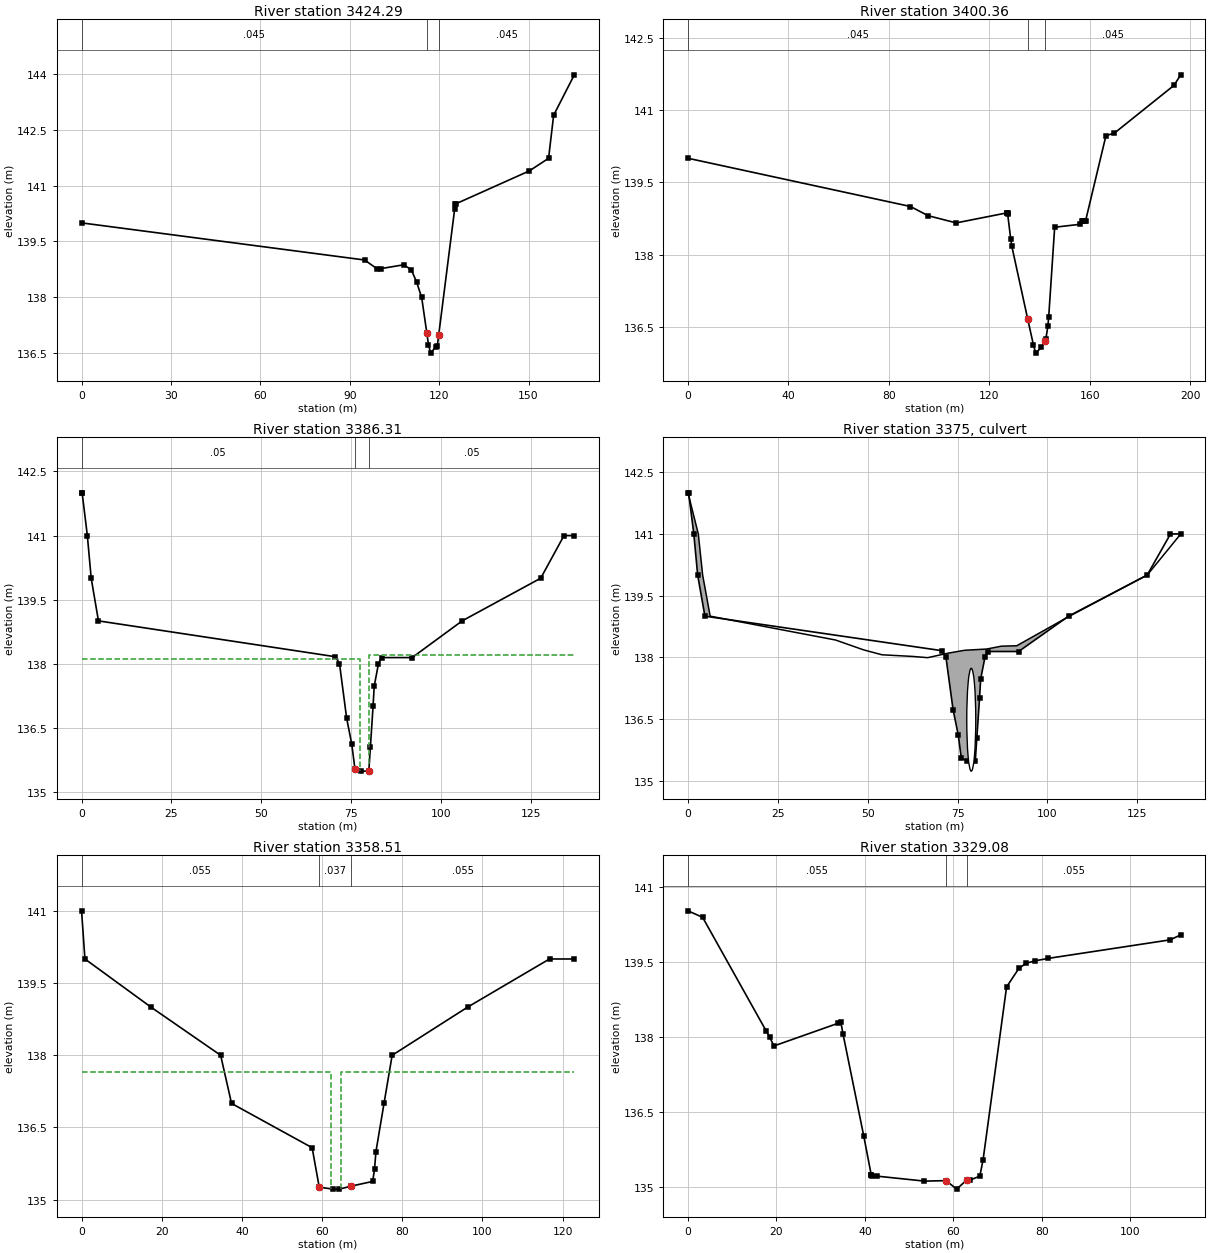
Type RM Length L Ch R = 1 ,3424.29 ,8.23,23.93,32.98
XS GIS Cut Line= 4
342741.0263061525422475.42547607342798.7764892585422393.02508545
342778.0883178715422347.92071533342764.7338867195422340.83691406
#Sta/Elev= 21
       0     140   94.97     139   99.23  138.76  100.62  138.77  108.07  138.87
  110.64  138.74  112.42  138.41  114.14  137.99  115.87  137.03  116.42  136.72
  117.15  136.49  118.87  136.66  119.38  136.68  119.85 136.978  125.22  140.38
  125.42  140.51   125.5  140.51  150.25   141.4  156.72  141.74  158.42   142.9
  165.36  143.99
#Mann= 3 , 0 , 0
       0    .045       0  115.87    .037       0  119.85    .045       0
Bank Sta=115.87,119.85
XS Rating Curve= 0 ,0
Exp/Cntr=0.3,0.1

Type RM Length L Ch R = 1 ,3400.36 ,30.11,14.07,14.53
Node Photo=..\..\..\..\Corner Brook\Windshield Survey\CB photos\P1000743.JPG
XS GIS Cut Line= 5
342741.6364746095422476.37109375 342803.951110845422421.63049316
342806.5554809575422376.14929199342815.2952880865422363.81768799
342817.5844726565422311.28552246
#Sta/Elev= 28
       0     140   88.58     139   95.56  138.81  106.78  138.66  127.17  138.87
  127.19  138.87  127.21  138.86  127.26  138.85   128.5  138.32  128.91  138.18
  135.28  136.66  137.53  136.13  138.42  135.96  140.73  136.08  142.16  136.22
  142.51  136.26  143.28  136.52  143.61  136.71  145.99  138.57  155.92  138.63
  156.89   138.7  157.45   138.7  158.21   138.7  158.28   138.7  166.41  140.47
  169.73  140.52  193.46  141.51   196.2  141.73
#Mann= 3 , 0 , 0
       0    .045       0  135.28    .037       0  142.16    .045       0
Bank Sta=135.28,142.16
XS Rating Curve= 0 ,0
Exp/Cntr=0.3,0.1

Type RM Length L Ch R = 1 ,3386.31 ,29.51,27.8,27.54
Node Photo=..\..\..\..\Corner Brook\Windshield Survey\CB photos\P1000744.JPG
XS GIS Cut Line= 4
 342822.208923345422442.65411377 342815.560729985422397.39172363
342839.7583007815422332.14831543342843.3023071295422310.68652344
#Sta/Elev= 22
       0     142     .16     142    1.61     141    2.68     140     4.7     139
   70.64  138.16   71.76     138   73.75  136.72   75.18  136.11   76.04  135.54
   77.68  135.48   79.92  135.48   80.35 136.034    81.1     137   81.42  137.47
   82.61     138   83.45  138.14   91.97  138.14  105.89     139  127.75     140
  134.23     141  137.09     141
#Mann= 3 , 0 , 0
       0     .05       0   76.04    .037       0   79.92     .05       0
#XS Ineff= 2 , 0
       0   77.55   138.1   80.05       0   138.2
Permanent Ineff=
       F       F
Bank Sta=76.04,79.92
XS Rating Curve= 0 ,0
Exp/Cntr=0.5,0.3

Type RM Length L Ch R = 2 ,3375    ,,,
Node Photo=..\..\..\..\Corner Brook\Windshield Survey\CB photos\P1000739.JPG
BEGIN DESCRIPTION:
Reids Road (Structure #2126)
END DESCRIPTION:
Bridge Culvert--1,0,-1,-1, 0
Deck Dist Width WeirC Skew NumUp NumDn MinLoCord MaxHiCord MaxSubmerge Is_Ogee
8.57,9.2,1.67,0, 17, 15, 138.02, , 0.98, 0, 0,0,,
       0    2.86    4.07    6.16   41.02   48.84   53.97   62.53   66.68   72.38
   76.97   83.09   87.19   91.46  106.13  127.75  137.09
     142     141     140     139  138.42  138.18  138.06  138.02  137.99   138.1
  138.17   138.2  138.27  138.28     139     140     141
                                                                                
                                                        
       0    3.53   30.69   36.27   41.89   50.14   54.71   59.64   65.76    71.3
   75.32   79.43   96.32  116.75  122.94
     140     139  138.42  138.18  138.06  138.04  137.95  138.05  138.12   138.2
  138.27  138.28     139     140     140
                                                                                
                                        
BR Coef=-1 , 0 , 0 ,, 0 ,,,0.8,-1,,0,
WSPro=,,,, 1 ,,,, 0 ,,,, 0 ,,,,-1 ,-1 ,-1 , 0 , 0 , 0 , 0 , 0
Culvert=1,2.5,,25.2,0.03,0.5,1,1,1,135.23,78.8,134.96,63.58,Culvert #1  , 0 ,1.3
Culvert Bottom n=0.035
Culvert Bottom Depth=0.25
Culvert Depth Blocked=0.25
BC Design=,, 0 ,, 0 ,,,,,,
BC Use User HTab Curves=0
BC User HTab FreeFlow(D)= 0

Type RM Length L Ch R = 1 ,3358.51 ,36.84,29.41,25.17
Node Photo=..\..\..\..\Corner Brook\Windshield Survey\CB photos\P1000740.JPG
XS GIS Cut Line= 4
 342850.251892095422435.83587646342847.4329223635422392.70129395
342864.3112792975422342.42590332342877.2770996095422319.11187744
#Sta/Elev= 18
       0     141     .84     140   17.32     139    34.7     138   37.42     137
   57.53  136.08    59.3  135.26   62.84  135.22   64.33  135.22   67.14  135.28
   72.63  135.38   73.09  135.63   73.45     136   75.46     137   77.49     138
   96.32     139  116.75     140  122.94     140
#Mann= 3 , 0 , 0
       0    .055       0    59.3    .037       0   67.14    .055       0
#XS Ineff= 2 , 0
       0   62.33  137.65   64.83       0  137.65
Permanent Ineff=
       F       F
Bank Sta=59.3,67.14
XS Rating Curve= 0 ,0
Exp/Cntr=0.5,0.3

Type RM Length L Ch R = 1 ,3329.08 ,15.08,25.53,28.83
Node Photo=..\..\..\..\Corner Brook\Windshield Survey\CB photos\P1000738.JPG
XS GIS Cut Line= 4
342878.4979248055422428.72991943342884.5581054695422375.60827637
342876.9606933595422348.64331055342884.4547119145422319.64312744
#Sta/Elev= 27
       0  140.52     3.3  140.39   17.74  138.11   18.51  137.99   19.41  137.82
   33.83  138.27   34.57  138.29   35.07  138.05   39.72  136.03   41.42  135.25
   41.49  135.24   41.61  135.23   42.68  135.22   53.47  135.12   58.35  135.13
   60.74  134.96      63  135.14   63.78  135.14   65.99  135.22   66.73  135.55
   72.04     139   74.82  139.37    76.4  139.47    78.4  139.52   81.48  139.57
  109.01  139.94  111.43  140.04
#Mann= 3 , 0 , 0
       0    .055       0   58.35    .037       0      63    .055       0
Bank Sta=58.35,63
XS Rating Curve= 0 ,0
Exp/Cntr=0.3,0.1

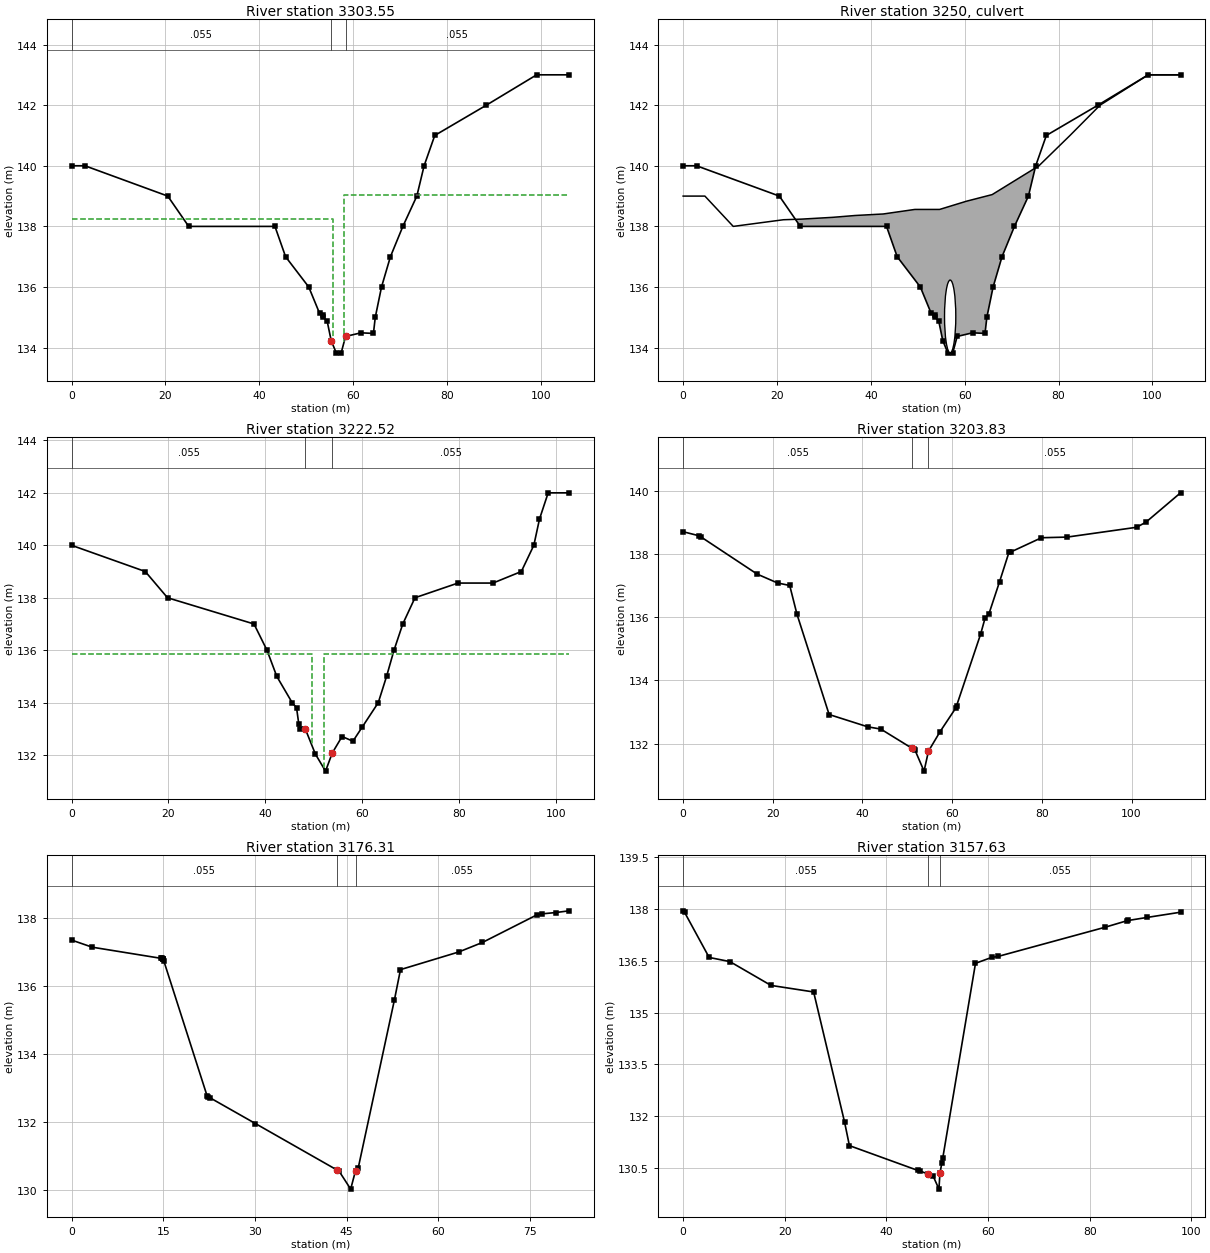
Type RM Length L Ch R = 1 ,3303.55 ,77.91,81.04,82.42
Node Photo=..\..\..\..\Corner Brook\Windshield Survey\CB photos\P1000737.JPG
XS GIS Cut Line= 3
342888.4572753915422435.33532715342897.522888184  5422386.980896
342924.0737304695422336.75268555
#Sta/Elev= 27
       0     140    2.86     140   20.51     139   24.97     138   43.35     138
   45.62     137   50.56     136   52.87  135.13   53.65  135.07   53.66     135
   54.46  134.89   55.34  134.23   56.44  133.82   57.45  133.82    58.4  134.37
   61.68  134.49   64.34  134.47   64.73     135   66.06     136   67.96     137
   70.61     138   73.59     139   75.14     140   77.41     141   88.42     142
   99.12     143  106.01     143
#Mann= 3 , 0 , 0
       0    .055       0   55.34    .037       0    58.4    .055       0
#XS Ineff= 2 , 0
       0   55.71  138.24   58.11       0  139.05
Permanent Ineff=
       F       F
Bank Sta=55.34,58.4
XS Rating Curve= 0 ,0
Exp/Cntr=0.5,0.3

Type RM Length L Ch R = 2 ,3250    ,,,
Node Photo=..\..\..\..\Corner Brook\Windshield Survey\CB photos\P1000734.JPG
BEGIN DESCRIPTION:
Country Road @ O'Connell Drive (Structure #2124)
END DESCRIPTION:
Bridge Culvert--1,0,-1,-1, 0
Deck Dist Width WeirC Skew NumUp NumDn MinLoCord MaxHiCord MaxSubmerge Is_Ogee
23.9,33.7,1.67,0, 17, 16, 138, , 0.98, 0, 0.25,0.19,,
       0    4.64   10.68   21.38    25.2   31.95   36.67   42.65   49.38   54.66
   60.36   65.87   75.83   82.45   88.86   99.12  106.01
     139     139     138  138.22  138.24   138.3  138.36  138.41  138.56  138.56
  138.83  139.05     140     141     142     143     143
                                                                                
                                                        
       0    3.94    8.14   31.38   37.38   45.37   48.09   53.01   60.78   65.68
   71.92    77.6   83.32   93.42  100.05  102.67
     139     139     138  137.16  137.19  137.41  137.29  137.47  137.88  137.91
  138.56  138.83  139.05     140     141     141
                                                                                
                                                
BR Coef=-1 , 0 , 0 ,, 0 ,,,0.8,-1,,0,
WSPro=,,,, 1 ,,,, 0 ,,,, 0 ,,,,-1 ,-1 ,-1 , 0 , 0 , 0 , 0 , 0
Culvert=1,2.4,,73.9,0.03,0.5,1,1,1,133.83,56.91,132.04,50.87,Culvert #1  , 0 ,4.5
Culvert Bottom n=0.03
BC Design=,, 0 ,, 0 ,,,,,,
BC Use User HTab Curves=0
BC User HTab FreeFlow(D)= 0

Type RM Length L Ch R = 1 ,3222.52 ,20.45,18.68,16.9
Node Photo=..\..\..\..\Corner Brook\Windshield Survey\CB photos\P1000735.JPG
XS GIS Cut Line= 4
 342906.869323735422465.38110352342937.1802978525422457.29949951
 342957.333923345422434.97229004342976.2042846685422398.31750488
#Sta/Elev= 29
       0     140   15.22     139   19.81     138   37.66     137   40.34     136
   42.37     135   45.54     134   46.44  133.81   46.92  133.17   47.23     133
   48.27  132.99   50.33  132.04   52.43  131.39   53.81  132.08   55.84  132.71
   58.08  132.53   60.04 133.081   63.31     134   65.02     135   66.56     136
   68.37     137   70.89     138   79.77  138.56   86.99  138.56   92.84     139
   95.42     140   96.59     141   98.38     142  102.67     142
#Mann= 3 , 0 , 0
       0    .055       0   48.27    .037       0   53.81    .055       0
#XS Ineff= 2 , 0
       0   49.67  135.86   52.07       0  135.86
Permanent Ineff=
       F       F
Bank Sta=48.27,53.81
XS Rating Curve= 0 ,0
Exp/Cntr=0.5,0.3

Type RM Length L Ch R = 1 ,3203.83 ,18.78,27.53,31.97
XS GIS Cut Line= 6
342919.8419189455422471.01928711342960.0792846685422462.17608643
342970.4498901375422445.31829834342977.3635253915422438.68572998
342992.1586914065422435.92230225343008.4749145515422416.57727051
#Sta/Elev= 29
       0   138.7     3.6  138.57    4.04  138.53   16.51  137.36   21.05  137.08
   23.77     137   25.39  136.09   32.56  132.92    41.2  132.53   44.08  132.46
   51.07  131.85   51.42  131.82   51.66  131.81   53.73  131.13   54.71  131.76
   57.31  132.38   60.87  133.14   60.99   133.2   66.34  135.46   67.32  135.96
   68.19   136.1   70.57  137.12   72.69  138.06   73.08  138.06   79.92  138.51
   85.62  138.53  101.11  138.84   103.2     139  110.93  139.93
#Mann= 3 , 0 , 0
       0    .055       0   51.07    .037       0   54.71    .055       0
Bank Sta=51.07,54.71
XS Rating Curve= 0 ,0
Exp/Cntr=0.3,0.1

Type RM Length L Ch R = 1 ,3176.31 ,16.72,18.68,19.25
XS GIS Cut Line= 4
 342934.375122075422480.65289307342948.3464965825422485.50390625
342998.2213134775422469.24047852343003.1815185555422455.98931885
#Sta/Elev= 25
       0  137.35    3.38  137.14   14.72  136.81   14.79  136.81   14.97   136.8
   14.98   136.8   14.99   136.8   15.13  136.72   22.19  132.76   22.28  132.72
   22.74   132.7   30.09  131.95   43.47  130.58   43.78  130.55   45.68  130.02
   46.47  130.56    46.9  130.63   52.84  135.59   53.83  136.48   63.38     137
   67.25  137.28   76.25   138.1   76.94  138.12   79.27  138.16    81.4  138.21
#Mann= 3 , 0 , 0
       0    .055       0   43.47    .037       0   46.47    .055       0
Bank Sta=43.47,46.47
XS Rating Curve= 0 ,0
Exp/Cntr=0.3,0.1

Type RM Length L Ch R = 1 ,3157.63 ,26.95,27.53,27.7
XS GIS Cut Line= 4
342934.7797241215422501.48413086342996.0344848635422491.94989014
343011.382873535 5422477.7175293343012.3507080085422462.79431152
#Sta/Elev= 24
       0  137.95     .27  137.91    5.12   136.6     9.2  136.48   17.29  135.79
   25.68   135.6   31.77  131.83   32.72  131.15   46.21  130.43   46.52  130.42
   48.14  130.33   49.22  130.26   50.34  129.89   50.53 130.343   50.91  130.65
   51.09  130.79   57.53  136.43    60.7   136.6   61.99  136.63   82.92  137.47
   87.26  137.66   87.57  137.67   91.35  137.76   97.88  137.91
#Mann= 3 , 0 , 0
       0    .055       0   48.14    .037       0   50.53    .055       0
Bank Sta=48.14,50.53
XS Rating Curve= 0 ,0
Exp/Cntr=0.3,0.1

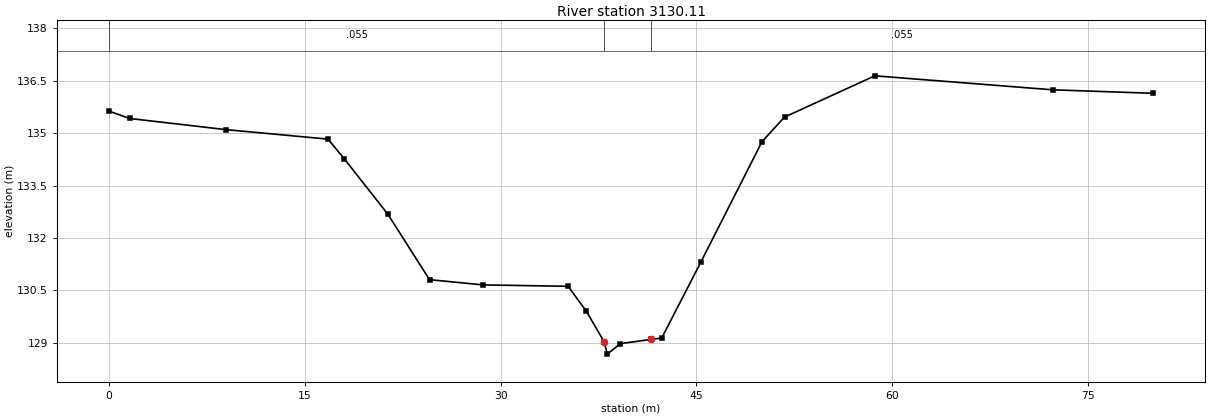
Type RM Length L Ch R = 1 ,3130.11 ,47.22,46.27,43.59
XS GIS Cut Line= 2
342944.3775024415422525.39831543343024.0010986335422517.64727783
#Sta/Elev= 21
       0  135.63    1.57  135.42    8.98   135.1   16.77  134.83   18.01  134.27
   21.36  132.68   24.55  130.81   28.64  130.66   35.17  130.62   36.56  129.91
   37.94 129.027   38.17  128.68   39.17  128.98    41.5   129.1   42.34  129.14
   45.35  131.32   50.03  134.76   51.75  135.46   58.67  136.64   72.29  136.24
      80  136.14
#Mann= 3 , 0 , 0
       0    .055       0   37.94    .037       0    41.5    .055       0
Bank Sta=37.94,41.5
XS Rating Curve= 0 ,0
Exp/Cntr=0.3,0.1