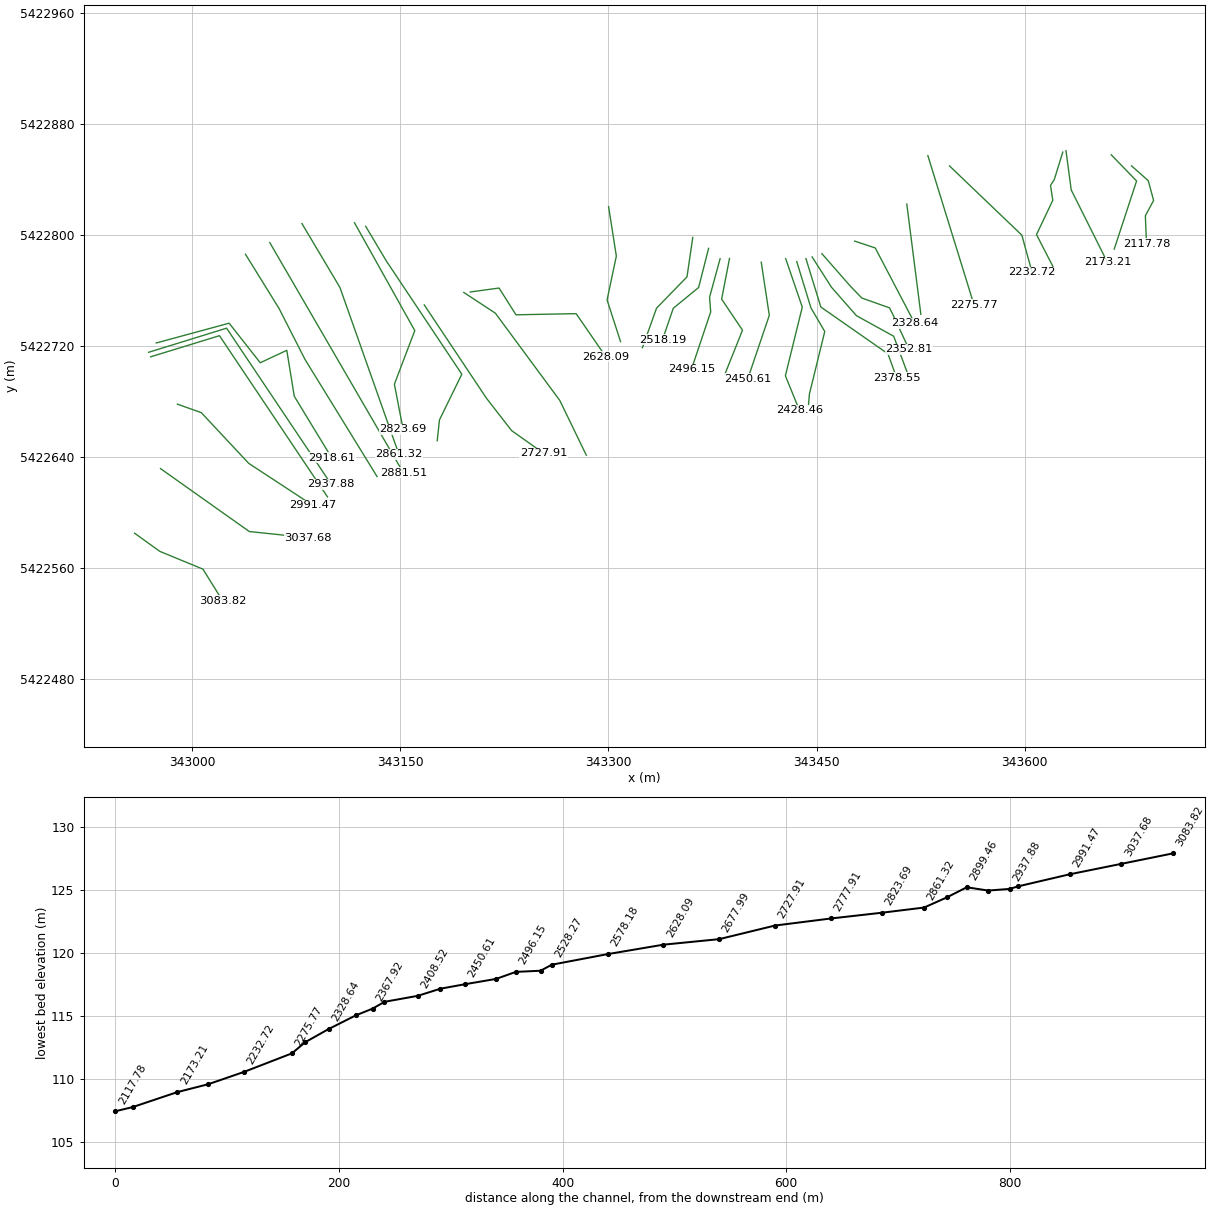
HEC-RAS study Corner_Brook2.prj: Corner_Brook2

--- Corner_Brook2.g02 (geometry) --- (continued)

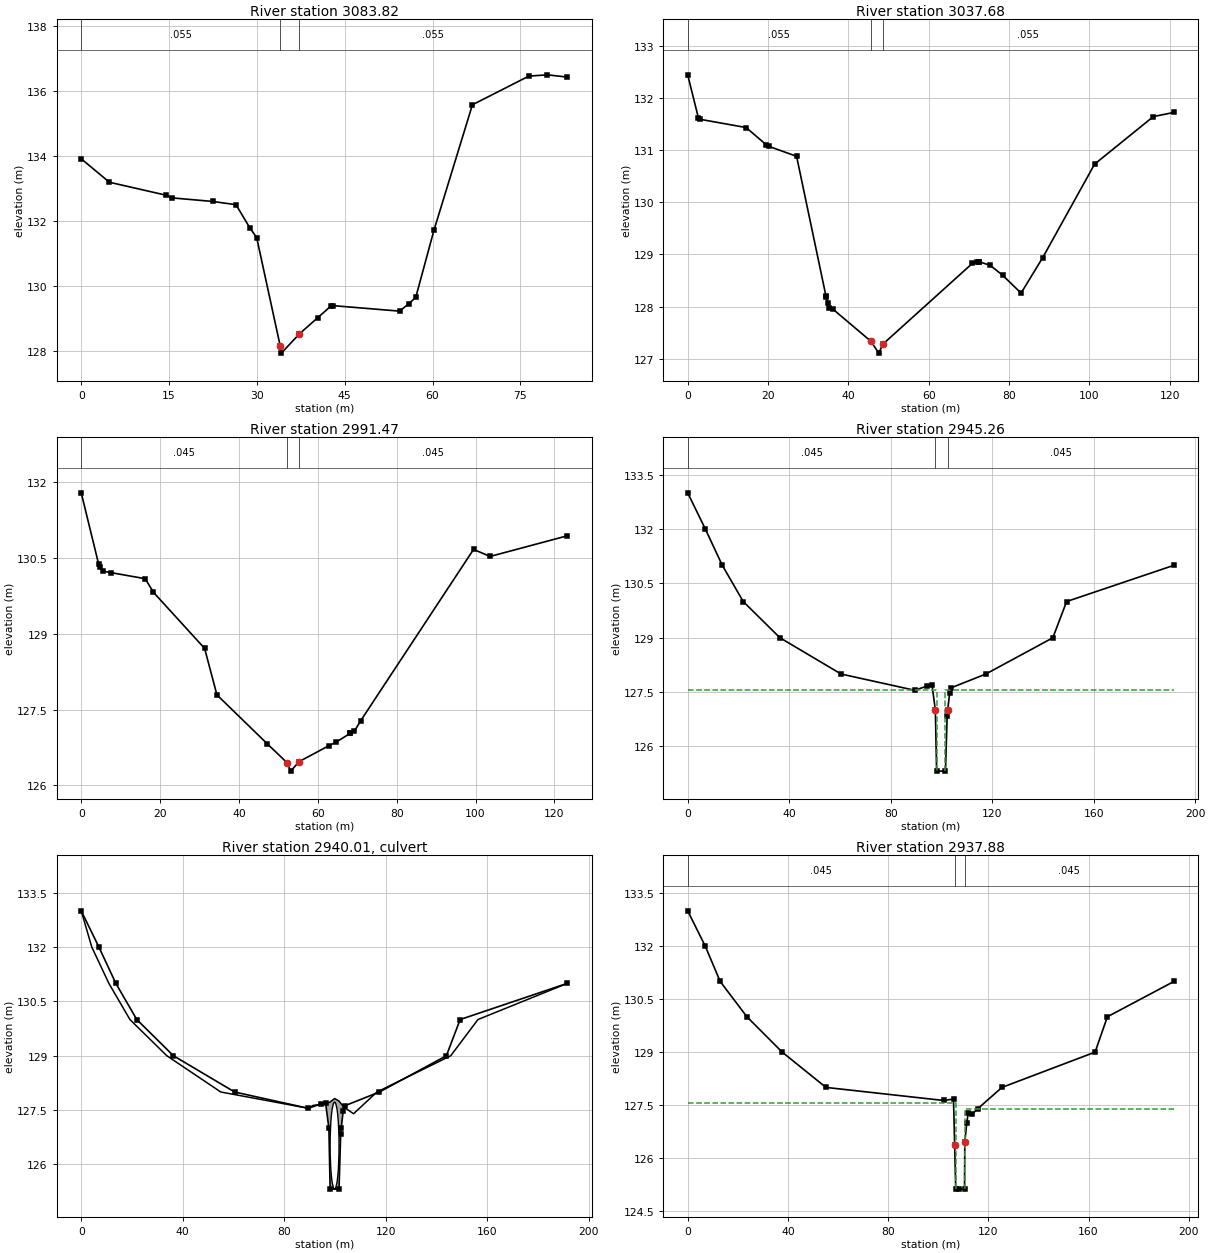
Type RM Length L Ch R = 1 ,3083.82 ,47.22,46.14,46.83
XS GIS Cut Line= 4
 342958.537292485422585.16668701342976.7575073245422572.07971191
343007.7532958985422559.33209229343022.0814819345422536.35168457
#Sta/Elev= 22
       0  133.91    4.81  133.19   14.53  132.79   15.47  132.71   22.43   132.6
   26.43   132.5   28.82  131.78   29.96  131.49   33.98  128.16   34.17  127.94
   37.25  128.53   40.39  129.03   42.66  129.39   42.94   129.4   54.37  129.23
   55.95  129.46   57.12  129.65   60.24  131.72    66.8  135.57   76.43  136.45
    79.6  136.49   83.03  136.42
#Mann= 3 , 0 , 0
       0    .055       0   33.98    .037       0   37.25    .055       0
Bank Sta=33.98,37.25
XS Rating Curve= 0 ,0
Exp/Cntr=0.3,0.1

Type RM Length L Ch R = 1 ,3037.68 ,49.3,46.21,45.52
XS GIS Cut Line= 3
342977.193115234 5422631.7020874 343041.185485845422586.40209961
343083.5668945315422581.93988037
#Sta/Elev= 26
       0  132.44    2.68  131.61    2.95  131.59   14.55  131.43   19.56   131.1
   20.19  131.07    27.1  130.88   34.42   128.2   34.51  128.18   34.81  128.07
   35.25  127.98   36.18  127.95   45.55  127.34   47.57  127.11   48.55  127.28
   70.87  128.83   72.03  128.86   72.45  128.86   72.54  128.86   75.33  128.79
    78.4   128.6   82.98  128.26   88.37  128.94  101.28  130.73  115.89  131.64
  121.02  131.72
#Mann= 3 , 0 , 0
       0    .055       0   45.55    .037       0   48.55    .055       0
Bank Sta=45.55,48.55
XS Rating Curve= 0 ,0
Exp/Cntr=0.3,0.1

Type RM Length L Ch R = 1 ,2991.47 ,58.07,46.21,37.18
Node Photo=..\..\..\..\Corner Brook\Windshield Survey\CB photos\P1000733.JPG
XS GIS Cut Line= 4
342989.3674926765422678.10650635343006.6290893555422671.96868896
343040.7589111335422635.49371338343086.8018798835422605.33392334
#Sta/Elev= 22
       0  131.79    4.41  130.38    4.84  130.32    5.47  130.24    7.54  130.21
   16.22  130.09   18.32  129.82   31.29  128.71   34.41  127.79   47.19  126.82
   52.29  126.44   53.11  126.28   55.29  126.47   62.73  126.78   64.53  126.85
   68.27  127.03   68.28  127.03   69.28  127.07   70.89  127.28    99.5  130.67
  103.68  130.53  123.31  130.94
#Mann= 3 , 0 , 0
       0    .045       0   52.29    .037       0   55.29    .045       0
Bank Sta=52.29,55.29
XS Rating Curve= 0 ,0
Exp/Cntr=0.3,0.1

Type RM Length L Ch R = 1 ,2945.26 ,7.49,7.38,7.56
Node Photo=..\..\..\..\Corner Brook\Windshield Survey\CB photos\P1000730.JPG
XS GIS Cut Line= 3
       342970.06     5422712.187      343019.685     5422727.405
      343097.517     5422611.367
#Sta/Elev= 20
       0     133    6.96     132   13.63     131   21.89     130   36.36     129
   60.45     128   89.52  127.55   94.37  127.67   96.31  127.69   97.61     127
    98.1  125.32   101.6  125.32  102.25  126.84  102.45     127  103.24  127.47
  103.87  127.62  117.51     128  143.91     129  149.33     130  191.63     131
#Mann= 3 , 0 , 0
       0    .045       0   97.61    .037       0  102.45    .045       0
#XS Ineff= 2 , 0
       0    98.1  127.55   101.6       0  127.57
Permanent Ineff=
       F       F
Bank Sta=97.61,102.45
XS Rating Curve= 0 ,0
Exp/Cntr=0.5,0.3

Type RM Length L Ch R = 2 ,2940.01 ,,,
Node Photo=..\..\..\..\Corner Brook\Windshield Survey\CB photos\P1000732.JPG
BEGIN DESCRIPTION:
Driveway (Structure #2123)
END DESCRIPTION:
Bridge Culvert--1,0,-1,-1, 0
Deck Dist Width WeirC Skew NumUp NumDn MinLoCord MaxHiCord MaxSubmerge Is_Ogee
1,5.5,1.67,0, 19, 18, 127.55, , 0.98, 0, 0,0,,
       0    4.16   10.88   19.19   33.75   55.01   89.55   91.35   95.95   97.99
   99.87   101.6  102.49   103.8  107.32  116.54  145.62  156.35  191.63
     133     132     131     130     129     128  127.55  127.63  127.67  127.72
  127.82  127.75  127.67  127.57   127.4     128     129     130     131
                                                                                
                                                                        
       0    7.01   12.97   23.64   37.71   55.19   98.45  102.12  106.29  106.87
  109.55  110.71  112.69  115.87  125.43  162.62  167.52  194.08
     133     132     131     130     129     128  127.55  127.63  127.72  127.71
  127.78  127.69  127.57   127.4     128     129     130     131
                                                                                
                                                                
BR Coef=-1 , 0 , 0 ,, 0 ,,,0.8,-1,,0,
WSPro=,,,, 1 ,,,, 0 ,,,, 0 ,,,,-1 ,-1 ,-1 , 0 , 0 , 0 , 0 , 0
Culvert=5,2.4,3.5,5.5,0.03,0.5,1,41,1,125.32,99.85,125.12,108.74,Culvert #1  , 0 ,1
Culvert Bottom n=0.03
BC Design=,, 0 ,, 0 ,,,,,,
BC Use User HTab Curves=0
BC User HTab FreeFlow(D)= 0

Type RM Length L Ch R = 1 ,2937.88 ,4.94,19.28,13.14
Node Photo=..\..\..\..\Corner Brook\Windshield Survey\CB photos\P1000731.JPG
XS GIS Cut Line= 3
342968.6340942385422715.44329834343024.8264770515422732.81750488
 343100.17590332  5422620.480896
#Sta/Elev= 21
       0     133    7.01     132   12.97     131   23.64     130   37.71     129
   55.19     128  102.16  127.63   106.1  127.67  106.55 126.381  106.99  125.12
  108.34  125.12  110.49  125.12  110.62  126.45  111.38     127  112.01  127.28
  113.63  127.25  115.83   127.4  125.43     128  162.62     129  167.52     130
  194.08     131
#Mann= 3 , 0 , 0
       0    .045       0  106.55    .037       0  110.62    .045       0
#XS Ineff= 2 , 0
       0  106.99  127.55  110.49       0   127.4
Permanent Ineff=
       F       F
Bank Sta=106.55,110.62
XS Rating Curve= 0 ,0
Exp/Cntr=0.5,0.3

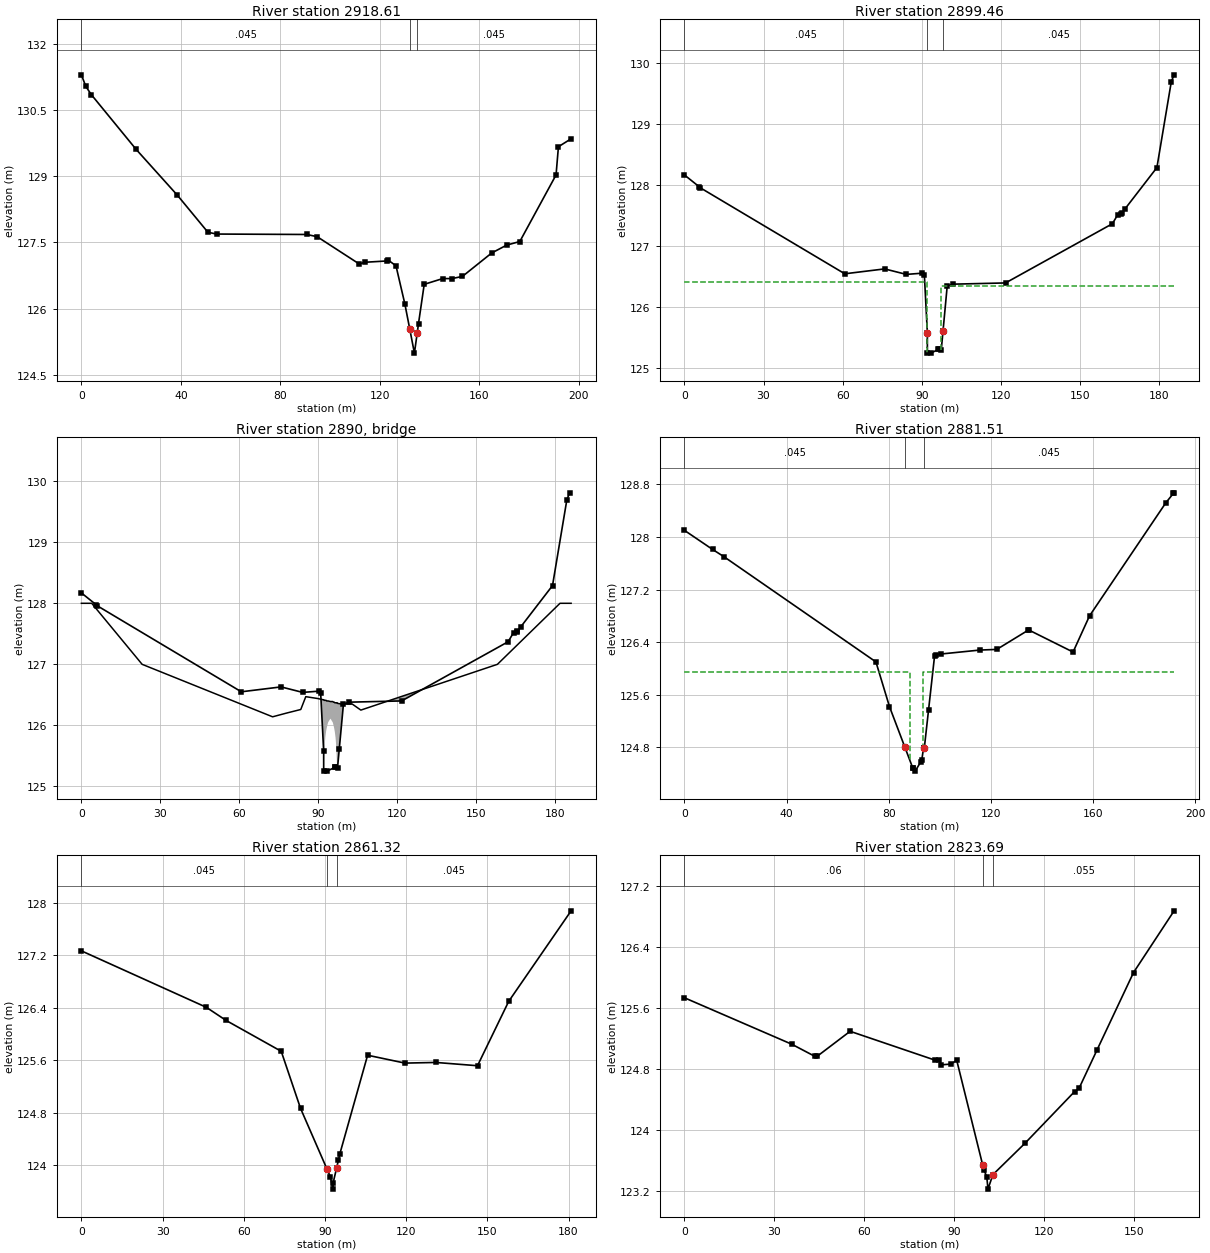
Type RM Length L Ch R = 1 ,2918.61 ,34.67,19.14,22.57
XS GIS Cut Line= 6
342974.1320800785422722.15911865343026.6691284185422736.40472412
343049.0684814455422707.91351318343068.2098999025422716.86791992
343073.5969238285422683.78411865343100.4652709965422639.64147949
#Sta/Elev= 29
       0   131.3    1.75  131.04       4  130.85   22.01  129.61   38.61  128.57
    50.9  127.73   54.43  127.69   90.68  127.68   94.84  127.63  111.81  127.01
  113.97  127.05  123.01  127.08  123.39   127.1  126.55  126.97   130.1  126.11
  132.08  125.54  133.96  124.99  135.08  125.44  135.61  125.66  137.91  126.55
  145.33  126.68   149.1  126.68  153.29  126.73  165.04  127.26  171.11  127.44
  176.36  127.52  190.94  129.03   191.9  129.67     197  129.85
#Mann= 3 , 0 , 0
       0    .045       0  132.08    .037       0  135.08    .045       0
Bank Sta=132.08,135.08
XS Rating Curve= 0 ,0
Exp/Cntr=0.3,0.1

Type RM Length L Ch R = 1 ,2899.46 ,18.33,17.95,18.23
Node Photo=..\..\..\..\Corner Brook\Windshield Survey\CB photos\P1000728.JPG
XS GIS Cut Line= 4
      343038.424     5422786.044      343062.654     5422746.953
      343081.347     5422710.283      343133.261     5422625.989
#Sta/Elev= 26
       0  128.17     5.5  127.98       6  127.96   60.79  126.55    75.9  126.63
   84.12  126.54   90.21  126.56   90.95  126.53   92.09  125.58    92.1  125.25
   93.37  125.25   96.25  125.31    96.4  125.31   97.35   125.3   98.03 125.616
   99.61  126.35  101.81  126.38  121.72   126.4  162.21  127.37  164.27  127.52
  165.59  127.53  165.75  127.54  166.94  127.61  179.08  128.29  184.55   129.7
   185.6  129.81
#Mann= 3 , 0 , 0
       0    .045       0   92.09    .035       0   98.03    .045       0
#XS Ineff= 2 , 0
       0    92.1  126.42   97.19       0  126.35
Permanent Ineff=
       F       F
Bank Sta=92.09,98.03
XS Rating Curve= 0 ,0
Exp/Cntr=0.5,0.3

Type RM Length L Ch R = 3 ,2890    ,,,
Node Photo=..\..\..\..\Corner Brook\Windshield Survey\CB photos\P1000726.JPG
BEGIN DESCRIPTION:
Boones Road (Structure #2122)
END DESCRIPTION:
Bridge Culvert--1,0,-1,-1, 0
Deck Dist Width WeirC Skew NumUp NumDn MinLoCord MaxHiCord MaxSubmerge Is_Ogee
3.3,6.8,1.67,0, 39, 37, 126.14, , 0.98, 0, 0,0,,
       0    3.92   23.08   72.68   77.87   83.39   85.29   89.77   91.88   91.89
   91.93   92.01   92.13   92.29   92.53   92.71   93.01   93.22   93.47   93.79
   94.66   95.53   95.85    96.1   96.31   96.61   96.79   97.03   97.19   97.31
   97.38   97.43   97.44   98.76  102.92  106.22  158.14  181.93  186.15
     128     128     127  126.14   126.2  126.26  126.47  126.44  126.42  126.42
  126.42  126.42  126.42  126.41  126.41  126.41  126.41   126.4   126.4   126.4
  126.39  126.39  126.38  126.38  126.37  126.37  126.37  126.37  126.37  126.36
  126.36  126.36  126.36  126.35  126.35  126.25     127     128     128
                                                                  124.56   124.7
   124.9   125.1   125.3   125.5   125.7   125.8   125.9  125.95     126  126.05
  126.11  126.05     126  125.95   125.9   125.8   125.7   125.5   125.3   125.1
   124.9   124.7  124.56
       0    2.16   21.06   69.01   74.17   79.66   86.02   88.24   88.28   88.33
   88.39   88.52   88.69   88.96   89.16   89.54   89.78   90.08   90.55   91.02
    91.5   91.96   92.26    92.5   92.85   93.09   93.35   93.53   93.65   93.71
   93.76    93.8   97.25  101.94  155.03  179.79  191.76
     128     128     127  126.14   126.2  126.26  126.27  126.27  126.27  126.27
  126.27  126.27  126.27  126.27  126.27  126.27  126.27  126.27  126.27  126.27
  126.26  126.26  126.26  126.26  126.26  126.26  126.26  126.26  126.26  126.26
  126.26  126.26  126.26  126.22     127     128     129
                                                          124.12   124.4  124.56
   124.7   124.9   125.1   125.3   125.4   125.5  125.55   125.6  125.65  125.67
  125.65   125.6  125.55   125.5   125.4   125.3   125.1   124.9   124.7  124.56
   124.4  124.12
BR Coef=-1 , 0 , 0 ,, 0 ,,,0.8,-1,,0,
WSPro=,,,, 1 ,,,, 0 ,,,, 0 ,,,,-1 ,-1 ,-1 , 0 , 0 , 0 , 0 , 0
BC Design=,, 0 ,, 0 ,,,,,,
BC Use User HTab Curves=0
BC User HTab FreeFlow(D)= 0

Type RM Length L Ch R = 1 ,2881.51 ,26.39,20.19,15.85
Node Photo=..\..\..\..\Corner Brook\Windshield Survey\CB photos\P1000727.JPG
XS GIS Cut Line= 2
 343055.954895025422794.41247559343152.2583007815422628.60229492
#Sta/Elev= 26
       0   128.1   11.02  127.81   15.46   127.7      75   126.1   80.31  125.42
   86.32 124.805    89.4  124.49    89.5  124.49   90.37  124.44   92.54  124.58
   92.96  124.61   93.64  124.79   93.94  124.79    95.6 125.368   97.96  126.19
   98.64  126.21  100.43  126.22  115.65  126.28  122.32  126.29  134.53  126.58
  135.12  126.58  152.19  126.25  158.64   126.8  188.54  128.52  191.45  128.66
  191.75  128.67
#Mann= 3 , 0 , 0
       0    .045       0   86.32    .035       0   93.94    .045       0
#XS Ineff= 2 , 0
       0   88.35  125.95    93.6       0  125.95
Permanent Ineff=
       F       F
Bank Sta=86.32,93.94
XS Rating Curve= 0 ,0
Exp/Cntr=0.5,0.3

Type RM Length L Ch R = 1 ,2861.32 ,36.84,37.63,19.88
XS GIS Cut Line= 3
343079.1082763675422808.15112305343106.4719238285422762.20788574
343149.0048828135422642.02648926
#Sta/Elev= 18
       0  127.27   46.17  126.41   53.47  126.21   73.84  125.74   80.98  124.87
   90.66 123.954   91.97  123.83   92.95  123.64   93.05  123.74   94.28 123.958
   94.97  124.08   95.52  124.18  105.76  125.68  119.57  125.56     131  125.57
  146.37  125.52  157.89   126.5  180.96  127.88
#Mann= 3 , 0 , 0
       0    .045       0   90.66    .035       0   94.28    .045       0
Bank Sta=90.66,94.28
XS Rating Curve= 0 ,0
Exp/Cntr=0.3,0.1

Type RM Length L Ch R = 1 ,2823.69 ,30.98,45.79,43.12
XS GIS Cut Line= 4
343116.9957275395422808.70892334 343160.449096685422731.05889893
343145.7584838875422692.48370361343152.0548706055422659.88208008
#Sta/Elev= 21
       0  125.74   35.87  125.13   43.62  124.97   44.25  124.97   55.32   125.3
   83.78  124.92   85.09  124.93   85.64  124.86   88.98  124.87    90.9  124.92
   99.61  123.54  100.02  123.48  100.94  123.39  101.33  123.23  102.98  123.42
  113.65  123.83  130.26  124.51  131.71  124.55  137.67  125.05  149.91  126.07
  163.46  126.88
#Mann= 3 , 0 , 0
       0     .06       0   99.61     .04       0  102.98    .055       0
Bank Sta=99.61,102.98
XS Rating Curve= 0 ,0
Exp/Cntr=0.3,0.1

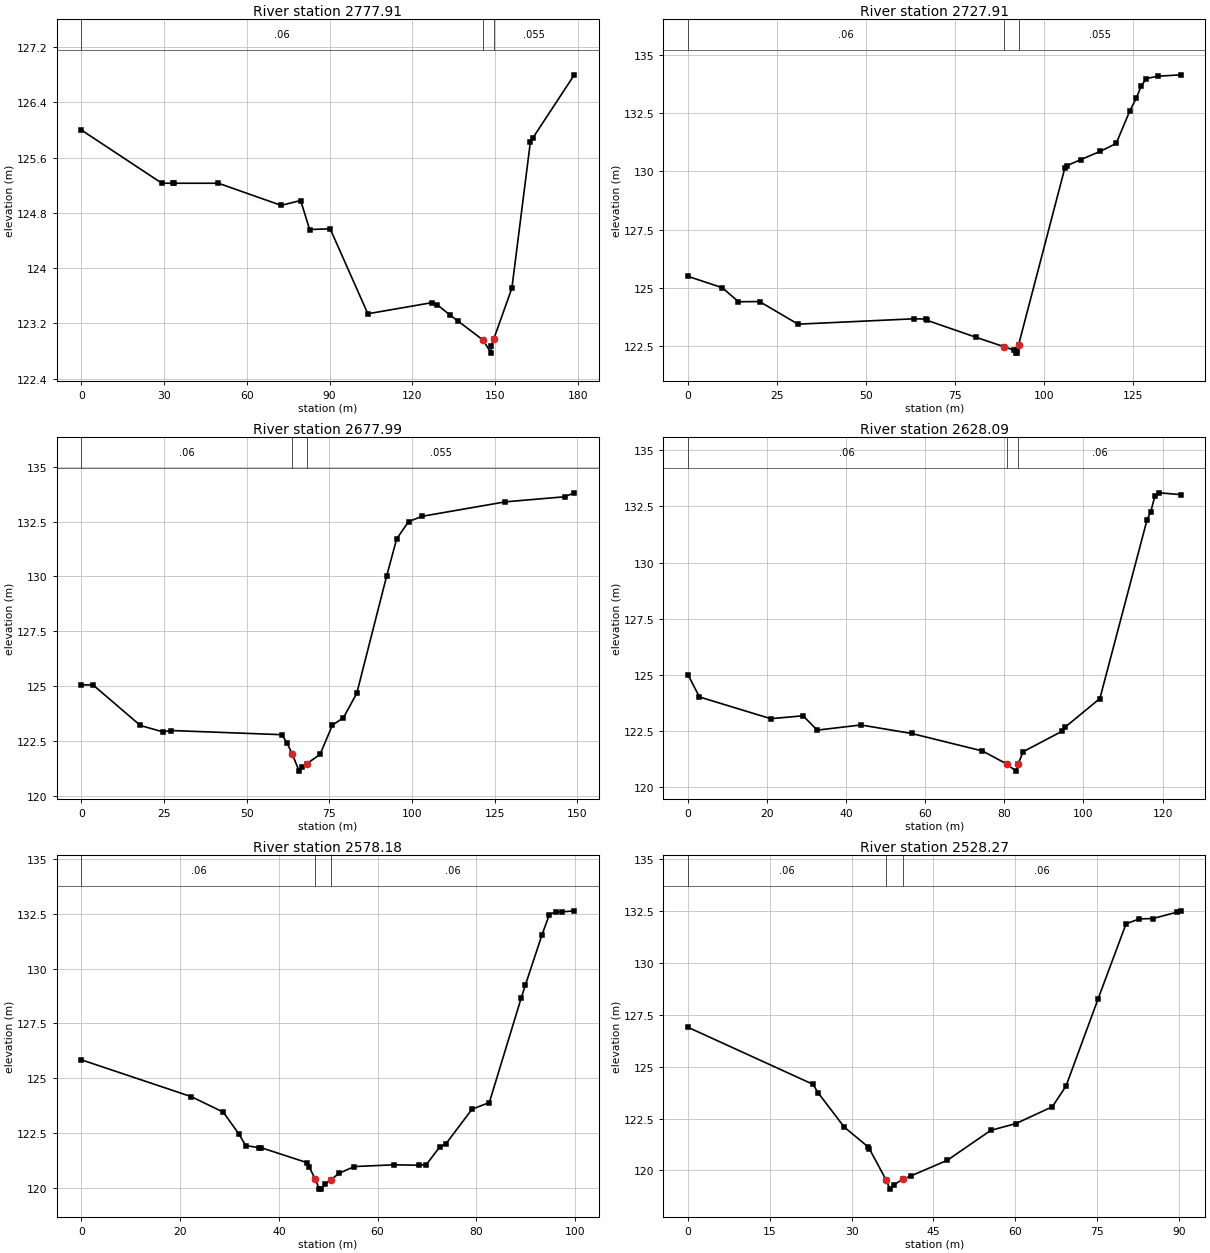
Type RM Length L Ch R = 1 ,2777.91 ,18.27,50,52.04
XS GIS Cut Line= 5
      343125.059     5422806.133      343140.039     5422781.071
      343194.347      5422699.69      343178.237     5422666.772
      343176.616     5422651.727
#Sta/Elev= 22
       0     126   29.19  125.23   33.26  125.23    33.7  125.23    49.7  125.23
   72.44  124.91   79.55  124.98   82.77  124.56   90.24  124.57  103.91  123.34
  127.03   123.5  129.11  123.47  133.76  123.32  136.76  123.23  145.71 122.959
  148.66  122.77  148.71 122.876  149.57 122.972  156.16  123.71  162.88  125.83
  163.68  125.88  178.81   126.8
#Mann= 3 , 0 , 0
       0     .06       0  145.71     .04       0  149.57    .055       0
Bank Sta=145.71,149.57
XS Rating Curve= 0 ,0
Exp/Cntr=0.3,0.1

Type RM Length L Ch R = 1 ,2727.91 ,50.49,49.91,45.74
XS GIS Cut Line= 4
343167.2744750985422749.55352783343212.1629028325422682.28771973
343230.2714843755422659.01647949343253.1824951175422642.84570313
#Sta/Elev= 26
       0   125.5    9.68  125.01    14.2  124.41   20.11  124.42   30.93  123.45
   63.44  123.68   66.79  123.67   67.06  123.62   80.87  122.89   88.66  122.49
    91.7  122.33   92.15  122.21   92.37  122.21    92.5  122.34   92.85  122.56
  105.88  130.16  106.43  130.24  110.35   130.5  115.77  130.85  120.27  131.19
  124.02  132.56  125.88  133.13  127.31  133.65  128.69  133.97  131.93  134.07
   138.4  134.13
#Mann= 3 , 0 , 0
       0     .06       0   88.66     .04       0   92.85    .055       0
Bank Sta=88.66,92.85
XS Rating Curve= 0 ,0
Exp/Cntr=0.3,0.1

Type RM Length L Ch R = 1 ,2677.99 ,30.93,49.91,53.27
XS GIS Cut Line= 4
343195.7907104495422758.52947998343218.5405273445422743.58673096
343264.958312988 5422680.7545166343284.0593261725422641.36248779
#Sta/Elev= 22
       0  125.06    3.48  125.06   17.83  123.21   24.63  122.92   27.22  122.98
   60.66  122.79   62.28  122.39   63.84  121.89   65.87  121.13   66.84  121.33
   68.24 121.474   72.18  121.89   75.95  123.23   79.26  123.56   83.31  124.68
   92.31     130   95.37  131.71   98.98   132.5  103.06  132.74  128.29   133.4
   146.2  133.63  149.12  133.81
#Mann= 3 , 0 , 0
       0     .06       0   63.84     .04       0   68.24    .055       0
Bank Sta=63.84,68.24
XS Rating Curve= 0 ,0
Exp/Cntr=0.3,0.1

Type RM Length L Ch R = 1 ,2628.09 ,74.09,49.91,27.82
XS GIS Cut Line= 5
      343200.431     5422758.864      343221.187     5422761.703
      343233.375      5422742.44       343276.73     5422743.274
      343298.006     5422712.411
#Sta/Elev= 20
       0     125    2.92     124   20.95  123.03    29.1  123.16   32.69  122.52
   43.75  122.75   56.56  122.37   74.45  121.59   80.58  121.01   82.93  120.69
   83.43 120.998   84.78  121.56   94.47  122.46   95.27  122.64  104.14  123.93
  116.06   131.9  116.99  132.26  118.03  132.95  119.18  133.11  124.59  133.03
#Mann= 3 , 0 , 0
       0     .06       0   80.58     .04       0   83.43     .06       0
Bank Sta=80.58,83.43
XS Rating Curve= 0 ,0
Exp/Cntr=0.3,0.1

Type RM Length L Ch R = 1 ,2578.18 ,51.62,49.91,42.47
XS GIS Cut Line= 4
343300.1138916025422820.29492188343305.7077026375422784.74267578
343299.030090332 5422753.1427002343308.7435302735422723.11151123
#Sta/Elev= 30
       0  125.84   22.26  124.16   28.75  123.45   31.94  122.44   33.26  121.93
   35.99  121.83   36.42  121.83   45.68  121.15   46.13  120.95   47.37   120.4
   48.18  119.94   48.56  119.94   49.39  120.18   50.47 120.363   52.28  120.67
   55.26  120.97   63.36  121.05   68.29  121.03   69.88  121.06    72.6  121.87
   73.85  122.01   79.14  123.59   82.63  123.89   89.09  128.66   89.95  129.26
   93.31  131.55    94.8  132.47   96.06  132.59   97.34  132.59   99.85  132.64
#Mann= 3 , 0 , 0
       0     .06       0   47.37     .04       0   50.47     .06       0
Bank Sta=47.37,50.47
XS Rating Curve= 0 ,0
Exp/Cntr=0.3,0.1

Type RM Length L Ch R = 1 ,2528.27 ,10.94,10.08,9.19
XS GIS Cut Line= 4
343360.7821044925422798.12591553 343356.624877935422769.76672363
343334.6744995125422747.21173096343324.4912719735422718.76751709
#Sta/Elev= 22
       0   126.9   22.93  124.15   23.87  123.74   28.66  122.09   33.01  121.14
   33.27  121.04   36.36 119.532   37.04   119.1   37.82  119.32   39.38  119.57
   40.82  119.73   47.55  120.49   55.51  121.93   60.14  122.26   66.81  123.07
   69.32  124.07   75.21  128.28   80.33  131.89   82.78  132.12   85.26  132.14
   89.71  132.45   90.35  132.51
#Mann= 3 , 0 , 0
       0     .06       0   36.36     .04       0   39.38     .06       0
Bank Sta=36.36,39.38
XS Rating Curve= 0 ,0
Exp/Cntr=0.3,0.1

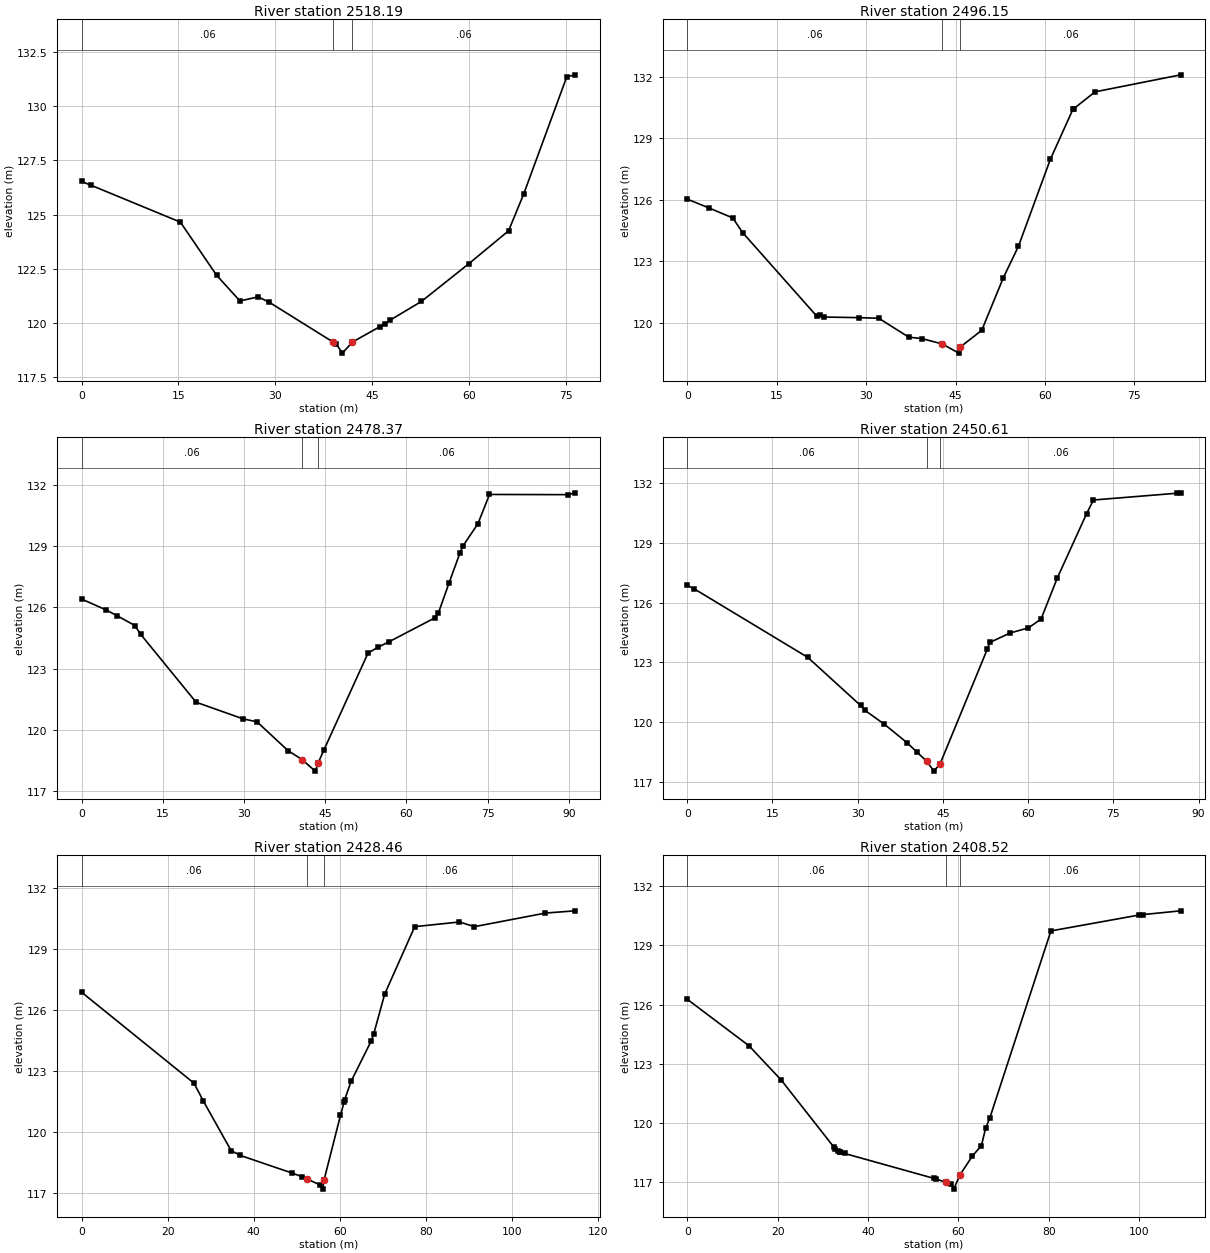
Type RM Length L Ch R = 1 ,2518.19 ,13.16,22.04,26.43
XS GIS Cut Line= 4
343372.1911010745422790.27990723343365.000915527 5422762.0916748
343346.7489013675422747.16851807343339.0054931645422724.64550781
#Sta/Elev= 20
       0  126.52    1.44  126.35   15.31  124.65   20.91  122.21   24.54  121.02
   27.35  121.21   29.09  120.96   38.97  119.13   39.43  119.05   40.42  118.62
   41.97  119.13   46.18  119.83   47.03  119.97   47.77  120.13   52.67     121
   60.03  122.74   66.17  124.25   68.51  125.94   75.19  131.34   76.48  131.43
#Mann= 3 , 0 , 0
       0     .06       0   38.97     .04       0   41.97     .06       0
Bank Sta=38.97,41.97
XS Rating Curve= 0 ,0
Exp/Cntr=0.3,0.1

Type RM Length L Ch R = 1 ,2496.15 ,11.19,17.78,21.52
XS GIS Cut Line= 4
343380.4874877935422782.81829834343372.8823242195422755.04449463
343373.7120971685422744.54309082 343359.884704595422703.36608887
#Sta/Elev= 22
       0  126.04    3.72   125.6    7.65  125.12    9.28  124.41   21.73  120.33
   22.28  120.37   22.96  120.29    28.8  120.26   32.13  120.23   37.14  119.31
   39.33  119.24   42.76  118.98   45.54  118.53    45.8  118.83   49.39  119.64
   52.99  122.19   55.55  123.74    60.9  127.98   64.72  130.44   64.83  130.45
    68.4  131.27   82.77   132.1
#Mann= 3 , 0 , 0
       0     .06       0   42.76     .04       0    45.8     .06       0
Bank Sta=42.76,45.8
XS Rating Curve= 0 ,0
Exp/Cntr=0.3,0.1

Type RM Length L Ch R = 1 ,2478.37 ,31.88,27.75,24.25
XS GIS Cut Line= 4
343387.2590942385422783.03112793343381.5856933595422753.71472168
343396.6262817385422731.35772705343383.856323242 5422699.4822998
#Sta/Elev= 25
       0  126.41    4.49  125.88    6.57  125.59    9.85  125.11   10.88  124.69
   21.14  121.35   29.86  120.53   32.39  120.39    38.1  118.98   40.69  118.54
   43.16  117.97   43.69  118.37   44.72  118.99    52.9  123.76   54.68  124.04
   56.81  124.32   65.19  125.48   65.91  125.74   67.85  127.19    69.9  128.69
   70.44  129.02   73.19   130.1   75.33  131.54   89.83  131.53   91.14  131.62
#Mann= 3 , 0 , 0
       0     .06       0   40.69     .04       0   43.69     .06       0
Bank Sta=40.69,43.69
XS Rating Curve= 0 ,0
Exp/Cntr=0.3,0.1

Type RM Length L Ch R = 1 ,2450.61 ,24.03,22.16,22.39
XS GIS Cut Line= 3
343410.1376953135422780.31707764343415.9451293955422742.04187012
343400.4584960945422696.44329834
#Sta/Elev= 21
       0  126.86    1.27  126.68   21.23  123.25   30.51  120.84   31.31  120.59
    34.7   119.9   38.71  118.97   40.41  118.51   42.15 118.043   43.43  117.55
   44.53  117.93   52.83  123.67   53.27     124    56.8  124.47   60.05  124.73
   62.28  125.17   65.14  127.23   70.29  130.45    71.5  131.14   86.19  131.48
   86.87   131.5
#Mann= 3 , 0 , 0
       0     .06       0   42.15     .04       0   44.53     .06       0
Bank Sta=42.15,44.53
XS Rating Curve= 0 ,0
Exp/Cntr=0.3,0.1

Type RM Length L Ch R = 1 ,2428.46 ,12.39,19.94,19.98
XS GIS Cut Line= 4
343427.7509155275422782.86132813 343439.704895025422747.98748779
343427.5335083015422698.53912354343437.6638793955422673.66210938
#Sta/Elev= 23
       0  126.89   26.11  122.41   28.31  121.52   34.73  119.09   36.87  118.85
   48.78  117.99   51.12  117.81   52.36  117.69   55.36   117.4   55.97  117.19
   56.31 117.624   60.14  120.82   60.99  121.48   61.11  121.59   62.61   122.5
   67.29  124.49   67.87  124.84   70.42   126.8   77.39  130.12   87.79  130.35
   91.27  130.12  107.77  130.79  114.65   130.9
#Mann= 3 , 0 , 0
       0     .06       0   52.36     .04       0   56.31     .06       0
Bank Sta=52.36,56.31
XS Rating Curve= 0 ,0
Exp/Cntr=0.3,0.1

Type RM Length L Ch R = 1 ,2408.52 ,14.15,29.97,35.14
XS GIS Cut Line= 5
343435.7180786135422780.73168945343445.950317383 5422747.4309082
343455.9058837895422730.43487549343444.8441162115422685.38909912
343444.1527099615422677.09832764
#Sta/Elev= 23
       0  126.27   13.66  123.91    20.8  122.17    32.4  118.78   32.73  118.66
   33.38  118.57   33.77  118.51   33.86  118.51   34.84  118.44   54.53  117.18
   55.11  117.14   57.35  116.97   58.36   116.9   58.99  116.63   60.36  117.35
   63.12  118.31   65.12  118.84   66.03  119.71      67  120.26    80.5  129.74
   100.1  130.55  100.92  130.57  109.24  130.76
#Mann= 3 , 0 , 0
       0     .06       0   57.35     .04       0   60.36     .06       0
Bank Sta=57.35,60.36
XS Rating Curve= 0 ,0
Exp/Cntr=0.3,0.1

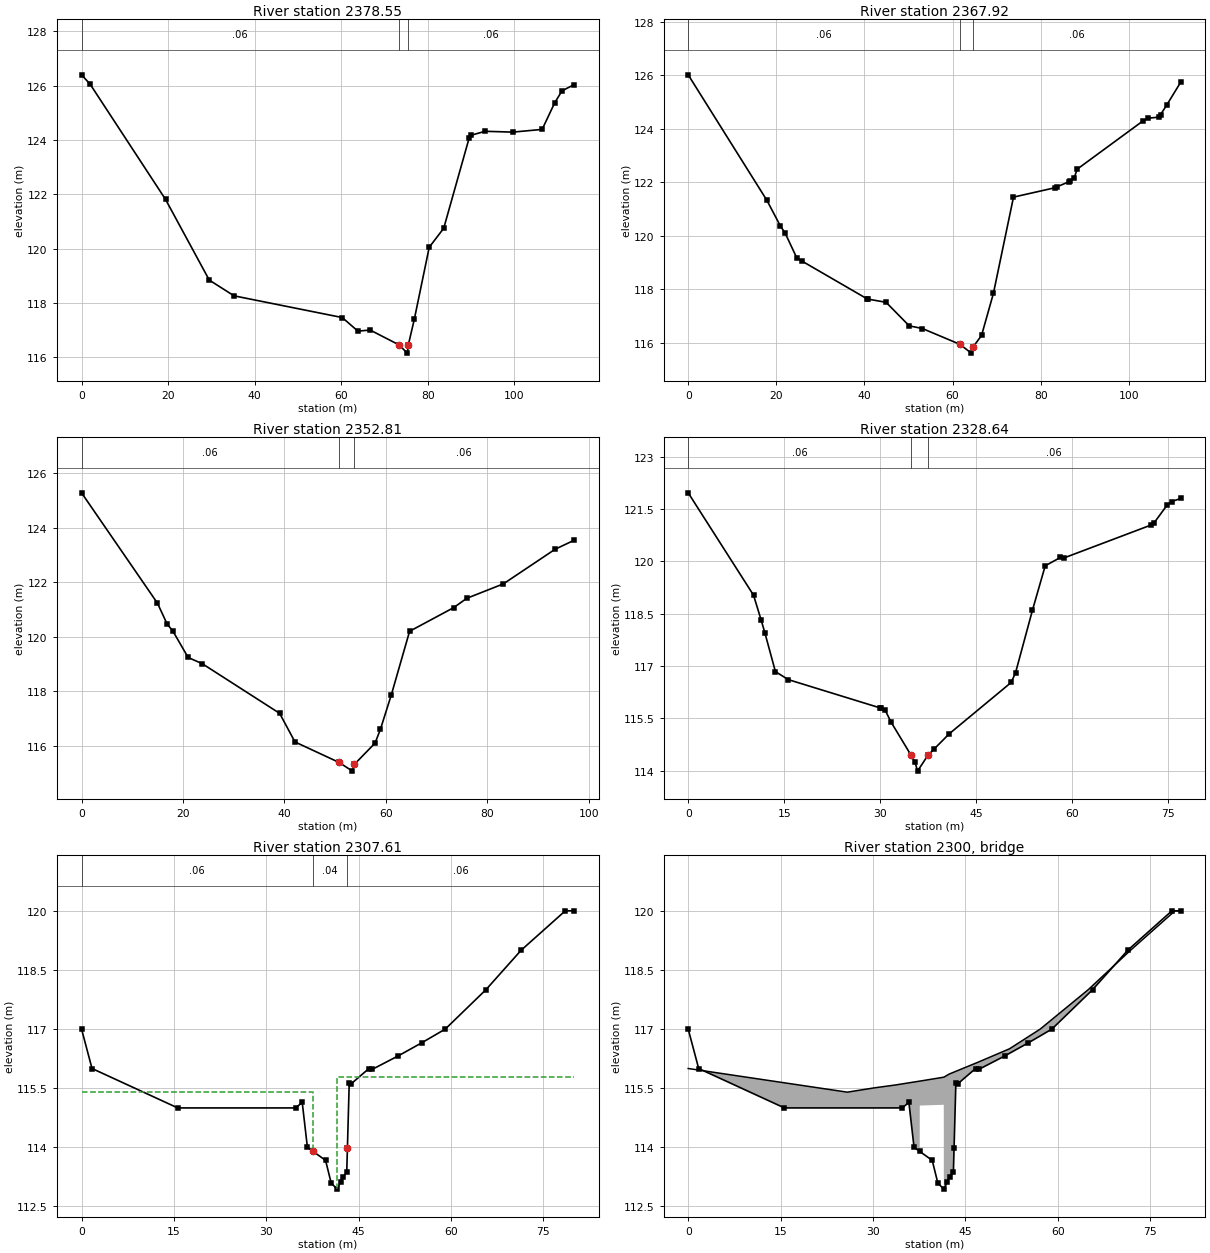
Type RM Length L Ch R = 1 ,2378.55 ,12.02,10.64,11.18
XS GIS Cut Line= 4
343442.339294434 5422782.8861084343453.0733032235422748.05151367
343501.4827270515422714.32147217343507.7213134775422697.05688477
#Sta/Elev= 22
       0   126.4    1.96  126.06   19.41  121.81   29.51  118.84   35.24  118.26
   60.24  117.46   63.85  116.96   66.68     117   73.28  116.46   75.28  116.15
   75.52 116.464    76.9  117.41   80.33  120.05   83.68  120.75   89.53  124.06
   89.88  124.17   93.24  124.32   99.65  124.29  106.42  124.39  109.32  125.37
  111.01  125.81  113.81  126.04
#Mann= 3 , 0 , 0
       0     .06       0   73.28     .04       0   75.52     .06       0
Bank Sta=73.28,75.52
XS Rating Curve= 0 ,0
Exp/Cntr=0.3,0.1

Type RM Length L Ch R = 1 ,2367.92 ,11.31,15.11,15.78
XS GIS Cut Line= 5
343446.8123168955422784.07751465343460.777709961 5422762.2454834
343478.7532958985422741.79528809   343505.578125 5422727.0100708
343515.3955078135422700.75628662
#Sta/Elev= 29
       0  126.01   17.86  121.32   20.93  120.36   22.02  120.09   24.64  119.17
   25.92  119.04   40.59  117.64   40.72  117.63   44.91  117.51   50.16  116.63
   53.14  116.53   61.66  115.94   64.25  115.61   64.66  115.84   66.58  116.27
   69.27  117.84   73.83  121.44   83.24  121.79   83.77  121.83    86.5  122.02
   86.55  122.03   87.58  122.16   88.33  122.49  103.32   124.3  104.43  124.39
  106.94  124.43   107.2  124.52  108.68   124.9   111.8  125.74
#Mann= 3 , 0 , 0
       0     .06       0   61.66     .04       0   64.66     .06       0
Bank Sta=61.66,64.66
XS Rating Curve= 0 ,0
Exp/Cntr=0.3,0.1

Type RM Length L Ch R = 1 ,2352.81 ,31.17,24.17,17.57
XS GIS Cut Line= 6
343453.8640747075422786.42651367343474.466674805 5422762.9362793
 343482.624877935422754.50750732343502.5360717775422747.46051025
343504.6102905275422743.45330811343516.6400756845422717.61407471
#Sta/Elev= 20
       0  125.28   14.97  121.23   16.86  120.47   18.03   120.2   21.01  119.24
   23.81  119.01   39.05  117.19   42.08  116.14   50.76  115.39   53.41  115.07
   53.79  115.32   57.87   116.1   58.93  116.61   61.09  117.88   64.67   120.2
   73.38  121.07   75.94  121.41   83.16  121.94   93.36  123.21   97.11  123.54
#Mann= 3 , 0 , 0
       0     .06       0   50.76     .04       0   53.79     .06       0
Bank Sta=50.76,53.79
XS Rating Curve= 0 ,0
Exp/Cntr=0.3,0.1

Type RM Length L Ch R = 1 ,2328.64 ,27.02,21.04,20.02
Node Photo=..\..\..\..\Corner Brook\Windshield Survey\CB photos\P1000725.JPG
XS GIS Cut Line= 3
343477.4550781255422795.50372314343492.2993164065422790.56732178
343520.741088867 5422736.2902832
#Sta/Elev= 27
       0  121.96    10.2  119.03   11.37  118.33   11.96  117.96   13.62  116.84
   15.64  116.61   29.98   115.8   30.07  115.79   30.72  115.75   31.66   115.4
   34.77 114.455   35.41  114.26   35.81  113.99   37.42  114.44   38.44  114.63
   40.77  115.06   50.44  116.53   51.12  116.81   53.76   118.6   55.75  119.87
   58.13  120.11   58.75   120.1   72.31  121.04   72.79  121.11   74.83  121.62
    75.5  121.71   76.92   121.8
#Mann= 3 , 0 , 0
       0     .06       0   34.77     .04       0   37.42     .06       0
Bank Sta=34.77,37.42
XS Rating Curve= 0 ,0
Exp/Cntr=0.3,0.1

Type RM Length L Ch R = 1 ,2307.61 ,11.95,11.77,11.75
XS GIS Cut Line= 2
343515.0319213875422822.16131592343525.157897949 5422742.8046875
#Sta/Elev= 25
       0     117     1.7     116   15.62     115   34.77     115   35.84  115.14
   36.68     114    37.6 113.897   39.63  113.67   40.55  113.09   41.53  112.94
   42.07  113.12   42.44  113.25   43.07  113.37   43.18 113.989   43.47  115.62
   43.77  115.61   46.68     116   47.23  115.98   51.43  116.32   55.23  116.65
   59.07     117   65.68     118   71.39     119   78.56     120      80     120
#Mann= 3 , 0 , 0
       0     .06       0    37.6     .04       0   43.18     .06       0
#XS Ineff= 2 , 0
       0    37.6   115.4   41.52       0  115.78
Permanent Ineff=
       F       F
Bank Sta=37.6,43.18
XS Rating Curve= 0 ,0
Exp/Cntr=0.5,0.3

Type RM Length L Ch R = 3 ,2300    ,,,
Node Photo=..\..\..\..\Corner Brook\Windshield Survey\CB photos\P1000720.JPG
BEGIN DESCRIPTION:
Walbournes Road (Structure #2121B)
END DESCRIPTION:
Bridge Culvert--1,0,-1,-1, 0
Deck Dist Width WeirC Skew NumUp NumDn MinLoCord MaxHiCord MaxSubmerge Is_Ogee
3.7,6.5,1.67,0, 16, 15, 115.4, , 0.98, 0, 0,0,,
       0   25.84   30.27   33.56    37.6   37.61   41.51   41.52    42.4   47.08
   52.18   57.17   64.97   71.84   79.06      80
     116   115.4  115.51  115.58  115.68  115.68  115.78  115.78  115.86  116.16
   116.5     117     118     119     120     120
                                     111  115.06  115.08     111
                                                
       0    26.2    30.6   37.53   38.31   38.32   42.42   42.43    42.5   46.64
   50.32   57.84   65.47   72.92      80
     116  115.34  115.42  115.63  115.64  115.64  115.79  115.79   115.8  115.98
  116.23     117     118     119     120
                                     111  114.97  114.93     111
                                        
BR Coef=-1 , 0 , 0 ,, 0 ,,,0.8,-1,,0,
WSPro=,,,, 1 ,,,, 0 ,,,, 0 ,,,,-1 ,-1 ,-1 , 0 , 0 , 0 , 0 , 0
BC Design=,, 0 ,, 0 ,,,,,,
BC Use User HTab Curves=0
BC User HTab FreeFlow(D)= 0

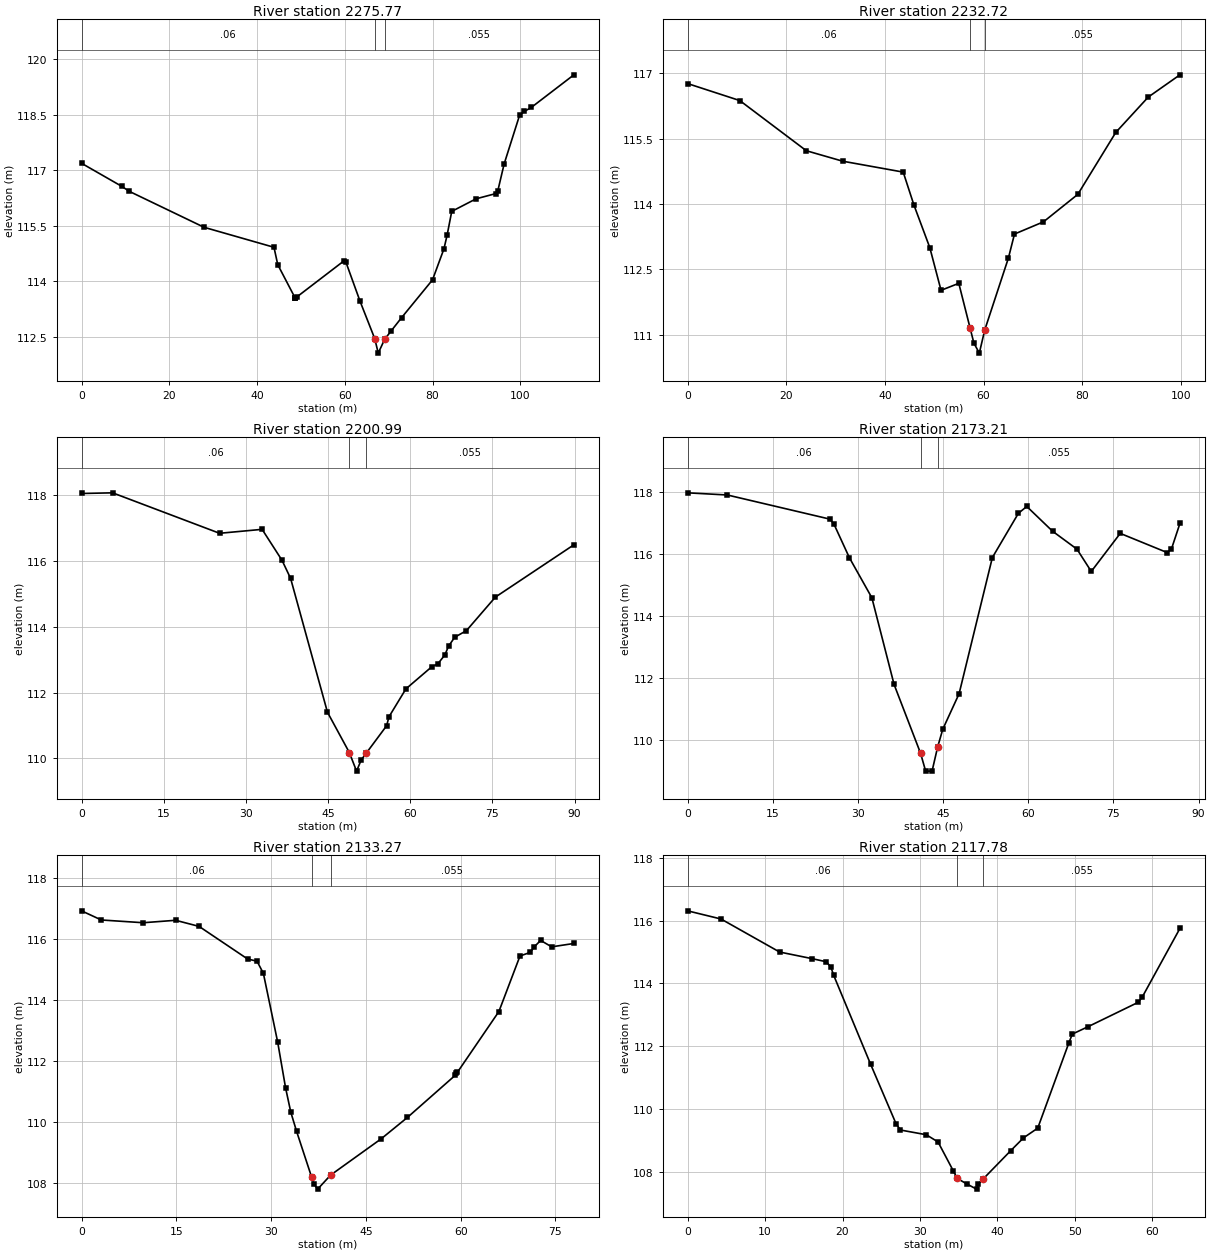
Type RM Length L Ch R = 1 ,2275.77 ,39.4,43.04,52.78
XS GIS Cut Line= 2
343530.2150878915422857.03369141343563.4030761725422749.83911133
#Sta/Elev= 30
       0  117.19    9.12  116.57   10.91  116.43   27.93  115.46   43.86  114.92
   44.72  114.45   48.68  113.55   48.69  113.55    48.7  113.55   49.09  113.58
   59.78  114.55   60.28  114.51   63.48  113.46   66.83 112.449   67.62  112.06
   69.08 112.433   70.63  112.67   72.95  113.02   79.99  114.04    82.6  114.88
   83.32  115.25   84.37  115.89   89.92  116.23   94.39  116.37   94.84  116.43
   96.31  117.17   99.84  118.49   100.9  118.59  102.52   118.7  112.21  119.58
#Mann= 3 , 0 , 0
       0     .06       0   66.83     .04       0   69.08    .055       0
Bank Sta=66.83,69.08
XS Rating Curve= 0 ,0
Exp/Cntr=0.3,0.1

Type RM Length L Ch R = 1 ,2232.72 ,38.44,31.74,21.2
XS GIS Cut Line= 3
343545.7821044925422849.65148926343597.9434814455422799.78308105
343605.2807006845422773.11547852
#Sta/Elev= 20
       0  116.76   10.59  116.37   24.08  115.22   31.45  114.98   43.72  114.73
   45.91  113.97   49.11     113   51.39  112.02   54.99  112.18    57.3 111.146
   58.05  110.81   59.15  110.58   60.25  111.11   65.05  112.76   66.28  113.31
   72.16  113.59   79.12  114.22   86.82  115.64    93.4  116.45   99.82  116.96
#Mann= 3 , 0 , 0
       0     .06       0    57.3     .04       0   60.25    .055       0
Bank Sta=57.3,60.25
XS Rating Curve= 0 ,0
Exp/Cntr=0.3,0.1

Type RM Length L Ch R = 1 ,2200.99 ,22.72,27.78,32.31
XS GIS Cut Line= 6
343627.4519042975422859.60089111343621.3679199225422839.97967529
343618.6024780275422835.55810547 343620.261718755422824.91827393
343608.5084838875422800.18450928343620.3999023445422777.10888672
#Sta/Elev= 22
       0  118.05    5.67  118.07    25.2  116.84   32.96  116.96   36.59  116.02
   38.16  115.47   44.89   111.4   48.88 110.176    50.2  109.61   51.05  109.95
   51.98 110.158   55.69  110.99   56.11  111.26   59.21  112.11   63.91  112.78
   65.03  112.87   66.31  113.14      67  113.41   68.12  113.68   70.25  113.88
   75.54   114.9   89.87  116.49
#Mann= 3 , 0 , 0
       0     .06       0   48.88     .04       0   51.98    .055       0
Bank Sta=48.88,51.98
XS Rating Curve= 0 ,0
Exp/Cntr=0.3,0.1

Type RM Length L Ch R = 1 ,2173.21 ,42.81,39.94,36.09
XS GIS Cut Line= 3
343629.7476806645422860.61590576343633.5178833015422832.35351563
343659.5560913095422780.30328369
#Sta/Elev= 23
       0  117.97    7.01   117.9   25.08  117.12   25.78  116.96   28.51  115.87
   32.46  114.58   36.37  111.78   41.03  109.56   41.93  108.98   43.06  108.98
   44.03  109.75   44.94  110.33   47.82  111.48   53.68  115.88   58.27  117.31
   59.74  117.53   64.28  116.73   68.58  116.15    71.1  115.43    76.2  116.66
   84.47  116.04   85.21  116.15   86.71  116.98
#Mann= 3 , 0 , 0
       0     .06       0   41.03     .04       0   44.03    .055       0
Bank Sta=41.03,44.03
XS Rating Curve= 0 ,0
Exp/Cntr=0.3,0.1

Type RM Length L Ch R = 1 ,2133.27 ,16.07,15.48,14.82
XS GIS Cut Line= 3
343662.3342895515422857.67529297343680.6378784185422838.80108643
343664.5114746095422789.75189209
#Sta/Elev= 28
       0  116.91    3.13  116.61    9.77  116.52   14.89   116.6    18.6   116.4
   26.29  115.33   27.77  115.26   28.78  114.86   31.04  112.61    32.3   111.1
   33.12  110.31   34.04  109.68   36.42  108.18   36.77  107.96   37.37  107.79
   39.42  108.25   47.43  109.44   51.58  110.14   59.14  111.52   59.32   111.6
   59.49  111.62   66.05  113.61   69.39  115.43   71.03  115.55   71.64  115.73
   72.66  115.94    74.4  115.73   77.92  115.84
#Mann= 3 , 0 , 0
       0     .06       0   36.42     .04       0   39.42    .055       0
Bank Sta=36.42,39.42
XS Rating Curve= 0 ,0
Exp/Cntr=0.3,0.1

Type RM Length L Ch R = 1 ,2117.78 ,8.25,14.77,20.57
XS GIS Cut Line= 5
343676.9987182625422849.66088867343689.0283203135422839.02111816
343692.9000854495422824.78887939343686.9542846685422813.73468018
343687.7838745125422793.56072998
#Sta/Elev= 27
       0  116.31    4.32  116.05   11.88     115   16.06  114.79   17.91  114.69
    18.5  114.52   18.86  114.26   23.63  111.43   26.91  109.54   27.47  109.34
   30.81  109.19   32.33  108.96   34.28  108.05   34.81   107.8   36.08  107.62
    37.3  107.46   37.55  107.63   38.17 107.787    41.7  108.68   43.36  109.09
    45.2   109.4   49.23  112.12   49.66  112.39   51.73  112.63   58.16   113.4
   58.67  113.56   63.55  115.75
#Mann= 3 , 0 , 0
       0     .06       0   34.81     .04       0   38.17    .055       0
Bank Sta=34.81,38.17
XS Rating Curve= 0 ,0
Exp/Cntr=0.3,0.1