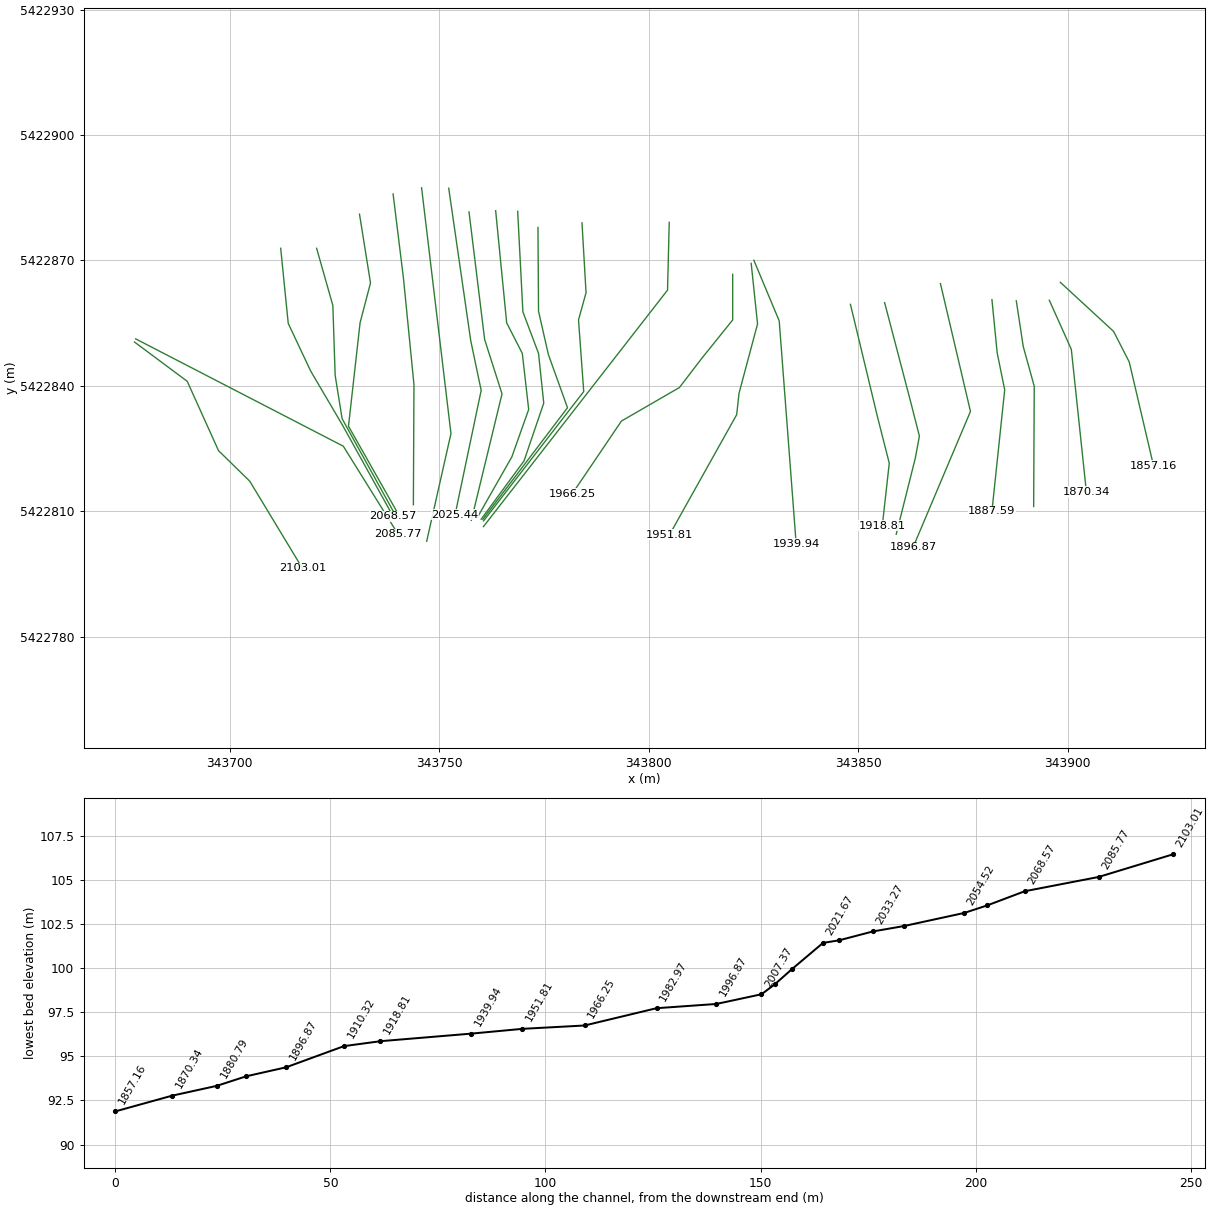
HEC-RAS study Corner_Brook2.prj: Corner_Brook2

--- Corner_Brook2.g02 (geometry) --- (continued)

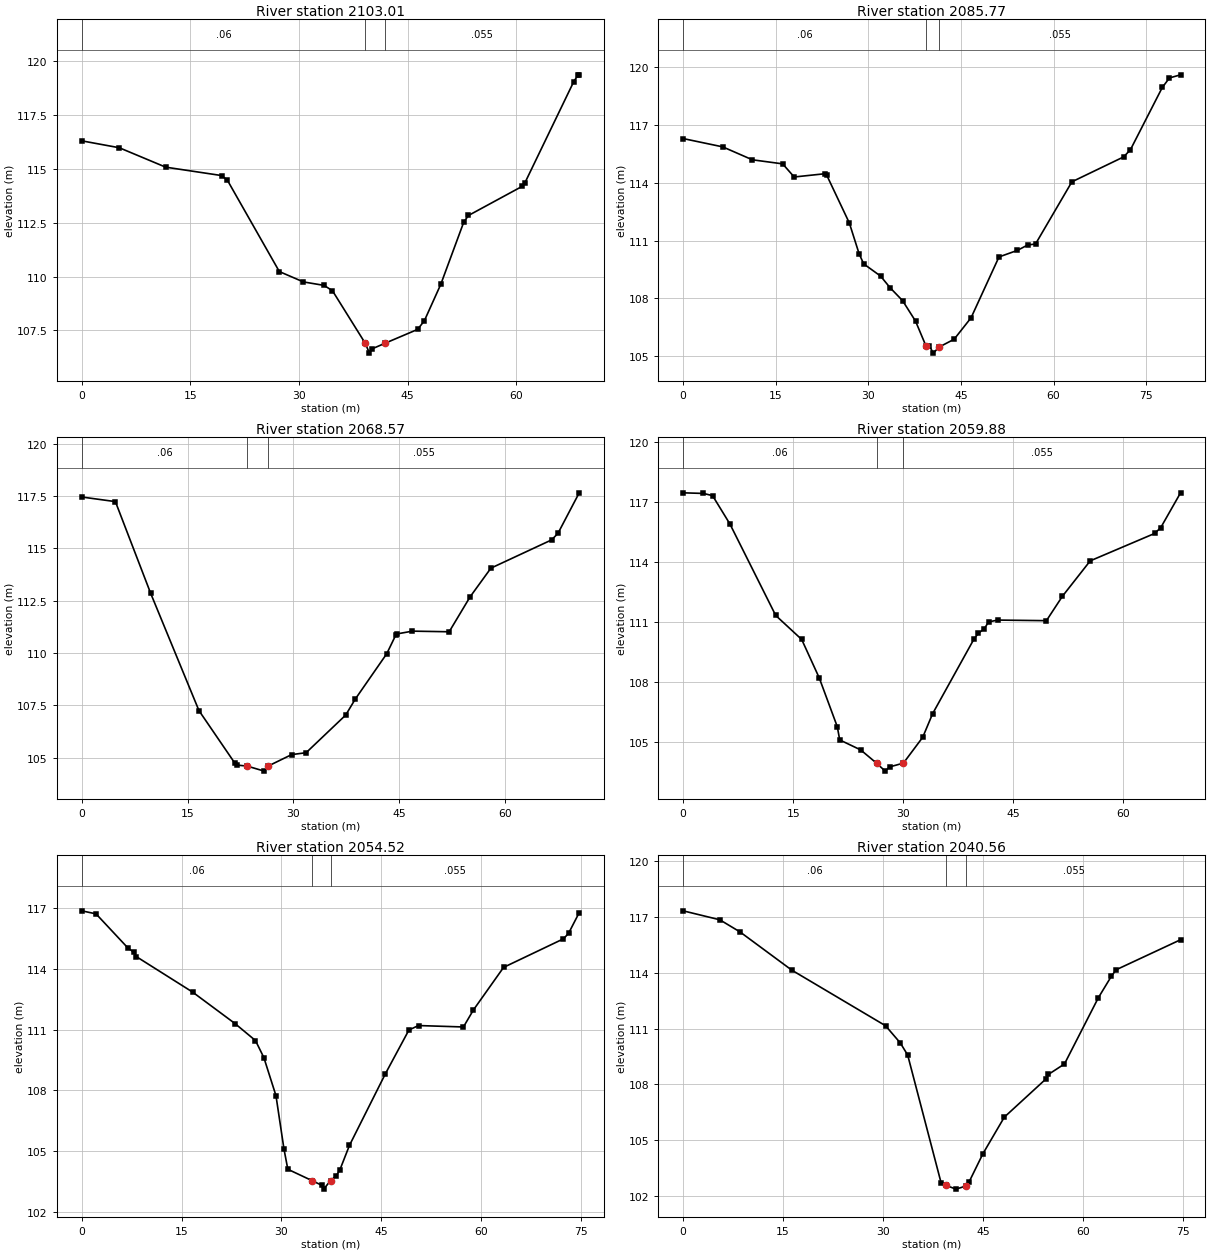
Type RM Length L Ch R = 1 ,2103.01 ,16.08,17.24,19.84
XS GIS Cut Line= 5
343677.275085449 5422850.4899292343689.8580932625422841.09387207
343697.3247070315422824.51251221343704.7915039065422817.18908691
343717.3743286135422796.32427979
#Sta/Elev= 23
       0  116.29    5.18  115.97   11.59  115.07   19.33  114.68   20.12  114.46
   27.29  110.23   30.62  109.75   33.47  109.59   34.63  109.34   39.13  106.92
   39.74  106.45   40.04  106.64   41.87 106.905   46.39  107.55   47.32  107.95
   49.59  109.64   52.76  112.52   53.41  112.83   60.83  114.18   61.19  114.33
   67.95  119.03   68.55  119.34   68.71  119.35
#Mann= 3 , 0 , 0
       0     .06       0   39.13     .04       0   41.87    .055       0
Bank Sta=39.13,41.87
XS Rating Curve= 0 ,0
Exp/Cntr=0.3,0.1

Type RM Length L Ch R = 1 ,2085.77 ,20.31,17.19,10.69
XS GIS Cut Line= 3
343677.549072266 5422851.2479248 343727.107482915422825.57110596
343740.1682739265422804.53967285
#Sta/Elev= 30
       0  116.28    6.41  115.85   11.22  115.18   16.12  114.97   17.99  114.29
      23  114.46   23.25  114.39   26.92  111.91   28.51  110.31   29.25  109.79
   31.98  109.16   33.54  108.55   35.54  107.89   37.64  106.83   39.31  105.56
    39.9  105.55    40.5  105.17    41.5  105.49    43.9  105.89   46.64     107
   51.16  110.15   54.14  110.49   55.82  110.77   57.08  110.82   62.97  114.04
   71.35  115.33   72.45   115.7   77.62  118.93   78.78  119.42   80.57  119.58
#Mann= 3 , 0 , 0
       0     .06       0   39.31     .04       0    41.5    .055       0
Bank Sta=39.31,41.5
XS Rating Curve= 0 ,0
Exp/Cntr=0.3,0.1

Type RM Length L Ch R = 1 ,2068.57 ,10.71,8.69,4.44
XS GIS Cut Line= 5
343712.1630859385422872.91271973343713.9606933595422854.94952393
343719.353271484  5422843.480896343726.8198852545422830.76849365
343738.9880981455422808.79827881
#Sta/Elev= 23
       0  117.46    4.77  117.24    9.77  112.86   16.63  107.25   21.72  104.74
   21.98  104.65   23.48   104.6   25.89  104.36   26.49  104.61   29.78  105.15
   31.83  105.24   37.45  107.04    38.8   107.8   43.27  109.97   44.55  110.86
   44.76  110.92   46.92  111.05   52.13  111.02    55.1  112.69   58.05  114.06
   66.66  115.41   67.56  115.72   70.58  117.66
#Mann= 3 , 0 , 0
       0     .06       0   23.48     .04       0   26.49    .055       0
Bank Sta=23.48,26.49
XS Rating Curve= 0 ,0
Exp/Cntr=0.3,0.1

Type RM Length L Ch R = 1 ,2059.88 ,5.98,5.37,4.2
XS GIS Cut Line= 5
343720.7360839845422872.91271973343724.6077270515422859.23309326
343725.1607055665422842.51348877343726.8198852545422832.15032959
 343739.541076665422809.07452393
#Sta/Elev= 27
       0  117.47    2.76  117.44    4.01  117.33    6.38  115.91   12.62  111.34
   16.16  110.14   18.55  108.22   21.01  105.78   21.34  105.12    24.2  104.62
   26.36 103.957   27.54  103.56   28.13  103.77   30.02  103.96   32.65  105.25
      34  106.43   39.65  110.17   40.24  110.45   41.05  110.68   41.63  111.02
   42.89  111.11   49.51  111.08   51.69   112.3   55.48  114.07   64.26  115.44
   65.09  115.73   67.79  117.47
#Mann= 3 , 0 , 0
       0     .06       0   26.36     .04       0   30.02    .055       0
Bank Sta=26.36,30.02
XS Rating Curve= 0 ,0
Exp/Cntr=0.3,0.1

Type RM Length L Ch R = 1 ,2054.52 ,12.81,13.96,14.46
XS GIS Cut Line= 5
343730.9680786135422881.06512451343733.5952758795422864.62188721
343731.1065063485422855.08770752343728.3408813485422830.35388184
343739.8176879885422810.04187012
#Sta/Elev= 28
       0  116.86    2.14  116.71    6.95  115.02    7.82  114.82     8.2   114.6
   16.65  112.85   23.01   111.3   26.09  110.46   27.35  109.62   29.17  107.74
   30.37  105.11   30.95  104.11   34.59 103.549   36.05  103.32   36.34  103.13
   37.37 103.554   38.22  103.78   38.78  104.09   40.21  105.29   45.62  108.83
   49.14  110.98   50.58   111.2   57.33  111.13   58.83  111.97   63.36  114.07
   72.36  115.48   73.12  115.75   74.72  116.77
#Mann= 3 , 0 , 0
       0     .06       0   34.59     .04       0   37.37    .055       0
Bank Sta=34.59,37.37
XS Rating Curve= 0 ,0
Exp/Cntr=0.3,0.1

Type RM Length L Ch R = 1 ,2040.56 ,7.27,7.29,7.43
XS GIS Cut Line= 4
343738.9880981455422885.90148926343741.4769287115422865.58929443
343743.9658813485422840.30267334343743.8275146485422811.56188965
#Sta/Elev= 21
       0  117.31     5.5  116.83    8.53  116.18    16.3  114.13   30.36  111.15
   32.57  110.23   33.68  109.58    38.7  102.72   39.47  102.59    40.9  102.39
   42.48  102.56   42.87  102.76   44.97  104.29   48.18  106.25   54.46  108.31
   54.79  108.54    57.2   109.1   62.28  112.65   64.23   113.8   64.95  114.15
   74.61  115.76
#Mann= 3 , 0 , 0
       0     .06       0   39.47     .04       0   42.48    .055       0
Bank Sta=39.47,42.48
XS Rating Curve= 0 ,0
Exp/Cntr=0.3,0.1

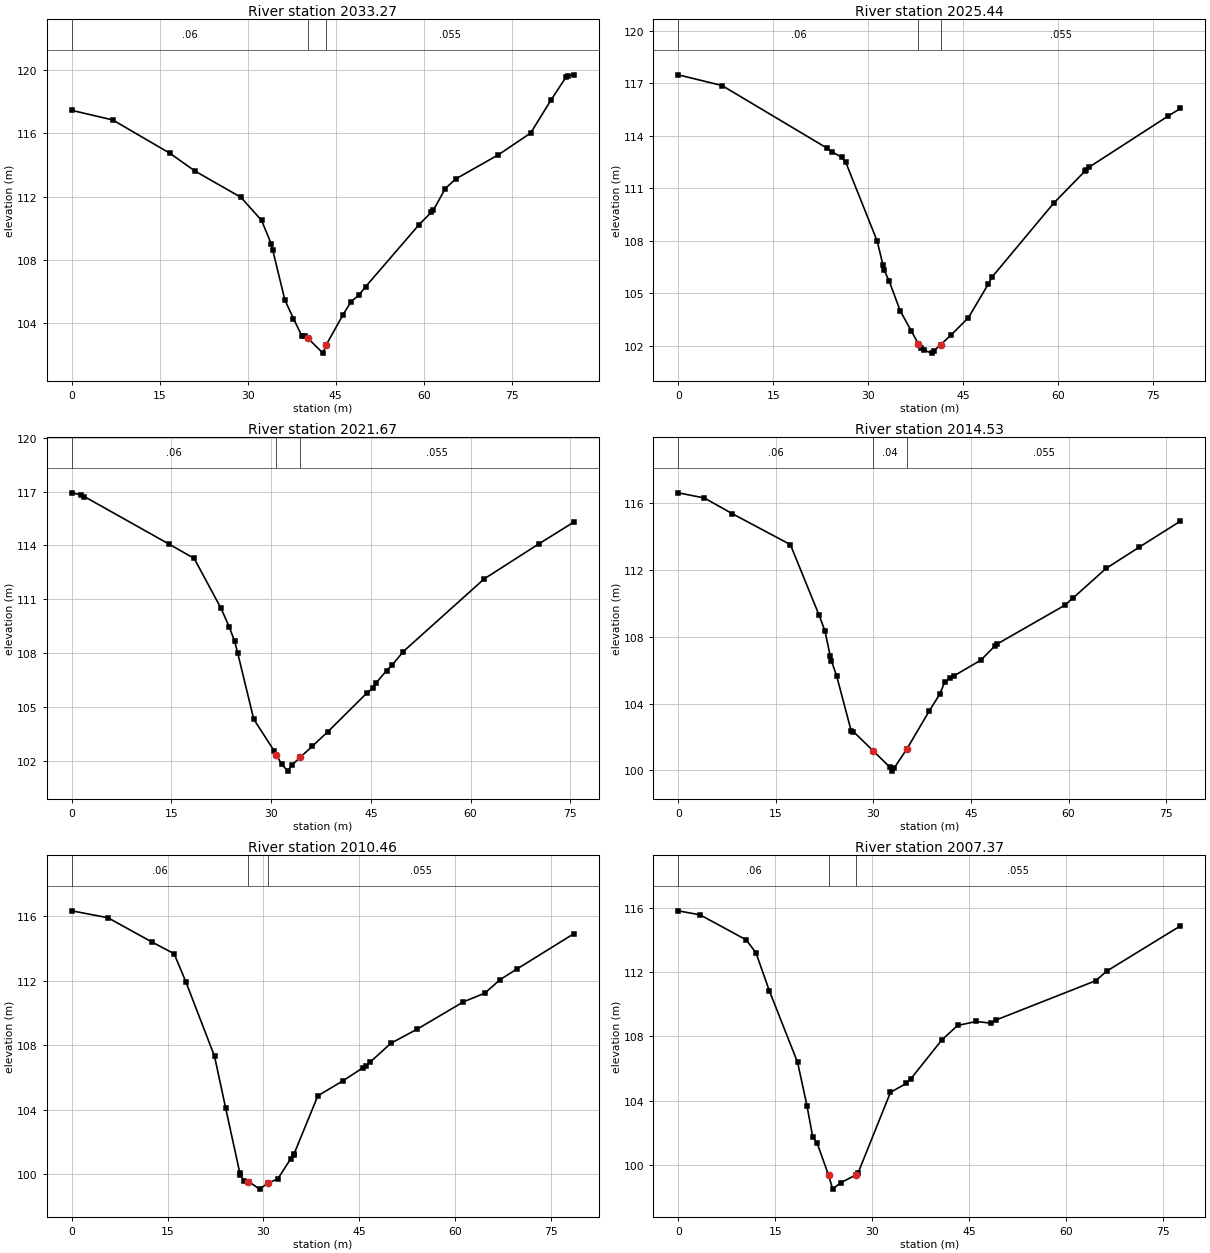
Type RM Length L Ch R = 1 ,2033.27 ,7.45,7.82,8.18
XS GIS Cut Line= 3
343745.7858886725422887.38110352343752.7958984385422828.58770752
343747.0051269535422802.84667969
#Sta/Elev= 30
       0  117.46    6.99  116.85   16.69  114.75   21.02  113.61   28.84  111.95
   32.35  110.49   33.98  109.02   34.27  108.59   36.33  105.44   37.79  104.27
   39.22  103.17    39.7  103.19   40.29  103.01   42.82  102.08   43.33  102.57
   46.26  104.52   47.59  105.33      49  105.78   50.12   106.3   59.21  110.22
   61.31  111.01   61.66  111.15   63.67   112.5   65.43  113.11   72.71  114.64
   78.22  116.02   81.66  118.09   84.31   119.6   84.51  119.66   85.59  119.71
#Mann= 3 , 0 , 0
       0     .06       0   40.29     .04       0   43.33    .055       0
Bank Sta=40.29,43.33
XS Rating Curve= 0 ,0
Exp/Cntr=0.3,0.1

Type RM Length L Ch R = 1 ,2025.44 ,3.43,3.77,4.29
XS GIS Cut Line= 4
343752.2620849615422887.28308105343757.5164794925422850.80432129
343760.0054931645422838.92108154343753.7830810555422809.21270752
#Sta/Elev= 28
       0  117.47    6.91  116.86   23.44   113.3    24.3  113.08   25.81  112.76
   26.46  112.49   31.45  107.97   32.35  106.61   32.52  106.34   33.36  105.67
   35.09  103.99   36.86  102.83   37.96 102.102   38.31  101.87   38.78  101.75
    40.1  101.58   40.47  101.73   41.47 102.063   43.11  102.61   45.87  103.61
      49  105.52   49.61  105.93   59.33  110.14    64.3  111.98   64.37  112.01
   64.94   112.2   77.36   115.1   79.35  115.55
#Mann= 3 , 0 , 0
       0     .06       0   37.96     .04       0   41.47    .055       0
Bank Sta=37.96,41.47
XS Rating Curve= 0 ,0
Exp/Cntr=0.3,0.1

Type RM Length L Ch R = 1 ,2021.67 ,6.52,7.14,7.19
XS GIS Cut Line= 4
 343757.101684575422881.61791992343760.8350830085422851.08068848
343764.9832763675422838.09191895343757.6549072275422807.83087158
#Sta/Elev= 27
       0  116.93    1.45  116.81     1.9  116.72   14.65  114.07   18.41  113.28
   22.41  110.53   23.71  109.45   24.51  108.65   24.95  108.03   27.38  104.32
   30.43  102.57   30.76  102.35   31.57  101.82   32.51  101.43   33.09  101.76
   34.36 102.194   36.19  102.82   38.55  103.63    44.4  105.78   45.39  106.07
    45.8  106.35   47.37  107.03   48.24  107.35   49.88  108.09   62.06  112.14
   70.33   114.1   75.54   115.3
#Mann= 3 , 0 , 0
       0     .06       0   30.76     .04       0   34.36    .055       0
Bank Sta=30.76,34.36
XS Rating Curve= 0 ,0
Exp/Cntr=0.3,0.1

Type RM Length L Ch R = 1 ,2014.53 ,4.45,4.08,4.12
XS GIS Cut Line= 6
343763.4622802735422881.89428711343766.0894775395422855.08770752
343769.8228759775422847.76428223 343771.343872075422834.36108398
 343767.333923345422823.03051758 343759.175903325422808.66009521
#Sta/Elev= 29
       0  116.62    4.02  116.31    8.27  115.38   17.24  113.52   21.64  109.31
   22.56  108.35   23.38  106.83   23.56  106.55   24.36  105.65   26.58  102.38
   26.94  102.32   30.01  101.16   32.53   100.2   32.94   99.96   33.21  100.15
   35.16  101.29   38.57  103.55    40.2  104.56   40.98  105.31   41.82  105.51
   42.46  105.68   46.55  106.61   48.64  107.44   48.94  107.55   59.43  109.89
   60.66  110.31   65.76  112.09   70.88  113.37   77.19  114.92
#Mann= 3 , 0 , 0
       0     .06       0   30.01     .04       0   35.16    .055       0
Bank Sta=30.01,35.16
XS Rating Curve= 0 ,0
Exp/Cntr=0.3,0.1

Type RM Length L Ch R = 1 ,2010.46 ,3.56,3.08,2.32
XS GIS Cut Line= 6
343768.7166748055422881.75610352343769.9611206055422857.71307373
343773.6945190435422847.76428223343774.9389038095422835.88110352
343770.2376708985422822.06329346343760.005493164 5422808.1072998
#Sta/Elev= 30
       0  116.34    5.67  115.91   12.57   114.4   16.02  113.68   17.86  111.93
   22.34  107.32   24.08  104.11   26.31  100.06   26.37   99.93      27    99.6
   27.63   99.55   27.73   99.54   29.38   99.08   30.65   99.44   32.25   99.72
   34.26  100.96    34.7  101.21   34.76  101.24   38.51  104.87   42.49  105.81
    45.5  106.59   46.09  106.72   46.65  106.94   49.92  108.12   54.09  109.01
   61.27  110.69   64.66  111.24   67.02  112.07   69.74  112.75   78.57  114.92
#Mann= 3 , 0 , 0
       0     .06       0   27.63     .04       0   30.65    .055       0
Bank Sta=27.63,30.65
XS Rating Curve= 0 ,0
Exp/Cntr=0.3,0.1

Type RM Length L Ch R = 1 ,2007.37 ,11.96,10.5,8.32
XS GIS Cut Line= 5
343773.5562744145422877.88708496343773.6945190435422857.85131836
 343776.045104985422847.48791504343780.608093262 5422834.7756958
343760.420288086 5422808.1072998
#Sta/Elev= 25
       0   115.8    3.38  115.55    10.5     114   12.01   113.2   14.09  110.83
   18.45  106.39   19.91  103.69   20.79  101.76   21.49  101.36   23.25  99.372
   23.87   98.52   25.15   98.93   27.44   99.39    27.8   99.52   32.81  104.53
   35.24  105.08   35.96  105.37   40.77  107.79   43.18  108.68   46.07  108.93
   48.41  108.82   49.06  109.01   64.54  111.46   66.26  112.06   77.62  114.86
#Mann= 3 , 0 , 0
       0     .06       0   23.25     .04       0   27.44    .055       0
Bank Sta=23.25,27.44
XS Rating Curve= 0 ,0
Exp/Cntr=0.3,0.1

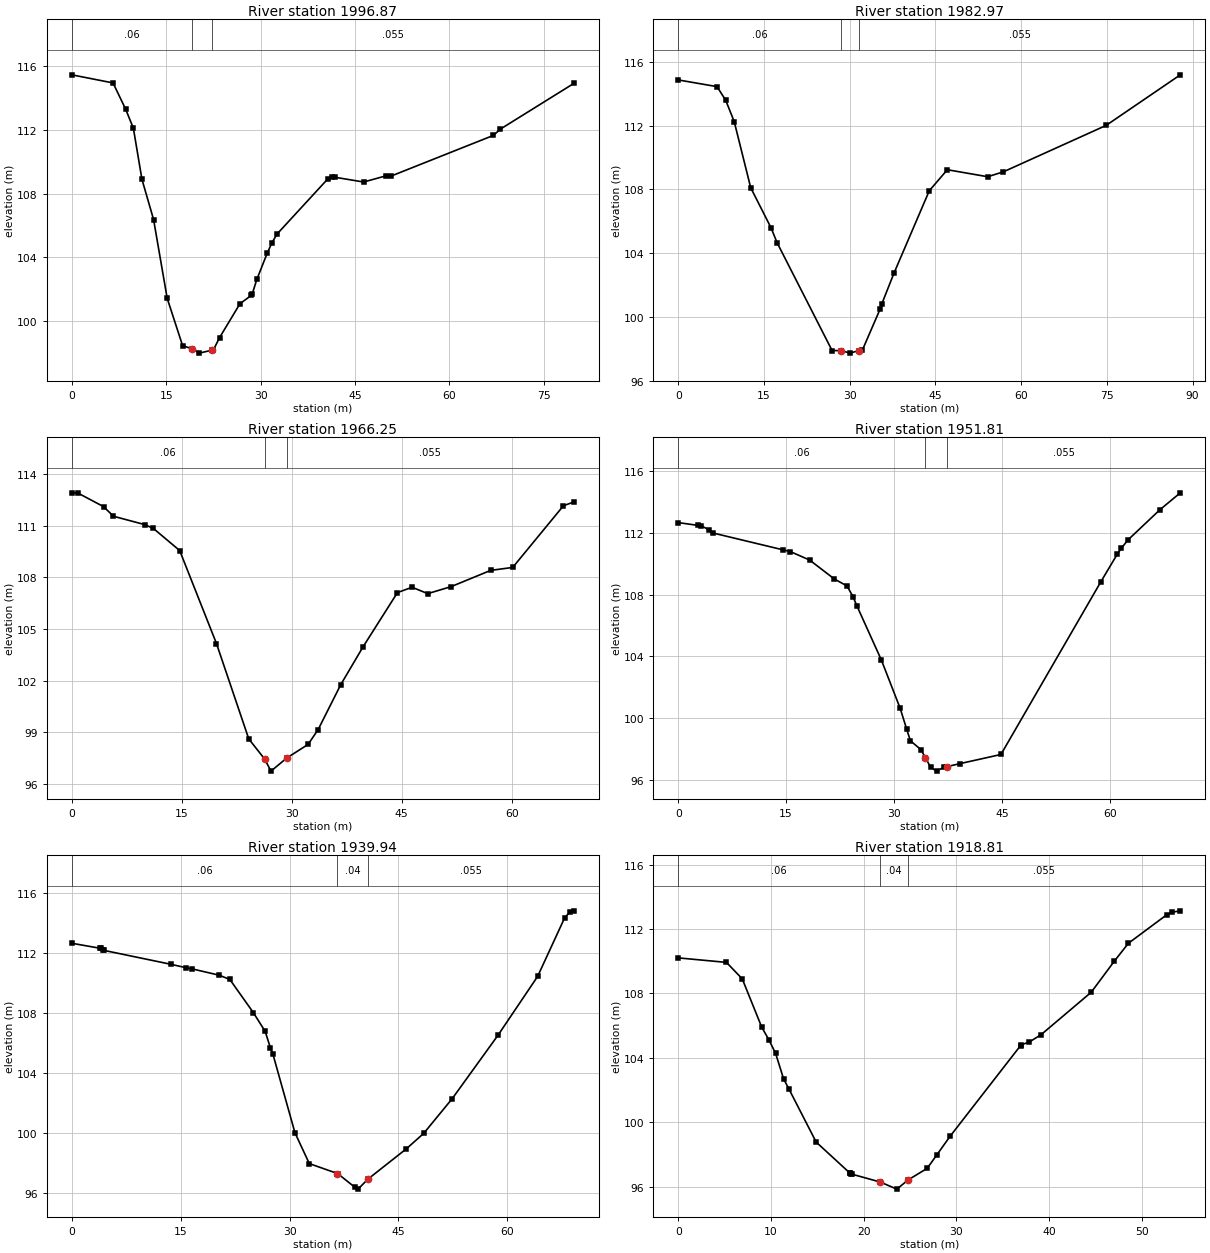
Type RM Length L Ch R = 1 ,1996.87 ,15.36,13.9,10.86
XS GIS Cut Line= 5
343784.0648803715422878.99249268343785.0328979495422862.27288818
343783.2352905275422855.77868652343784.4796752935422838.64471436
 343760.558471685422807.69268799
#Sta/Elev= 29
       0  115.47    6.56  114.96    8.58  113.29    9.79  112.11   11.15   108.9
      13  106.37   15.16  101.42   17.61   98.44   19.14   98.24   20.26   97.97
   22.32   98.16   22.49   98.16   23.49   98.95   26.73  101.08   28.53   101.6
   28.69  101.71   29.41  102.61   31.06  104.26    31.8   104.9    32.6  105.45
   40.67  108.92   41.28  109.03    41.8  109.03   46.38  108.73   49.94  109.12
   50.65  109.09   66.99  111.66   68.12  112.06   79.78  114.93
#Mann= 3 , 0 , 0
       0     .06       0   19.14     .04       0   22.32    .055       0
Bank Sta=19.14,22.32
XS Rating Curve= 0 ,0
Exp/Cntr=0.3,0.1

Type RM Length L Ch R = 1 ,1982.97 ,16.59,16.72,16.4
XS GIS Cut Line= 3
343804.8842773445422879.11907959343804.4791259775422862.90252686
343760.5501098635422806.34429932
#Sta/Elev= 21
       0  114.86    6.78  114.44     8.3  113.59     9.8  112.24   12.68   108.1
   16.22   105.6    17.3  104.65   26.92   97.89   28.53   97.89   30.05   97.73
   31.61   97.89   32.23   97.93   35.34  100.51   35.64  100.84   37.74  102.74
   43.92  107.91   47.08  109.23   54.14  108.79    56.9   109.1   74.87  112.01
   87.84  115.18
#Mann= 3 , 0 , 0
       0     .06       0   28.53     .04       0   31.61    .055       0
Bank Sta=28.53,31.61
XS Rating Curve= 0 ,0
Exp/Cntr=0.3,0.1

Type RM Length L Ch R = 1 ,1966.25 ,12.09,14.44,16.34
XS GIS Cut Line= 6
343820.0289306645422866.68371582343820.0289306645422855.76751709
343812.7005004885422846.64788818343807.3079223635422839.60089111
343793.4805297855422831.58648682343781.7274780275422814.17608643
#Sta/Elev= 24
       0   112.9     .82  112.89    4.33   112.1    5.69  111.54      10  111.05
   11.14  110.83   14.72  109.55   19.74  104.15   24.14   98.62   26.31   97.45
   27.17   96.75   29.32   97.51   32.23    98.3    33.6   99.16   36.69  101.77
   39.71  103.95   44.42  107.11   46.41  107.42   48.56  107.05   51.76  107.46
   57.14   108.4   60.14  108.57   67.06  112.15   68.48  112.37
#Mann= 3 , 0 , 0
       0     .06       0   26.31     .04       0   29.32    .055       0
Bank Sta=26.31,29.32
XS Rating Curve= 0 ,0
Exp/Cntr=0.3,0.1

Type RM Length L Ch R = 1 ,1951.81 ,11.11,11.87,15.26
XS GIS Cut Line= 5
343824.4406738285422869.32012939343825.961486816 5422854.8112793
 343821.536926275422838.23010254343820.9838867195422833.11749268
343804.9440917975422804.37652588
#Sta/Elev= 30
       0  112.68    2.71   112.5    3.11  112.49    4.34   112.2    4.78  112.01
   14.59  110.91   15.58   110.8   18.27  110.25   21.71  109.02   23.47  108.57
   24.29  107.88   24.86  107.26   28.25  103.76   30.86  100.63   31.75    99.3
   32.28   98.53   33.75   97.95   34.38   97.42   35.08   96.82   35.91   96.56
   36.89    96.8   37.43   96.86   39.21   97.05   44.87   97.64   58.76  108.84
   61.03  110.62   61.62  111.02   62.52  111.55   66.99  113.52   69.81  114.61
#Mann= 3 , 0 , 0
       0     .06       0   34.38     .04       0   37.43    .055       0
Bank Sta=34.38,37.43
XS Rating Curve= 0 ,0
Exp/Cntr=0.3,0.1

Type RM Length L Ch R = 1 ,1939.94 ,20.43,21.14,21.98
XS GIS Cut Line= 3
343825.0775146485422870.05511475343831.133911133 5422855.5269165
343835.1715087895422802.25708008
#Sta/Elev= 29
       0  112.67    3.85  112.34    3.99  112.33    4.37  112.24    4.48  112.19
   13.64  111.27   15.74  111.04    16.6  110.96   20.32  110.54   21.77  110.26
   25.01  108.05   26.64   106.8   27.35  105.72   27.72  105.26   30.74  100.05
   32.72   97.99    36.6   97.33   36.62   97.33   38.98   96.42   39.44   96.29
   40.76  96.943    46.1   98.98   48.49  100.01   52.41  102.32   58.71  106.54
   64.17  110.46    67.9  114.37   68.62  114.75   69.16  114.83
#Mann= 3 , 0 , 0
       0     .06       0    36.6     .04       0   40.76    .055       0
Bank Sta=36.6,40.76
XS Rating Curve= 0 ,0
Exp/Cntr=0.3,0.1

Type RM Length L Ch R = 1 ,1918.81 ,8.39,8.49,8.56
XS GIS Cut Line= 4
343848.1270751955422859.49609375343854.6259155275422832.41308594
343857.3914794925422821.49707031343855.7321166995422806.57391357
#Sta/Elev= 29
       0  110.21     5.2  109.93     6.9  108.91    9.01   105.9    9.77  105.13
    10.5  104.28   11.36   102.7   11.92  102.09   14.87   98.78   18.48   96.87
   18.51   96.85   18.58   96.82   18.71   96.79   21.78    96.3   23.57   95.86
   24.78   96.43   26.84   97.15   27.85   97.96   29.31   99.14   36.91  104.77
   36.99  104.82   37.82  104.98   39.11  105.44   44.53  108.08   47.02  110.01
   48.54  111.12   52.68  112.89   53.28  113.05   54.13  113.13
#Mann= 3 , 0 , 0
       0     .06       0   21.78     .04       0   24.78    .055       0
Bank Sta=21.78,24.78
XS Rating Curve= 0 ,0
Exp/Cntr=0.3,0.1

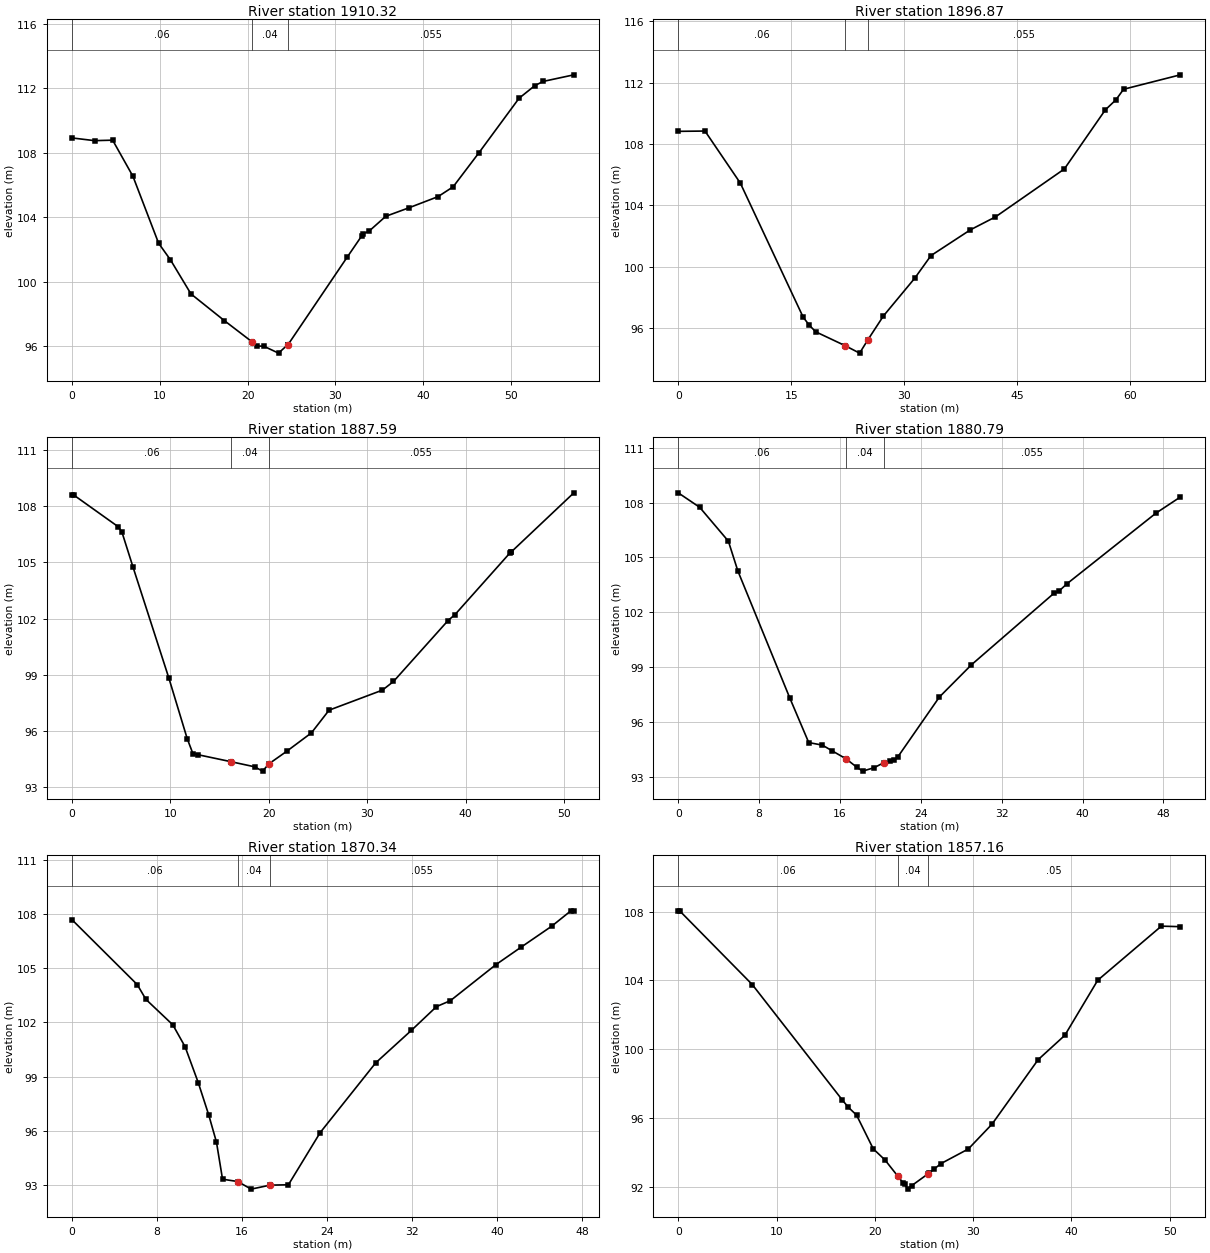
Type RM Length L Ch R = 1 ,1910.32 ,13.55,13.45,13.39
XS GIS Cut Line= 5
 343856.285278325422859.91052246343862.507507324 5422836.1439209
343864.5817260745422827.99151611343863.6137084965422822.74072266
343859.0507202155422804.50128174
#Sta/Elev= 27
       0  108.92    2.59  108.75    4.65  108.78    6.96  106.54    9.88  102.39
   11.23  101.36   13.56   99.25   17.37   97.59   20.51   96.28   21.11   96.02
   21.84   96.01   23.52   95.58   24.57    96.1   24.61   96.11   31.31  101.51
   32.98  102.84   33.16  102.98   33.82  103.14   35.72  104.06   38.32  104.58
   41.67  105.28   43.39  105.89   46.31  107.99   50.89  111.38   52.68  112.16
   53.62  112.42   57.12  112.83
#Mann= 3 , 0 , 0
       0     .06       0   20.51     .04       0   24.57    .055       0
Bank Sta=20.51,24.57
XS Rating Curve= 0 ,0
Exp/Cntr=0.3,0.1

Type RM Length L Ch R = 1 ,1896.87 ,9.42,9.28,9.18
XS GIS Cut Line= 3
343869.6077270515422864.45111084343876.771118164 5422833.8939209
343863.0836791995422801.41888428
#Sta/Elev= 19
       0  108.82    3.55  108.84    8.24  105.45   16.59   96.71   17.41   96.19
   18.24   95.77   22.17   94.86   24.07   94.38   25.17   95.25   27.23    96.8
   31.39   99.26   33.54  100.73   38.78  102.41    42.1  103.25   51.24  106.37
   56.68  110.22   58.08  110.87    59.1  111.56   66.63   112.5
#Mann= 3 , 0 , 0
       0     .06       0   22.17     .04       0   25.17    .055       0
Bank Sta=22.17,25.17
XS Rating Curve= 0 ,0
Exp/Cntr=0.3,0.1

Type RM Length L Ch R = 1 ,1887.59 ,6.51,6.81,7.02
XS GIS Cut Line= 4
343881.896911621 5422860.6217041343883.1412963875422847.90930176
343884.9389038095422839.06591797343881.8969116215422810.04870605
#Sta/Elev= 24
       0  108.59     .18   108.6    4.72   106.9    5.09  106.62    6.23  104.73
    9.87   98.81   11.72    95.6    12.3    94.8   12.77   94.75   16.19   94.37
   18.57    94.1   19.37   93.87   20.02  94.261    21.8   94.92   24.33   95.91
   26.12   97.12   31.54   98.19   32.66   98.65    38.2   101.9   38.91  102.22
   44.51  105.52   44.56  105.54   44.62  105.56   50.97  108.71
#Mann= 3 , 0 , 0
       0     .06       0   16.19     .04       0   20.02    .055       0
Bank Sta=16.19,20.02
XS Rating Curve= 0 ,0
Exp/Cntr=0.3,0.1

Type RM Length L Ch R = 1 ,1880.79 ,11.11,10.44,9.91
XS GIS Cut Line= 4
343887.7042846685422860.34527588343889.3635253915422849.42932129
343891.9907226565422839.89508057343891.8524780275422811.15411377
#Sta/Elev= 23
       0  108.53    2.12  107.74    4.96  105.89     5.9  104.26   11.04   97.32
   12.91   94.89   14.26   94.75   15.22   94.44   16.61      94   17.67   93.54
   18.25   93.33   19.39   93.52   20.33   93.79   20.93   93.87   21.31   93.92
   21.74   94.12   25.84   97.38   29.01   99.14   37.16  103.04    37.7  103.18
   38.45  103.56   47.26  107.42   49.67   108.3
#Mann= 3 , 0 , 0
       0     .06       0   16.61     .04       0   20.33    .055       0
Bank Sta=16.61,20.33
XS Rating Curve= 0 ,0
Exp/Cntr=0.3,0.1

Type RM Length L Ch R = 1 ,1870.34 ,11.52,13.18,13.86
XS GIS Cut Line= 3
343895.5858764655422860.48352051343900.8400878915422848.73828125
343904.4353027345422814.60852051
#Sta/Elev= 23
       0  107.69    6.15  104.09    6.97  103.27     9.5  101.86   10.65  100.65
   11.89   98.66   12.87   96.88    13.6   95.37   14.17   93.32    15.6   93.19
   16.86   92.77   18.63   92.99   20.36   93.01   23.35    95.9   28.57   99.76
   31.91  101.55   34.28  102.87   35.59   103.2   39.86  105.19   42.21  106.15
   45.11  107.32   46.91  108.17   47.19  108.16
#Mann= 3 , 0 , 0
       0     .06       0    15.6     .04       0   18.63    .055       0
Bank Sta=15.6,18.63
XS Rating Curve= 0 ,0
Exp/Cntr=0.3,0.1

Type RM Length L Ch R = 1 ,1857.16 ,7.94,8.89,10
XS GIS Cut Line= 4
 343898.213073735422864.76708984343910.9340820315422853.02191162
343914.6674804695422845.69848633343920.4749145515422820.82647705
#Sta/Elev= 24
       0  108.04     .16  108.03    7.53  103.76    16.7   97.05   17.31   96.63
   18.14   96.18   19.84   94.22   21.04   93.57   22.36  92.617   22.91   92.22
   23.02   92.15   23.39   91.88   23.77   92.09   25.42   92.77   25.53   92.82
   25.98   93.02   26.72   93.36   29.51   94.21   31.92   95.65   36.62    99.4
   39.33  100.81   42.68  104.01   49.15  107.15   51.08  107.12
#Mann= 3 , 0 , 0
       0     .06       0   22.36     .04       0   25.42     .05       0
Bank Sta=22.36,25.42
XS Rating Curve= 0 ,0
Exp/Cntr=0.3,0.1