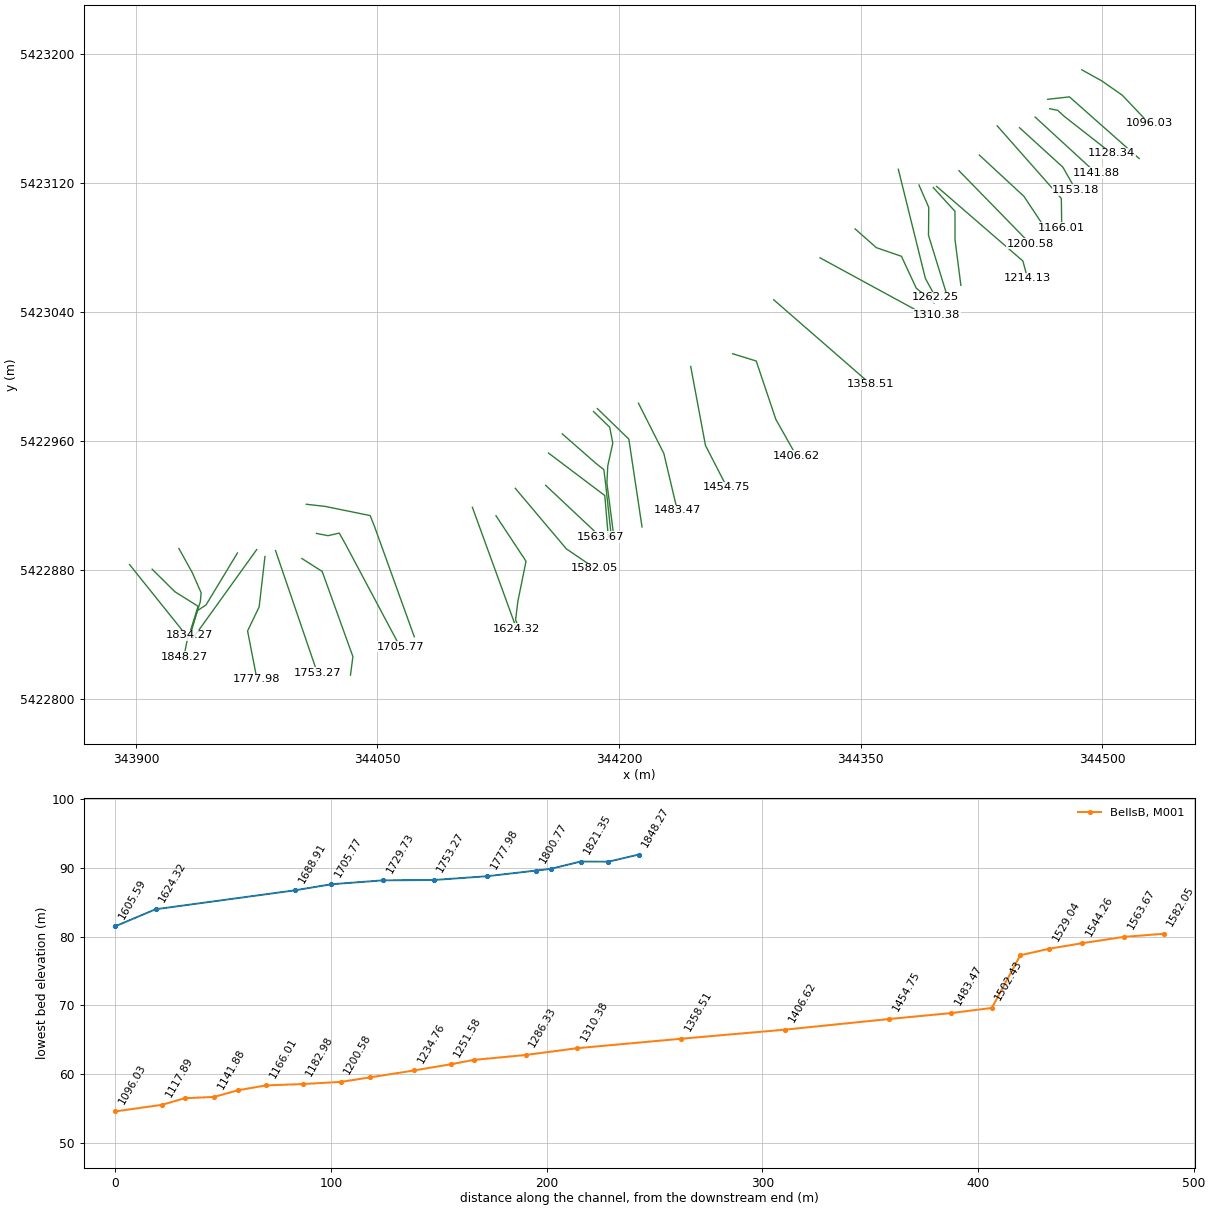
HEC-RAS study Corner_Brook2.prj: Corner_Brook2

--- Corner_Brook2.g02 (geometry) --- (continued)

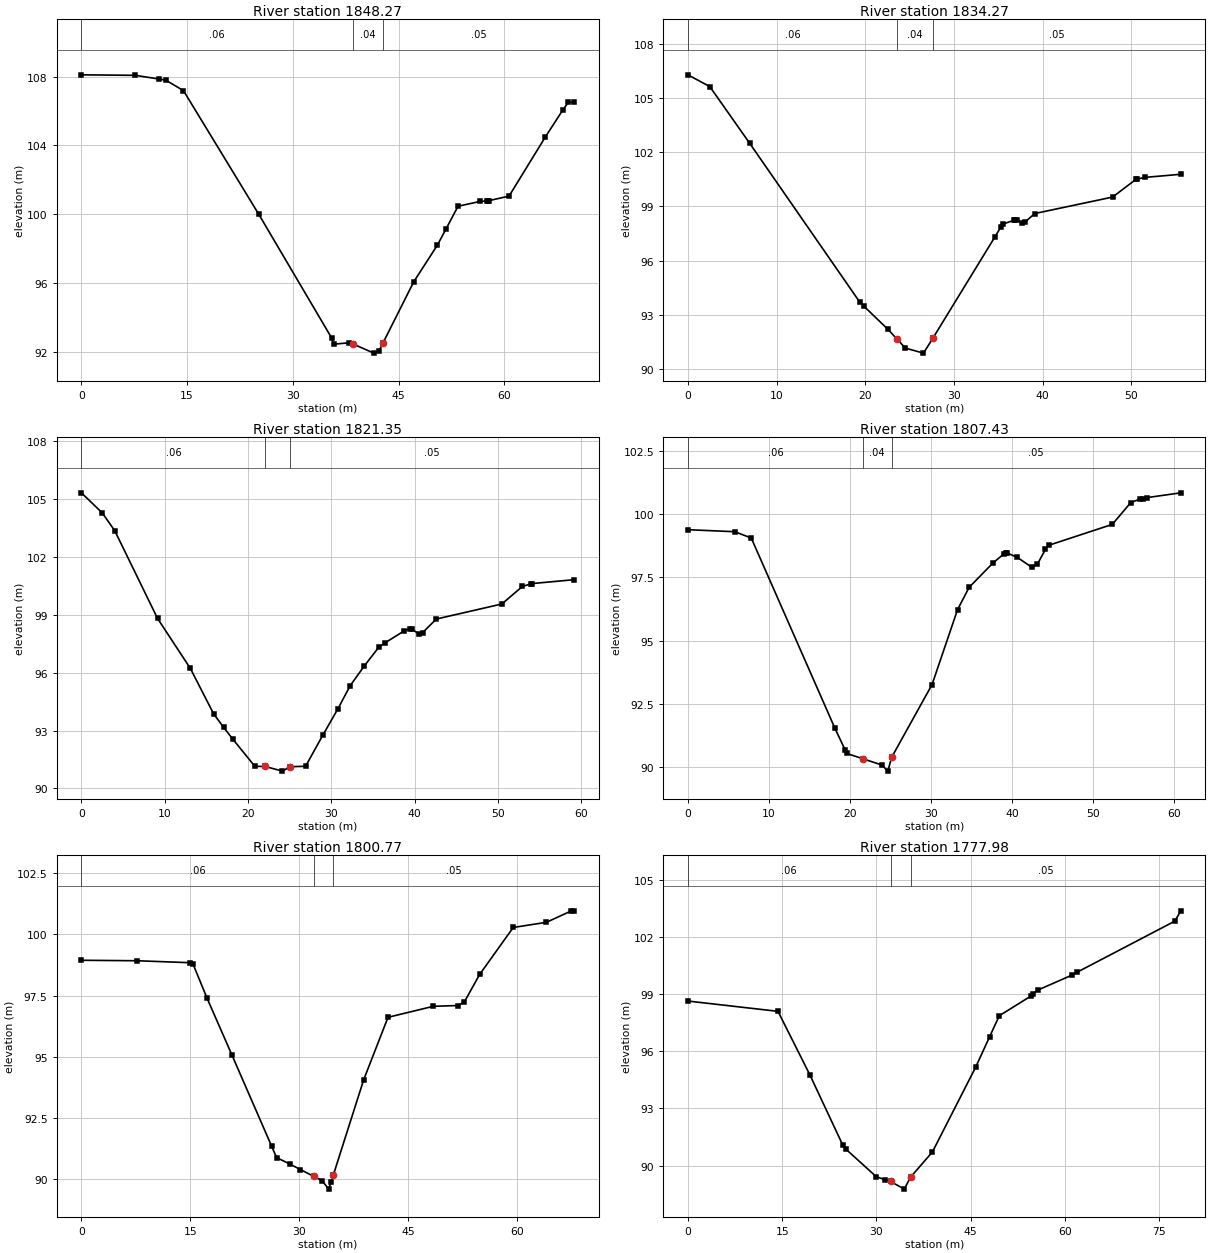
Type RM Length L Ch R = 1 ,1848.27 ,12.45,13.99,15.17
XS GIS Cut Line= 3
343896.088500977 5422883.3649292343932.2098999025422838.39147949
343929.8264770515422826.35388184
#Sta/Elev= 26
       0  108.11    7.65  108.08   10.94  107.87   11.97   107.8   14.48  107.19
   25.17   99.99    35.5    92.8   35.82   92.43   37.95   92.51    38.5   92.45
    41.5   91.91   42.22   92.03   42.78  92.487   47.16   96.06   50.51   98.19
   51.76   99.15   53.45  100.46   56.58  100.74   57.57  100.77   57.68  100.78
   57.87  100.79   60.69  101.05   65.85   104.5    68.3  106.05   69.09   106.5
   69.95  106.51
#Mann= 3 , 0 , 0
       0     .06       0    38.5     .04       0   42.78     .05       0
Bank Sta=38.5,42.78
XS Rating Curve= 0 ,0
Exp/Cntr=0.3,0.1

Type RM Length L Ch R = 1 ,1834.27 ,15.6,12.92,10.12
XS GIS Cut Line= 4
343910.1044921885422880.51928711343924.2083129885422866.56329346
343938.5886840825422857.58172607343933.0576782235422839.61871338
#Sta/Elev= 24
       0  106.27    2.47  105.62    6.96  102.49    19.4   93.69   19.84   93.48
   22.57   92.19   23.56   91.67   24.52   91.16   26.57   90.88   27.65   91.72
   34.63   97.31   35.27   97.83   35.54   98.02    36.8   98.23   36.94   98.26
   37.15   98.23   37.65   98.08   37.99   98.12   39.13    98.6    47.9   99.51
   50.54  100.49   50.62   100.5   51.59   100.6   55.59  100.77
#Mann= 3 , 0 , 0
       0     .06       0   23.56     .04       0   27.65     .05       0
Bank Sta=23.56,27.65
XS Rating Curve= 0 ,0
Exp/Cntr=0.3,0.1

Type RM Length L Ch R = 1 ,1821.35 ,17.76,13.93,9.68
XS GIS Cut Line= 5
 343926.697082525422893.36987305343934.9935302735422878.44671631
343940.5244750985422865.87249756343939.9713134775422860.20709229
343932.9194946295422838.65148926
#Sta/Elev= 30
       0  105.32     2.5  104.28    4.01  103.35    9.14   98.81   13.08   96.22
   15.87   93.87   17.07   93.17   18.17   92.56   20.82   91.15   22.07   91.14
   24.14    90.9   25.07   91.13   26.91   91.15   28.97   92.75   30.81   94.14
   32.26   95.32   33.93   96.33   35.74   97.34    36.5   97.56   38.73   98.16
   39.41   98.29   39.72   98.24   40.48   98.02   40.97   98.08   42.61   98.78
   50.48   99.56   52.95  100.47   54.03  100.61   54.14  100.62   59.18  100.82
#Mann= 3 , 0 , 0
       0     .06       0   22.07     .04       0   25.07     .05       0
Bank Sta=22.07,25.07
XS Rating Curve= 0 ,0
Exp/Cntr=0.3,0.1

Type RM Length L Ch R = 1 ,1807.43 ,6.99,6.66,6.33
XS GIS Cut Line= 4
343963.0629272465422890.60632324 343943.566528325422858.41088867
 343938.173889165422854.81829834343933.4724731455422838.78967285
#Sta/Elev= 28
       0   99.39    5.79   99.31    7.82   99.06   18.11   91.55    19.4   90.67
    19.6   90.53   21.59   90.32   23.95   90.07   24.67   89.83   25.15   90.38
   30.13   93.26   33.28   96.23   34.71   97.11   37.64   98.07   38.95   98.42
   39.27   98.46   39.39   98.47   40.66   98.29   42.45    97.9   43.12   98.02
   44.12   98.61    44.5   98.77   52.37    99.6   54.64  100.46   55.74   100.6
   56.21  100.61   56.64  100.66   60.82  100.85
#Mann= 3 , 0 , 0
       0     .06       0   21.59     .04       0   25.15     .05       0
Bank Sta=21.59,25.15
XS Rating Curve= 0 ,0
Exp/Cntr=0.3,0.1

Type RM Length L Ch R = 1 ,1800.77 ,20.94,22.78,23.41
XS GIS Cut Line= 2
343975.0184936525422892.67388916343935.345092773 5422837.5770874
#Sta/Elev= 25
       0   98.94    7.72   98.92      15   98.84   15.35    98.8   17.32   97.38
   20.73   95.07   26.19   91.35   26.87   90.88   28.67   90.62   30.17   90.39
   31.99  90.111   33.17   89.93   34.05   89.59   34.41    89.9   34.68  90.151
   38.88   94.06   42.23   96.61   48.48   97.06   51.82   97.09   52.73   97.23
   54.85   98.36   59.48  100.28   64.04  100.49   67.43  100.95   67.89  100.96
#Mann= 3 , 0 , 0
       0     .06       0   31.99     .04       0   34.68     .05       0
Bank Sta=31.99,34.68
XS Rating Curve= 0 ,0
Exp/Cntr=0.3,0.1

Type RM Length L Ch R = 1 ,1777.98 ,21.46,24.72,28.06
XS GIS Cut Line= 4
343980.1383056645422888.39147949343976.5432739265422857.16333008
343969.353088379 5422842.2401123343975.1605224615422812.39367676
#Sta/Elev= 21
       0   98.63   14.33   98.09   19.42   94.75   24.65   91.07   25.12   90.87
   29.94   89.43   31.43   89.25   32.26   89.17   34.42   88.77   35.43    89.4
    38.9   90.72   45.79   95.17      48   96.76   49.54   97.86   54.51   98.88
   54.85   99.01   55.63    99.2   61.03   99.98   61.85  100.13   77.47  102.82
   78.41  103.36
#Mann= 3 , 0 , 0
       0     .06       0   32.26     .04       0   35.43     .05       0
Bank Sta=32.26,35.43
XS Rating Curve= 0 ,0
Exp/Cntr=0.3,0.1

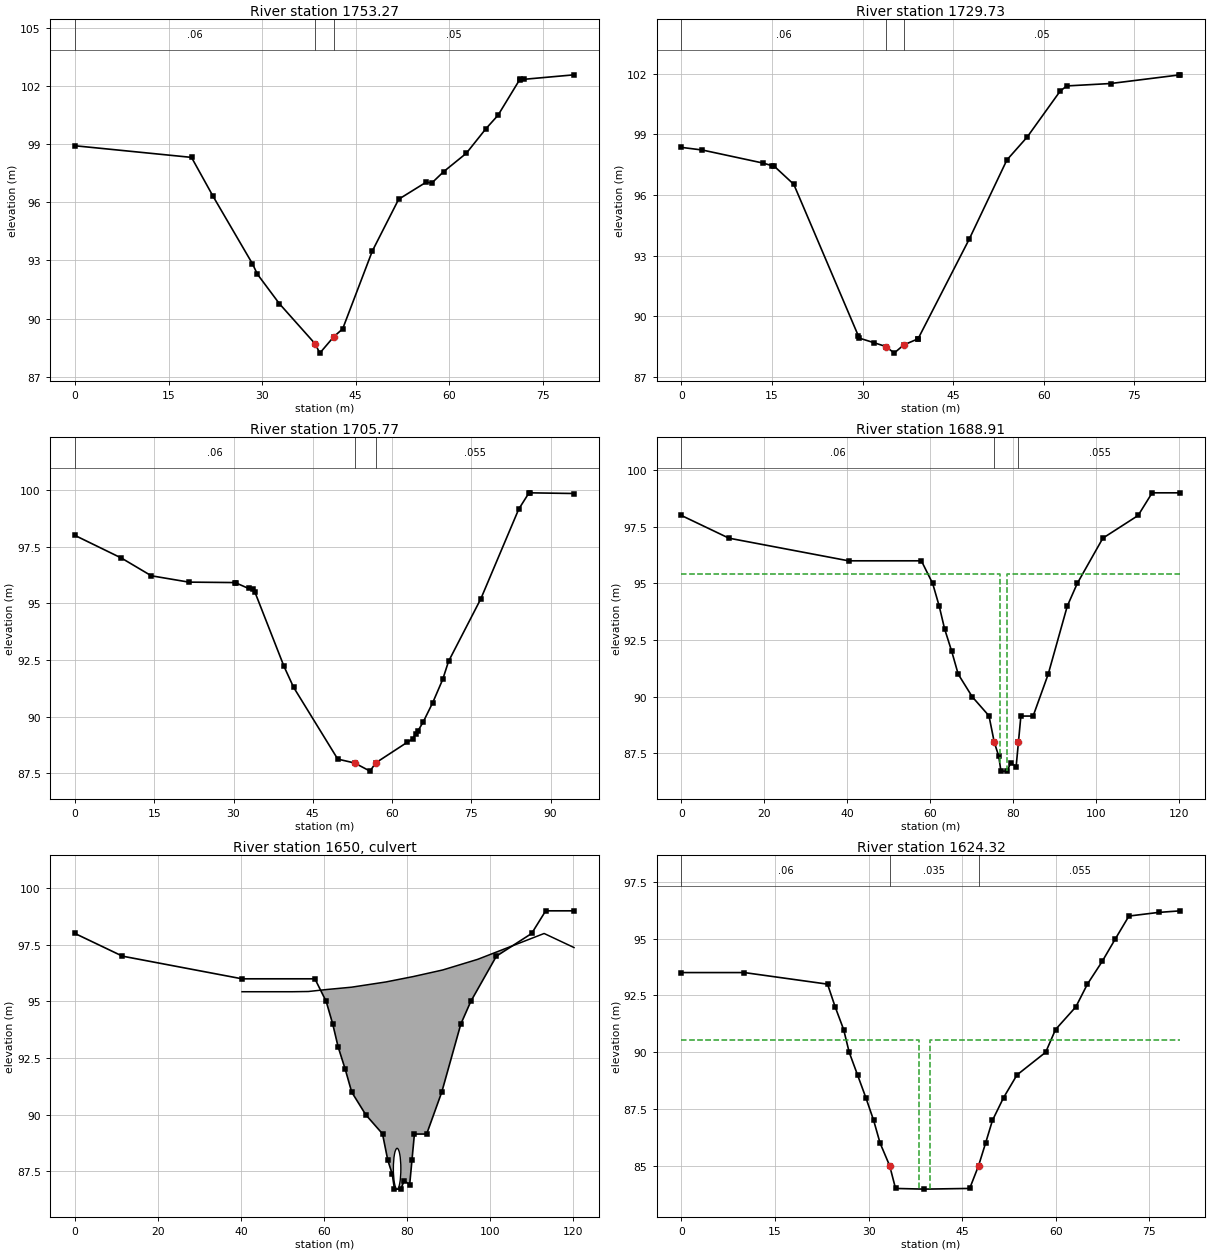
Type RM Length L Ch R = 1 ,1753.27 ,23.46,23.53,23.82
XS GIS Cut Line= 2
 343986.71307373 5422892.0324707344012.6475219735422816.35290527
#Sta/Elev= 22
       0   98.92   18.68   98.32   22.14   96.31   28.45   92.83   29.25   92.29
   32.77   90.77    38.5    88.7   39.25   88.22    41.5   89.07   42.91   89.47
   47.67   93.49   51.89   96.16    56.3   97.04   57.21      97   59.09   97.58
   62.73   98.53   65.88    99.8   67.81  100.49   71.29  102.33   71.32  102.34
   72.02  102.35      80  102.58
#Mann= 3 , 0 , 0
       0     .06       0    38.5     .04       0    41.5     .05       0
Bank Sta=38.5,41.5
XS Rating Curve= 0 ,0
Exp/Cntr=0.3,0.1

Type RM Length L Ch R = 1 ,1729.73 ,23.22,23.97,25.7
XS GIS Cut Line= 4
344003.0916748055422887.14788818344015.6744995125422879.13348389
344034.7561035165422826.34967041344033.2351074225422814.88092041
#Sta/Elev= 22
       0   98.35    3.45   98.22   13.56   97.57   14.92   97.45   15.28   97.44
    18.6   96.52   29.29   89.02   29.47   88.91   31.83   88.69   33.89  88.492
   35.21   88.17   36.78  88.572   39.18   88.88   39.19   88.89   47.64   93.81
   53.88   97.73   57.23   98.86   62.66  101.12   63.76  101.39   71.05  101.51
    82.3  101.93   82.61  101.94
#Mann= 3 , 0 , 0
       0     .06       0   33.89     .04       0   36.78     .05       0
Bank Sta=33.89,36.78
XS Rating Curve= 0 ,0
Exp/Cntr=0.3,0.1

Type RM Length L Ch R = 1 ,1705.77 ,17.93,16.86,16.52
Node Photo=..\..\..\..\Corner Brook\Windshield Survey\CB photos\P1000705.JPG
XS GIS Cut Line= 5
      344012.139     5422902.717      344019.302     5422901.315
       344026.26     5422902.924      344029.788     5422896.702
      344064.067     5422832.421
#Sta/Elev= 28
       0      98     8.8      97   14.44   96.22   21.54   95.94    30.3   95.92
   30.41   95.91   32.85   95.66   33.78   95.64   34.05    95.5   39.56   92.22
   41.37    91.3   49.73   88.13   52.91   87.96   55.84    87.6    56.9  87.962
   62.86   88.87    63.9   89.02   64.48   89.24   64.86   89.36   65.86   89.75
    67.7   90.62    69.6   91.65   70.69   92.44   76.82   95.21   83.98   99.16
    85.9   99.87   86.12   99.88   94.44   99.85
#Mann= 3 , 0 , 0
       0     .06       0   52.91    .035       0    56.9    .055       0
Bank Sta=52.91,56.9
XS Rating Curve= 0 ,0
Exp/Cntr=0.3,0.1

Type RM Length L Ch R = 1 ,1688.91 ,64.88,64.59,65.49
XS GIS Cut Line= 5
      344005.862     5422920.796      344017.456     5422919.468
      344045.474     5422913.779      344048.045     5422907.328
       344072.87     5422838.617
#Sta/Elev= 27
       0      98   11.43      97   40.26      96   57.82      96   60.54      95
   62.12      94   63.41      93   65.14      92   66.69      91   70.08      90
   74.11   89.16   75.38      88   76.46   87.38   76.99   86.72   78.53   86.72
   79.32   87.09   80.66   86.92   81.21  87.996    81.8   89.15   84.75   89.15
   88.39      91   92.98      94   95.38      95  101.56      97  110.05      98
  113.44      99  120.26      99
#Mann= 3 , 0 , 0
       0     .06       0   75.38    .035       0   81.21    .055       0
#XS Ineff= 2 , 0
       0   76.73   95.43   78.53       0   95.43
Permanent Ineff=
       F       F
Bank Sta=75.38,81.21
XS Rating Curve= 0 ,0
Exp/Cntr=0.5,0.3

Type RM Length L Ch R = 2 ,1650    ,,,
BEGIN DESCRIPTION:
Bliss Street (Structure #2120)
END DESCRIPTION:
Bridge Culvert--1,0,-1,-1, 0
Deck Dist Width WeirC Skew NumUp NumDn MinLoCord MaxHiCord MaxSubmerge Is_Ogee
21.2,15.5,1.67,0, 11, 13, 95.43, , 0.98, 0, 0.7,0.53,,
   40.26   52.35   56.26   60.77   66.61   74.88   81.52   88.61   97.05  113.06
  120.26
   95.43   95.43   95.44   95.53   95.63   95.86    96.1   96.39   96.86      98
   97.38
                                                                                
        
       0   10.32   13.62   17.53   22.04   28.85   36.98   44.83   51.73   59.58
   67.12    75.2      80
      95      95   95.43   95.44   95.53   94.97   95.53   96.06   96.49   96.95
   97.28   97.38   97.38
                                                                                
                        
BR Coef=-1 , 0 , 0 ,, 0 ,,,0.8,-1,,0,
WSPro=,,,, 1 ,,,, 0 ,,,, 0 ,,,,-1 ,-1 ,-1 , 0 , 0 , 0 , 0 , 0
Culvert=1,1.8,,56,0.03,0.5,1,2,1,86.72,77.63,84.33,38.91,Culvert #1  , 0 ,4.4
Culvert Bottom n=0.03
BC Design=,, 0 ,, 0 ,,,,,,
BC Use User HTab Curves=0
BC User HTab FreeFlow(D)= 0

Type RM Length L Ch R = 1 ,1624.32 ,17.6,18.73,19.48
Node Photo=..\..\..\..\Corner Brook\Windshield Survey\CB photos\P1000701.JPG
XS GIS Cut Line= 2
344108.9406738285422918.89208984344136.3378906255422843.72967529
#Sta/Elev= 28
       0   93.51   10.08   93.51   23.42      93   24.64      92      26      91
   26.89      90   28.23      89   29.56      88   30.81      87   31.84      86
   33.38      85   34.32      84   38.91   83.97   46.21      84   47.63      85
   48.76      86   49.86      87   51.64      88   53.79      89   58.39      90
   59.97      91   63.23      92   65.08      93   67.45      94   69.57      95
   71.74      96   76.49   96.16      80   96.23
#Mann= 3 , 0 , 0
       0     .06       0   33.38    .035       0   47.63    .055       0
#XS Ineff= 2 , 0
       0   38.01   90.55   39.81       0   90.55
Permanent Ineff=
       F       F
Bank Sta=33.38,47.63
XS Rating Curve= 0 ,0
Exp/Cntr=0.5,0.3

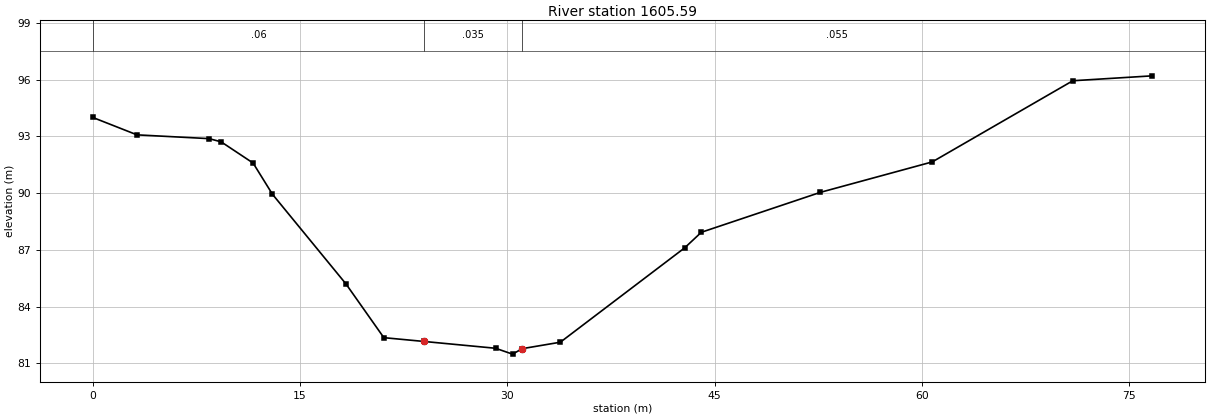
Type RM Length L Ch R = 1 ,1605.59 ,22.78,23.54,25
Node Photo=..\..\..\..\Corner Brook\Windshield Survey\CB photos\P1000703.JPG
XS GIS Cut Line= 5
344123.5905151375422913.68847656344142.2462768555422885.46252441
344137.1588745125422860.46691895344135.7728881845422849.03912354
 344138.025329595422843.67150879
#Sta/Elev= 19
       0      94     3.2   93.08    8.42   92.88    9.29   92.71    11.6   91.59
      13   89.94   18.32    85.2   21.06   82.36   23.96   82.16   29.14    81.8
   30.37   81.49   31.08   81.78   33.83   82.12   42.83   87.11   44.03   87.93
   52.64   90.04   60.74   91.65   70.91   95.94   76.67    96.2
#Mann= 3 , 0 , 0
       0     .06       0   23.96    .035       0   31.08    .055       0
Bank Sta=23.96,31.08
XS Rating Curve= 0 ,0
Exp/Cntr=0.3,0.1

River Reach=BellsB          ,M001

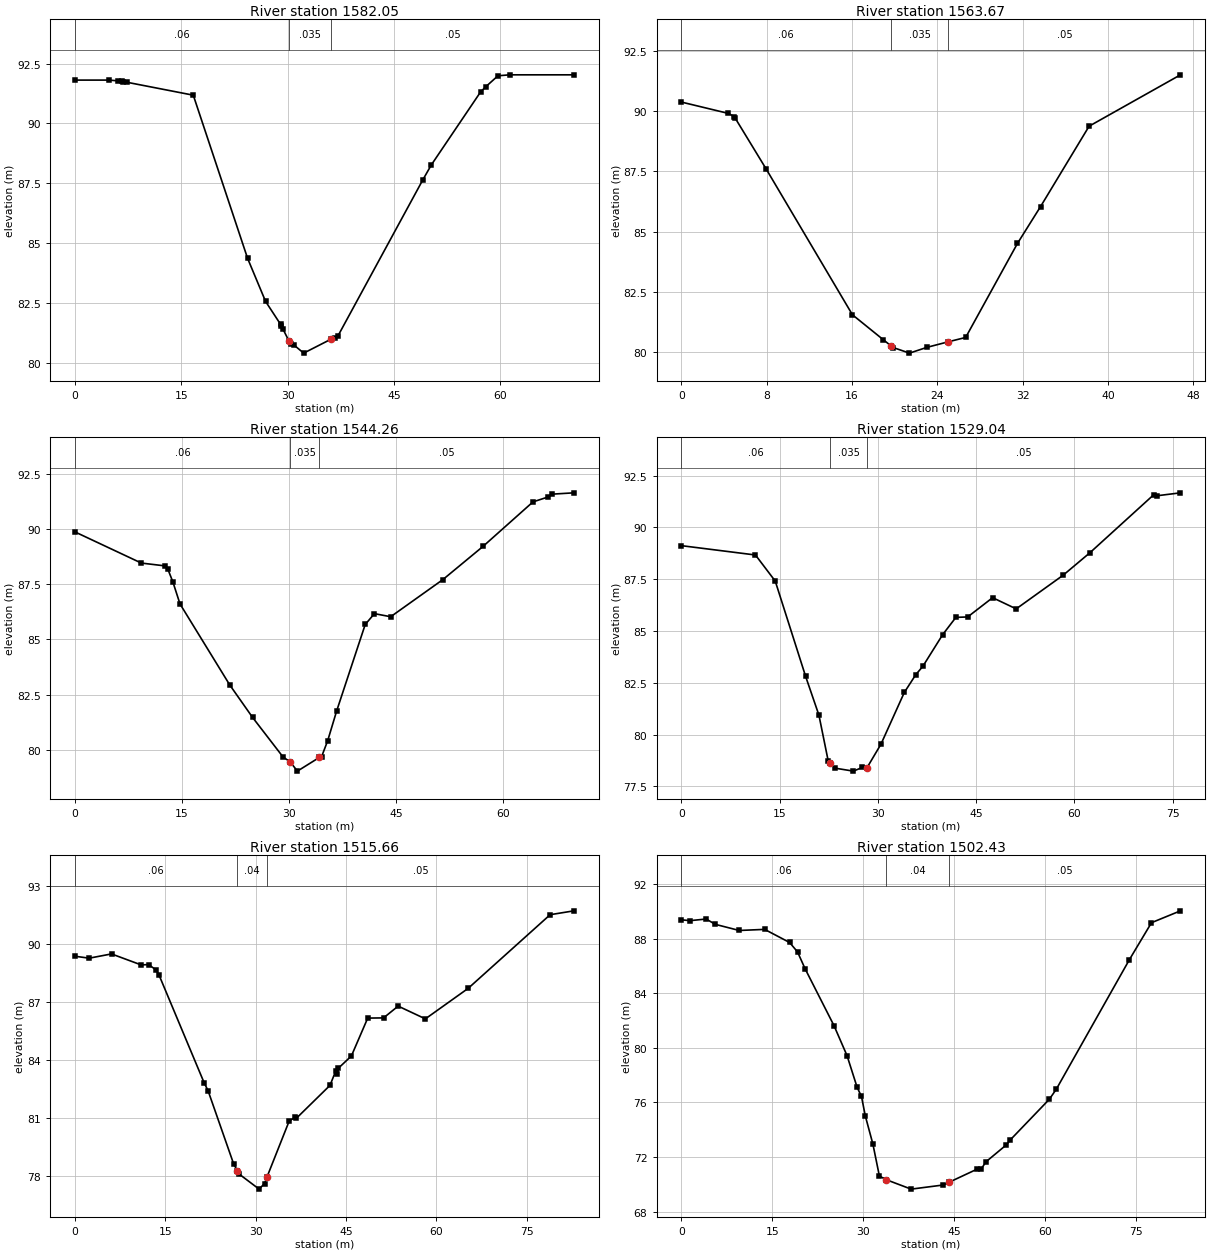
Type RM Length L Ch R = 1 ,1582.05 ,17.81,18.37,19.1
XS GIS Cut Line= 3
344135.5728759775422930.68328857344167.2293090825422893.19610596
344184.8796997075422881.19189453
#Sta/Elev= 26
       0   91.81    4.82   91.81       6   91.78    6.57   91.77    6.77   91.75
    7.32   91.72   16.69   91.18   24.35   84.37   26.89   82.57   29.01   81.61
   29.11   81.53   29.37    81.4   30.17  80.928   30.42   80.78   30.93   80.74
   32.27   80.41   36.11   80.99    36.7   81.05   37.07   81.11   49.07   87.64
   50.28   88.27   57.24   91.32   57.95   91.53   59.68   91.99   61.34   92.03
   70.41   92.03
#Mann= 3 , 0 , 0
       0     .06       0   30.17    .035       0   36.11     .05       0
Bank Sta=30.17,36.11
XS Rating Curve= 0 ,0
Exp/Cntr=0.3,0.1

Type RM Length L Ch R = 1 ,1563.67 ,18.98,19.42,20.26
XS GIS Cut Line= 2
344154.485717773 5422932.4967041344188.6195068365422900.46429443
#Sta/Elev= 17
       0   90.37     4.4    89.9    4.94   89.77    5.02   89.72    7.94    87.6
   16.04   81.55   18.95   80.51   19.66   80.26   19.87   80.19   21.39   79.96
   23.03    80.2   25.03   80.43   26.66   80.61   31.52   84.51   33.69   86.04
   38.24   89.37   46.81    91.5
#Mann= 3 , 0 , 0
       0     .06       0   19.66    .035       0   25.03     .05       0
Bank Sta=19.66,25.03
XS Rating Curve= 0 ,0
Exp/Cntr=0.3,0.1

Type RM Length L Ch R = 1 ,1544.26 ,15.64,15.21,13.49
XS GIS Cut Line= 3
344156.2185058595422952.52209473344191.1436767585422926.21228027
344193.3801269535422900.07452393
#Sta/Elev= 24
       0   89.87     9.3   88.46   12.68   88.33   13.01   88.19   13.72   87.61
   14.72   86.61    21.7   82.94    24.9   81.47   29.17   79.68   30.17   79.46
   31.18   79.04   34.26   79.66   34.58    79.7   35.43   80.42   36.69   81.77
   40.69   85.68   41.98   86.17   44.26   86.03   51.57   87.71   57.19   89.21
   64.21   91.23   66.31   91.45   66.89   91.58   69.96   91.64
#Mann= 3 , 0 , 0
       0     .06       0   30.17    .035       0   34.26     .05       0
Bank Sta=30.17,34.26
XS Rating Curve= 0 ,0
Exp/Cntr=0.3,0.1

Type RM Length L Ch R = 1 ,1529.04 ,18.66,13.38,5.34
XS GIS Cut Line= 5
344164.751708984 5422964.4151001344185.5438842775422946.23449707
344190.568725586 5422942.2520752344191.6082763675422933.94091797
344195.2468872075422900.35009766
#Sta/Elev= 25
       0   89.12    11.3   88.67   14.32   87.41   18.96   82.81   20.99   80.94
   22.42   78.71   22.69   78.63    23.5   78.38   26.26   78.24   27.62   78.42
   28.34   78.41   30.46   79.54   34.03   82.04   35.79    82.9   36.86    83.3
   39.89   84.83    41.9   85.66    43.7   85.68   47.51   86.61   51.11   86.07
    58.3    87.7   62.37   88.78   72.08   91.57   72.64   91.53   76.19   91.67
#Mann= 3 , 0 , 0
       0     .06       0   22.69    .035       0   28.34     .05       0
Bank Sta=22.69,28.34
XS Rating Curve= 0 ,0
Exp/Cntr=0.3,0.1

Type RM Length L Ch R = 1 ,1515.66 ,11.06,13.23,17.9
XS GIS Cut Line= 6
344184.1577148445422978.26690674344194.2072753915422968.57067871
 344196.113281255422958.70111084344192.9945068365422944.50292969
344192.4744873055422933.94091797344196.8062744145422900.52331543
#Sta/Elev= 30
       0   89.35    2.36   89.25    6.06   89.47      11    88.9   12.23   88.92
   13.45   88.64   13.96   88.37   21.44    82.8   22.08    82.4   26.35   78.59
   26.95   78.26   27.29   78.07   30.56    77.3   31.46   77.59    31.9   77.95
   35.55   80.82   36.48   81.01   36.73   80.96   42.33   82.67    43.3   83.43
   43.45   83.25   43.73   83.56   45.88   84.19   48.59   86.15   51.22   86.16
   53.64   86.77   58.16   86.11   65.27   87.69   78.87    91.5   82.83    91.7
#Mann= 3 , 0 , 0
       0     .06       0   26.95     .04       0    31.9     .05       0
Bank Sta=26.95,31.9
XS Rating Curve= 0 ,0
Exp/Cntr=0.3,0.1

Type RM Length L Ch R = 1 ,1502.43 ,17.13,18.96,22.01
XS GIS Cut Line= 3
344186.5355224615422980.11029053344206.0902709965422961.16369629
 344214.271301275422906.71710205
#Sta/Elev= 30
       0   89.38    1.43   89.32    4.08   89.44    5.57   89.05    9.53    88.6
   13.72   88.68   17.83   87.72   19.14   87.03   20.37   85.81   25.16   81.62
   27.31   79.42   28.97    77.1   29.69   76.43   30.31   75.02   31.57   72.94
   32.64    70.6   33.78   70.33   37.88   69.64   43.13   69.94   44.16   70.15
   48.73    71.1   49.41    71.1   50.21   71.64   53.59   72.89   54.25   73.26
   60.67   76.23   61.81   76.96   73.88   86.47   77.51   89.17   82.29   90.04
#Mann= 3 , 0 , 0
       0     .06       0   33.78     .04       0   44.16     .05       0
Bank Sta=33.78,44.16
XS Rating Curve= 0 ,0
Exp/Cntr=0.3,0.1

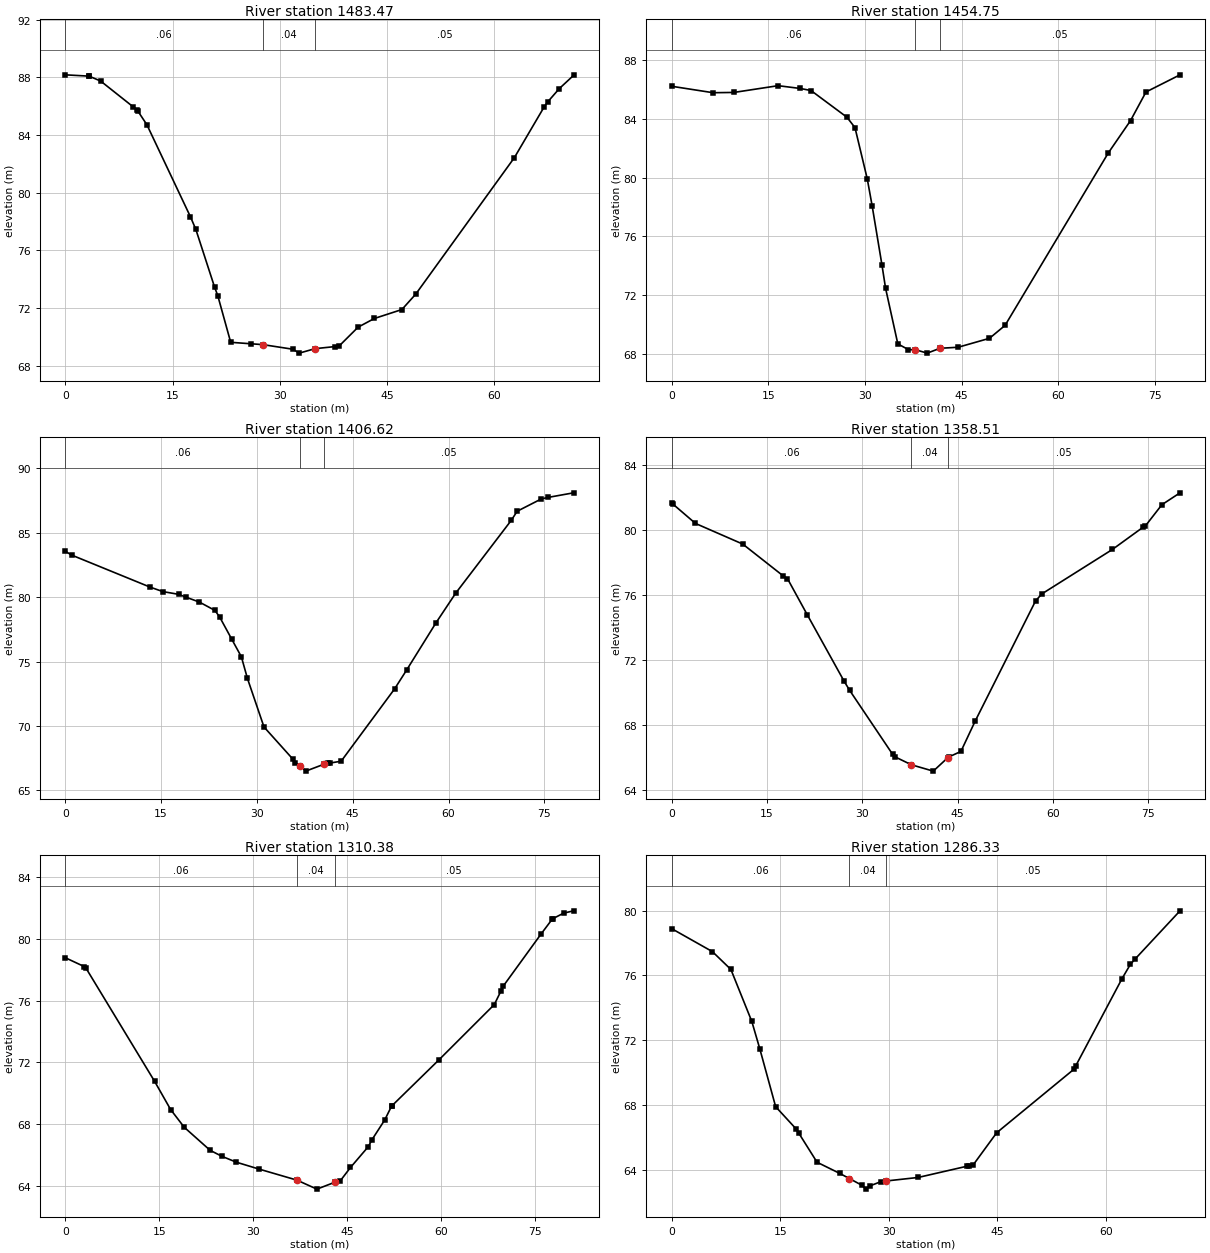
Type RM Length L Ch R = 1 ,1483.47 ,29.95,28.73,27.26
XS GIS Cut Line= 3
344212.0538940435422983.46130371344227.8212890635422952.29467773
344236.1381225595422917.14550781
#Sta/Elev= 29
       0   88.17     3.3   88.08    3.38   88.07    4.95   87.74    9.48   85.96
   10.07   85.74   10.18   85.64   11.42   84.71   17.49   78.35   18.26   77.46
   20.88   73.46   21.32   72.88   23.13   69.64    25.9   69.54   27.62   69.48
   31.82   69.16   32.71   68.89   34.93    69.2   37.64   69.34   38.28   69.38
   40.94   70.69   43.21   71.29   47.06   71.91      49   72.98   62.79   82.44
   66.97   85.97   67.43   86.29   69.07   87.22   71.05   88.13
#Mann= 3 , 0 , 0
       0     .06       0   27.62     .04       0   34.93     .05       0
Bank Sta=27.62,34.93
XS Rating Curve= 0 ,0
Exp/Cntr=0.3,0.1

Type RM Length L Ch R = 1 ,1454.75 ,46.23,48.12,48.46
XS GIS Cut Line= 3
344244.5089111335423006.18249512 344253.685485845422957.21392822
344267.0140991215422931.34307861
#Sta/Elev= 24
       0   86.22    6.43   85.78    9.67    85.8   16.53   86.26   19.97   86.07
   21.63   85.93   27.21   84.11   28.46    83.4   30.37    79.9   31.12   78.08
   32.64   74.06   33.21   72.45   35.11   68.66   36.75   68.27   37.85   68.26
   39.68   68.03   41.66   68.36   44.47   68.43   49.34   69.04   51.76   69.92
   67.78   81.67   71.24   83.88   73.64   85.83   78.92      87
#Mann= 3 , 0 , 0
       0     .06       0   37.85     .04       0   41.66     .05       0
Bank Sta=37.85,41.66
XS Rating Curve= 0 ,0
Exp/Cntr=0.3,0.1

Type RM Length L Ch R = 1 ,1406.62 ,45.67,48.12,50.82
XS GIS Cut Line= 4
 344270.56427002 5423014.0925293344285.178710938 5423009.6060791
344297.3618774415422973.44549561344310.1868896485422950.69970703
#Sta/Elev= 30
       0   83.57     .99   83.27   13.28   80.78   15.29   80.43   17.74   80.22
   18.94   79.99   20.99   79.62   23.43   78.97   24.17   78.46   26.07   76.73
   27.57   75.37   28.52   73.69   31.11   69.92   35.58   67.45   35.95    67.1
    36.8   66.91   37.65   66.49   40.58   67.04   41.19   67.11   41.46   67.12
   43.19   67.26   51.56   72.88   53.45   74.35   58.05   78.02   61.12   80.31
   69.81   85.96   70.74   86.67   74.53   87.63   75.64   87.75   79.56    88.1
#Mann= 3 , 0 , 0
       0     .06       0    36.8     .04       0   40.58     .05       0
Bank Sta=36.8,40.58
XS Rating Curve= 0 ,0
Exp/Cntr=0.3,0.1

Type RM Length L Ch R = 1 ,1358.51 ,45.41,48.12,49.91
XS GIS Cut Line= 2
344296.0416870125423047.56292725344356.4254760745422995.08648682
#Sta/Elev= 24
       0   81.66     .22   81.57    3.74   80.39   11.19   79.12   17.57   77.16
   18.22      77   21.35   74.77   27.13    70.7      28   70.14   34.76   66.21
   35.19   66.04   37.73   65.56   41.17   65.17   43.44   65.99   43.61   66.04
   45.52   66.38   47.76   68.24   57.26   75.62   58.22   76.05   69.36   78.79
   74.13   80.14    74.5   80.21   77.15   81.54      80   82.27
#Mann= 3 , 0 , 0
       0     .06       0   37.73     .04       0   43.44     .05       0
Bank Sta=37.73,43.44
XS Rating Curve= 0 ,0
Exp/Cntr=0.3,0.1

Type RM Length L Ch R = 1 ,1310.38 ,22.48,24.05,23.98
XS GIS Cut Line= 3
344324.8247070315423073.56048584344385.9348754885423040.35491943
344397.3156738285423038.21850586
#Sta/Elev= 29
       0   78.77    3.06   78.19    3.29   78.11   14.27   70.77   16.82   68.95
      19    67.8   23.13   66.31   25.02   65.92   27.33   65.54   30.99   65.09
      37   64.38   40.17    63.8   43.07   64.25   43.87   64.32   45.53    65.2
   48.38   66.55   48.95   66.99   50.99   68.27   52.08   69.16   52.17    69.2
   59.67   72.17   68.49   75.74   69.55   76.62   69.93   76.94   75.91   80.28
   77.69   81.24   77.86    81.3   79.55   81.65   81.13    81.8
#Mann= 3 , 0 , 0
       0     .06       0      37     .04       0   43.07     .05       0
Bank Sta=37,43.07
XS Rating Curve= 0 ,0
Exp/Cntr=0.3,0.1

Type RM Length L Ch R = 1 ,1286.33 ,28.88,24.08,12.48
XS GIS Cut Line= 5
344346.5858764655423091.49310303344359.7540893555423079.89208984
344375.348327637 5423074.5244751344384.5314941415423054.78552246
344395.6204833985423045.60870361
#Sta/Elev= 27
       0   78.89    5.63   77.47    8.18   76.37   11.07   73.16   12.18   71.46
   14.36    67.9   17.24    66.5   17.55   66.27   20.08   64.47   23.22   63.78
   24.56   63.46   26.31   63.04    26.8   62.81   27.39   63.01   28.94   63.28
   29.56   63.31   34.04   63.53   40.75   64.22   41.07   64.26   41.67   64.32
   44.89   66.29   55.53    70.2   55.81   70.42   62.21   75.81   63.35   76.68
      64   77.01   70.21   79.99
#Mann= 3 , 0 , 0
       0     .06       0   24.56     .04       0   29.56     .05       0
Bank Sta=24.56,29.56
XS Rating Curve= 0 ,0
Exp/Cntr=0.3,0.1

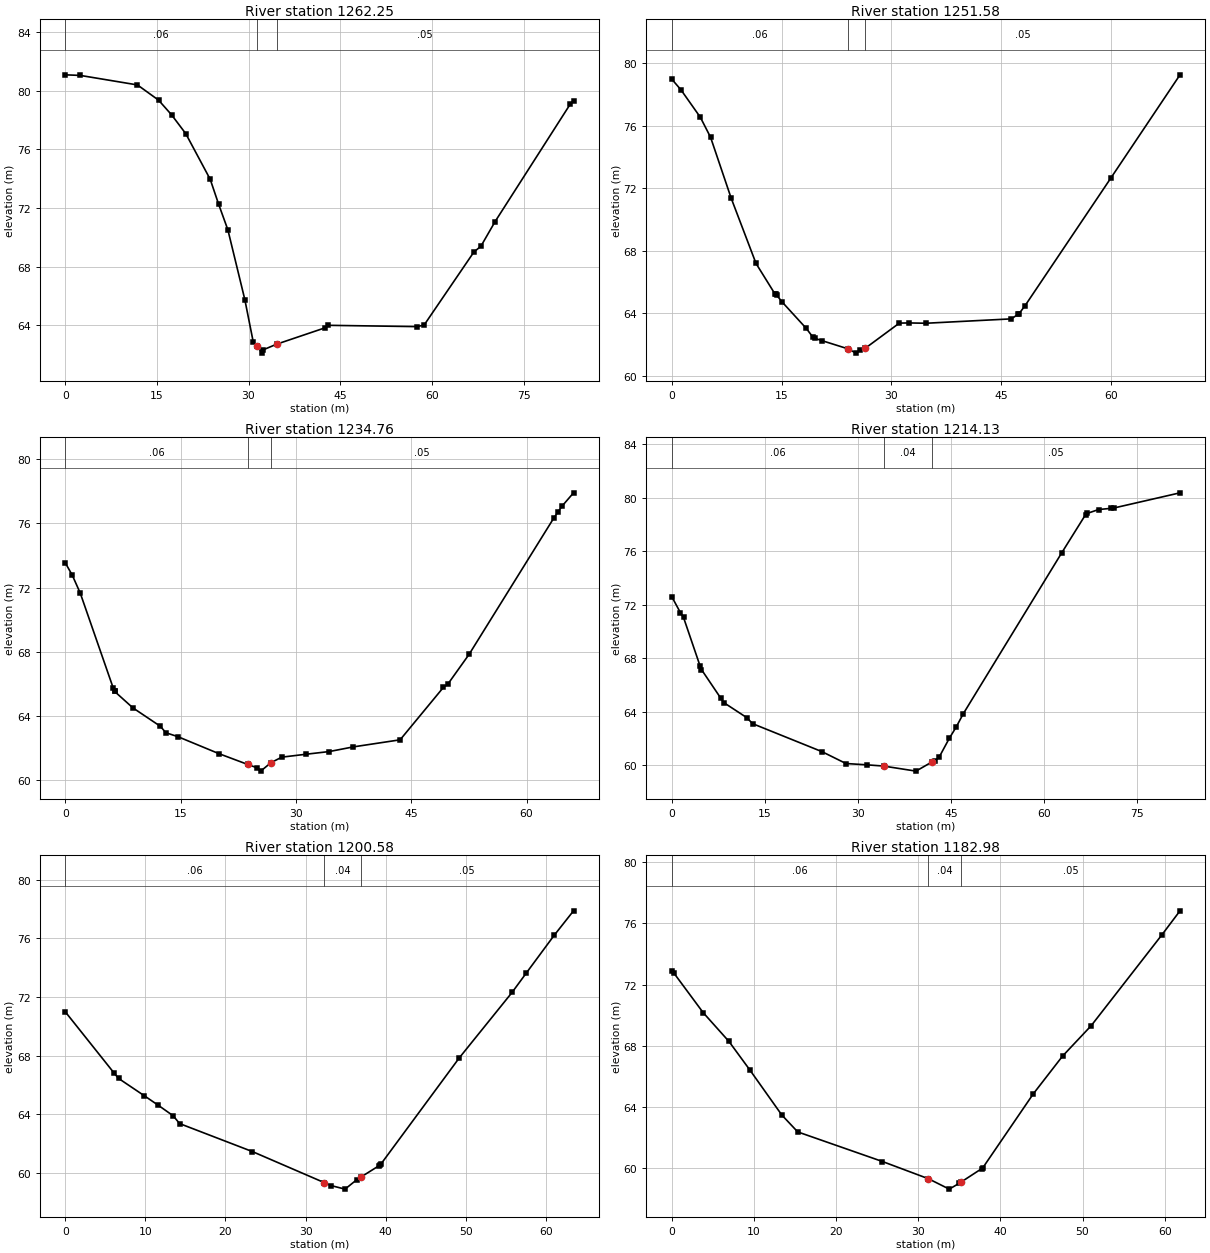
Type RM Length L Ch R = 1 ,1262.25 ,11.71,10.67,8.64
XS GIS Cut Line= 3
344373.4210815435423128.46972656344390.2106933595423060.81689453
344396.6876831055423048.99932861
#Sta/Elev= 24
       0    81.1    2.46   81.06   11.82   80.41   15.28   79.37    17.4   78.37
   19.73   77.08   23.73   73.96   25.09   72.28   26.62   70.51   29.39   65.75
   30.78   62.83   31.42    62.6   32.18   62.09   32.31    62.3   34.59    62.7
   42.46   63.81   42.98   63.99   57.64    63.9   58.75   64.02   66.88      69
   68.02   69.39   70.35   71.08   82.66   79.11   83.18   79.34
#Mann= 3 , 0 , 0
       0     .06       0   31.42     .04       0   34.59     .05       0
Bank Sta=31.42,34.59
XS Rating Curve= 0 ,0
Exp/Cntr=0.3,0.1

Type RM Length L Ch R = 1 ,1251.58 ,16.36,16.82,15.21
XS GIS Cut Line= 4
344386.2640991215423118.67730713344392.3284912115423104.82550049
344392.1552734385423087.51068115344403.0711059575423052.18829346
#Sta/Elev= 27
       0   78.98    1.27   78.29    3.91   76.54    5.31   75.26    8.12   71.37
   11.52   67.19   14.08   65.26   14.19   65.21   14.33   65.17   15.12   64.71
   18.38   63.04   19.27   62.49   19.53   62.41   20.51   62.26   24.03  61.741
   25.18   61.46   25.71   61.65   26.46   61.78   31.09   63.38   32.44   63.39
   34.72   63.37   46.38   63.65   47.27   63.93   47.36   63.94   48.22   64.47
   59.95   72.64   69.41   79.25
#Mann= 3 , 0 , 0
       0     .06       0   24.03     .04       0   26.46     .05       0
Bank Sta=24.03,26.46
XS Rating Curve= 0 ,0
Exp/Cntr=0.3,0.1

Type RM Length L Ch R = 1 ,1234.76 ,6.86,20.63,23.19
XS GIS Cut Line= 4
344395.1008911135423117.11907959344408.6157226565423102.40148926
344408.6157226565423084.91333008344412.2542724615423056.51708984
#Sta/Elev= 27
       0   73.55     .92   72.77    1.96   71.65    6.24   65.75    6.41   65.55
    6.43   65.53     8.8   64.51   12.38   63.36   13.09   62.96   14.63   62.72
   19.98   61.66   23.71   60.99   24.93   60.78   25.42   60.57   26.76  61.098
   28.16   61.44   31.29   61.62   34.35   61.79   37.47   62.08   43.55   62.52
   49.17   65.78   49.76   65.99   52.53   67.85   63.56   76.35   64.04   76.68
   64.62   77.08    66.1    77.9
#Mann= 3 , 0 , 0
       0     .06       0   23.71     .04       0   26.76     .05       0
Bank Sta=23.71,26.76
XS Rating Curve= 0 ,0
Exp/Cntr=0.3,0.1

Type RM Length L Ch R = 1 ,1214.13 ,15.14,13.55,13.08
XS GIS Cut Line= 3
344397.2103271485423117.85131836344450.7780761725423071.59112549
344453.648925781 5423060.8928833
#Sta/Elev= 27
       0   72.62    1.41   71.41    1.91   71.05    4.58   67.41     4.8   67.15
    7.92      65    8.39   64.68   12.07   63.56   13.04    63.1   24.19   61.01
   28.06   60.12   31.45   60.02   34.11   59.93   39.34   59.55   41.92   60.24
   42.35   60.32   43.05   60.58   44.72   62.02    45.8   62.84   46.96   63.85
   62.78   75.87   66.65   78.75   66.92   78.84   68.74   79.13   70.78   79.22
   71.26   79.25   81.85   80.38
#Mann= 3 , 0 , 0
       0     .06       0   34.11     .04       0   41.92     .05       0
Bank Sta=34.11,41.92
XS Rating Curve= 0 ,0
Exp/Cntr=0.3,0.1

Type RM Length L Ch R = 1 ,1200.58 ,17.09,17.6,17.74
XS GIS Cut Line= 2
344411.0806884775423127.57507324344455.4373168955423082.21032715
#Sta/Elev= 21
       0      71    6.14   66.79    6.66   66.45    9.87   65.27   11.64   64.61
   13.48    63.9   14.28   63.37   23.37   61.46   32.31   59.35    33.2   59.14
   34.93    58.9   36.39   59.54    36.9   59.72   39.18    60.5    39.3   60.53
   39.37   60.58    49.2   67.86   55.77   72.31   57.53   73.62   61.02    76.2
   63.45   77.88
#Mann= 3 , 0 , 0
       0     .06       0   32.31     .04       0    36.9     .05       0
Bank Sta=32.31,36.9
XS Rating Curve= 0 ,0
Exp/Cntr=0.3,0.1

Type RM Length L Ch R = 1 ,1182.98 ,17.91,16.97,16.65
XS GIS Cut Line= 3
344423.7293090825423137.27148438344451.4520874025423111.64550781
344464.7937011725423091.56030273
#Sta/Elev= 19
       0   72.88     .27   72.75    3.83   70.16    6.97   68.27    9.54   66.38
    13.4   63.45   15.34   62.34   25.65    60.4   31.25   59.27   33.78   58.59
   35.02   58.98   35.24   59.06   37.75   59.94   37.84   59.97      44   64.83
   47.57   67.31   51.05    69.3   59.62   75.23   61.86   76.83
#Mann= 3 , 0 , 0
       0     .06       0   31.25     .04       0   35.24     .05       0
Bank Sta=31.25,35.24
XS Rating Curve= 0 ,0
Exp/Cntr=0.3,0.1

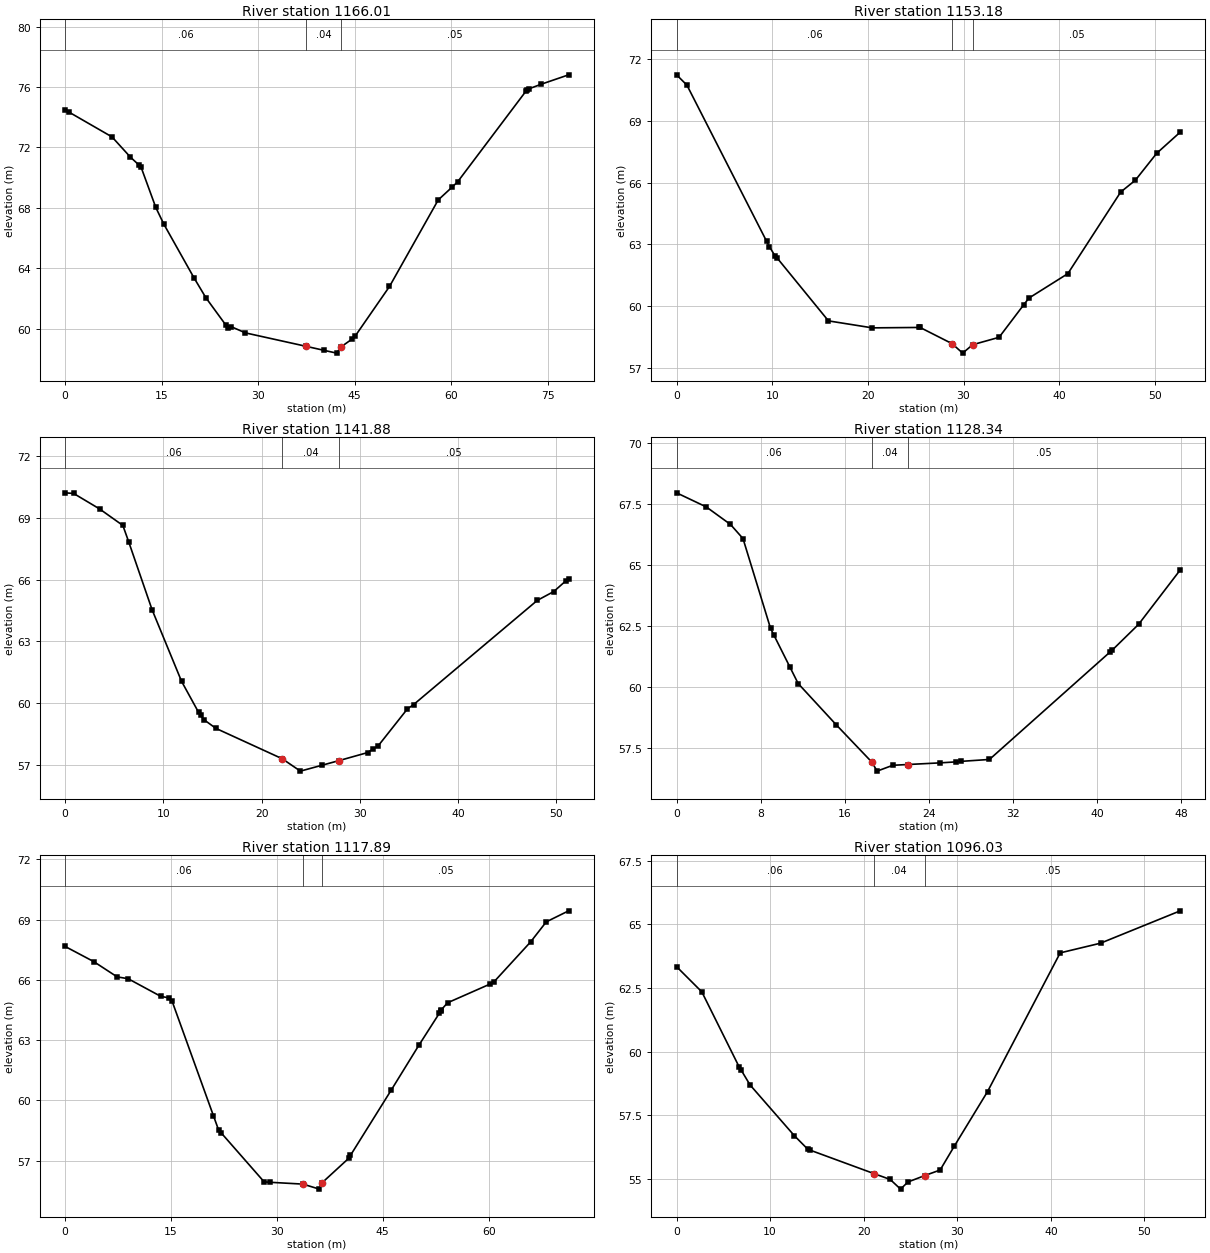
Type RM Length L Ch R = 1 ,1166.01 ,11.83,12.83,13.49
XS GIS Cut Line= 3
344434.7974853525423155.41571045344474.6513061525423110.34112549
344474.8782958985423092.27392578
#Sta/Elev= 29
       0   74.51     .63   74.34    7.31    72.7   10.15   71.37   11.57   70.81
   11.82    70.7   14.11   68.03   15.34   66.94   20.02   63.39    21.9   62.05
      25   60.24   25.33   60.08   25.77   60.15   28.03   59.73   37.46   58.84
   40.29   58.57   42.21   58.39   42.81   58.78   44.66   59.34    45.1   59.53
   50.41    62.8   57.98   68.53   60.17   69.39      61   69.73   71.68   75.77
   71.77   75.79   72.05   75.88   73.99   76.19   78.24   76.81
#Mann= 3 , 0 , 0
       0     .06       0   37.46     .04       0   42.81     .05       0
Bank Sta=37.46,42.81
XS Rating Curve= 0 ,0
Exp/Cntr=0.3,0.1

Type RM Length L Ch R = 1 ,1153.18 ,11.32,11.3,11.26
XS GIS Cut Line= 3
344448.679870605 5423154.2401123344475.5363159185423129.82611084
344483.6798706055423115.62792969
#Sta/Elev= 21
       0   71.25    1.08   70.75    9.42   63.14     9.7   62.89   10.27   62.45
    10.5   62.34   15.88   59.27   20.47   58.93   25.39   58.95   25.46   58.95
   28.81   58.16   29.91    57.7   30.96   58.11   33.72   58.47   36.29   60.05
   36.84   60.38   40.91   61.57   46.43   65.54   47.97   66.12    50.2   67.43
   52.66   68.46
#Mann= 3 , 0 , 0
       0     .06       0   28.81     .04       0   30.96     .05       0
Bank Sta=28.81,30.96
XS Rating Curve= 0 ,0
Exp/Cntr=0.3,0.1

Type RM Length L Ch R = 1 ,1141.88 ,13.01,13.54,14.12
XS GIS Cut Line= 2
344458.3828735355423160.81970215344496.1552734385423126.18988037
#Sta/Elev= 24
       0    70.2     .88   70.17    3.52   69.42    5.89   68.62    6.48   67.83
    8.86   64.54   11.86   61.07    13.6   59.56   13.81   59.43   14.11   59.22
   15.36   58.79    22.1   57.32   23.95   56.72   26.11      57   27.88   57.23
    30.8   57.62   31.36    57.8   31.84   57.93   34.83   59.73   35.46   59.94
   48.05   64.99   49.73   65.42   50.94   65.93   51.24   66.04
#Mann= 3 , 0 , 0
       0     .06       0    22.1     .04       0   27.88     .05       0
Bank Sta=22.1,27.88
XS Rating Curve= 0 ,0
Exp/Cntr=0.3,0.1

Type RM Length L Ch R = 1 ,1128.34 ,10.91,10.45,10
XS GIS Cut Line= 4
344467.3927001955423166.01409912344472.4174804695423164.97528076
344476.5759277345423161.16607666344505.8582763675423138.31048584
#Sta/Elev= 21
       0   67.97    2.83   67.39    5.13   66.67    6.32   66.09    8.94    62.4
    9.25   62.13   10.77   60.82   11.57   60.13    15.2   58.43   18.58    56.9
   19.08   56.53   20.57   56.77   22.01  56.802   25.08   56.87   26.58   56.91
   27.02   56.93   29.77   57.01    41.2   61.41   41.44    61.5   43.95   62.56
   47.92    64.8
#Mann= 3 , 0 , 0
       0     .06       0   18.58     .04       0   22.01     .05       0
Bank Sta=18.58,22.01
XS Rating Curve= 0 ,0
Exp/Cntr=0.3,0.1

Type RM Length L Ch R = 1 ,1117.89 ,21.15,21.85,22.43
XS GIS Cut Line= 3
344466.2083129885423171.84667969344479.6917114265423173.35028076
344522.9801025395423135.09832764
#Sta/Elev= 28
       0   67.67    4.08   66.91    7.39   66.15    8.94   66.06   13.57   65.18
    14.8    65.1   15.17   64.94   21.02   59.24   21.77   58.51    22.1   58.39
   28.21   55.94   29.08   55.92    33.7   55.83   36.03   55.58   36.43  55.903
   40.23   57.13   40.43   57.26    46.2   60.51   50.11   62.74   53.02   64.34
    53.2   64.46   53.27    64.5   54.18   64.86   60.25    65.8    60.8   65.92
   65.94   67.89   68.16   68.89   71.33   69.44
#Mann= 3 , 0 , 0
       0     .06       0    33.7     .04       0   36.43     .05       0
Bank Sta=33.7,36.43
XS Rating Curve= 0 ,0
Exp/Cntr=0.3,0.1

Type RM Length L Ch R = 1 ,1096.03 ,13.27,18.23,17.07
XS GIS Cut Line= 4
344487.350524902 5423190.1350708344499.8256835945423183.20928955
344512.4743041995423174.37872314344529.1080932625423156.89068604
#Sta/Elev= 19
       0   63.34     2.7   62.35    6.71   59.39    6.89   59.29    7.85    58.7
   12.58   56.71   14.04   56.17   14.27   56.14   21.09   55.22   22.83   54.99
   23.94   54.61   24.73   54.89   26.51   55.14   28.17   55.36   29.69    56.3
   33.24   58.44      41   63.88   45.31   64.26   53.83   65.53
#Mann= 3 , 0 , 0
       0     .06       0   21.09     .04       0   26.51     .05       0
Bank Sta=21.09,26.51
XS Rating Curve= 0 ,0
Exp/Cntr=0.3,0.1