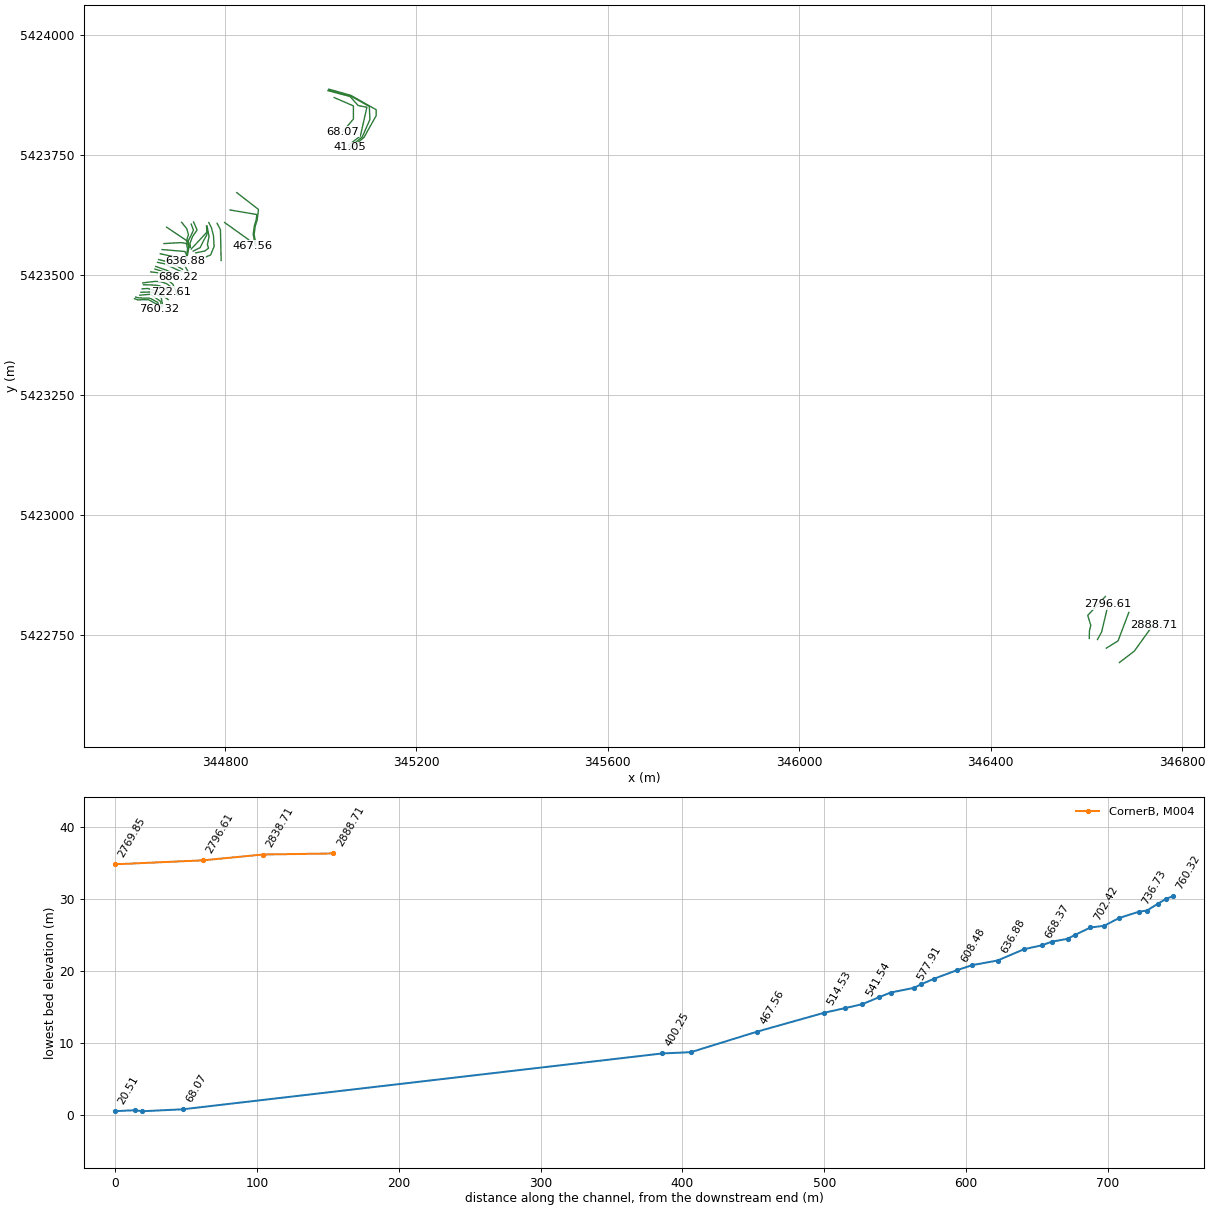
HEC-RAS study Corner_Brook2.prj: Corner_Brook2

--- Corner_Brook2.g02 (geometry) --- (continued)

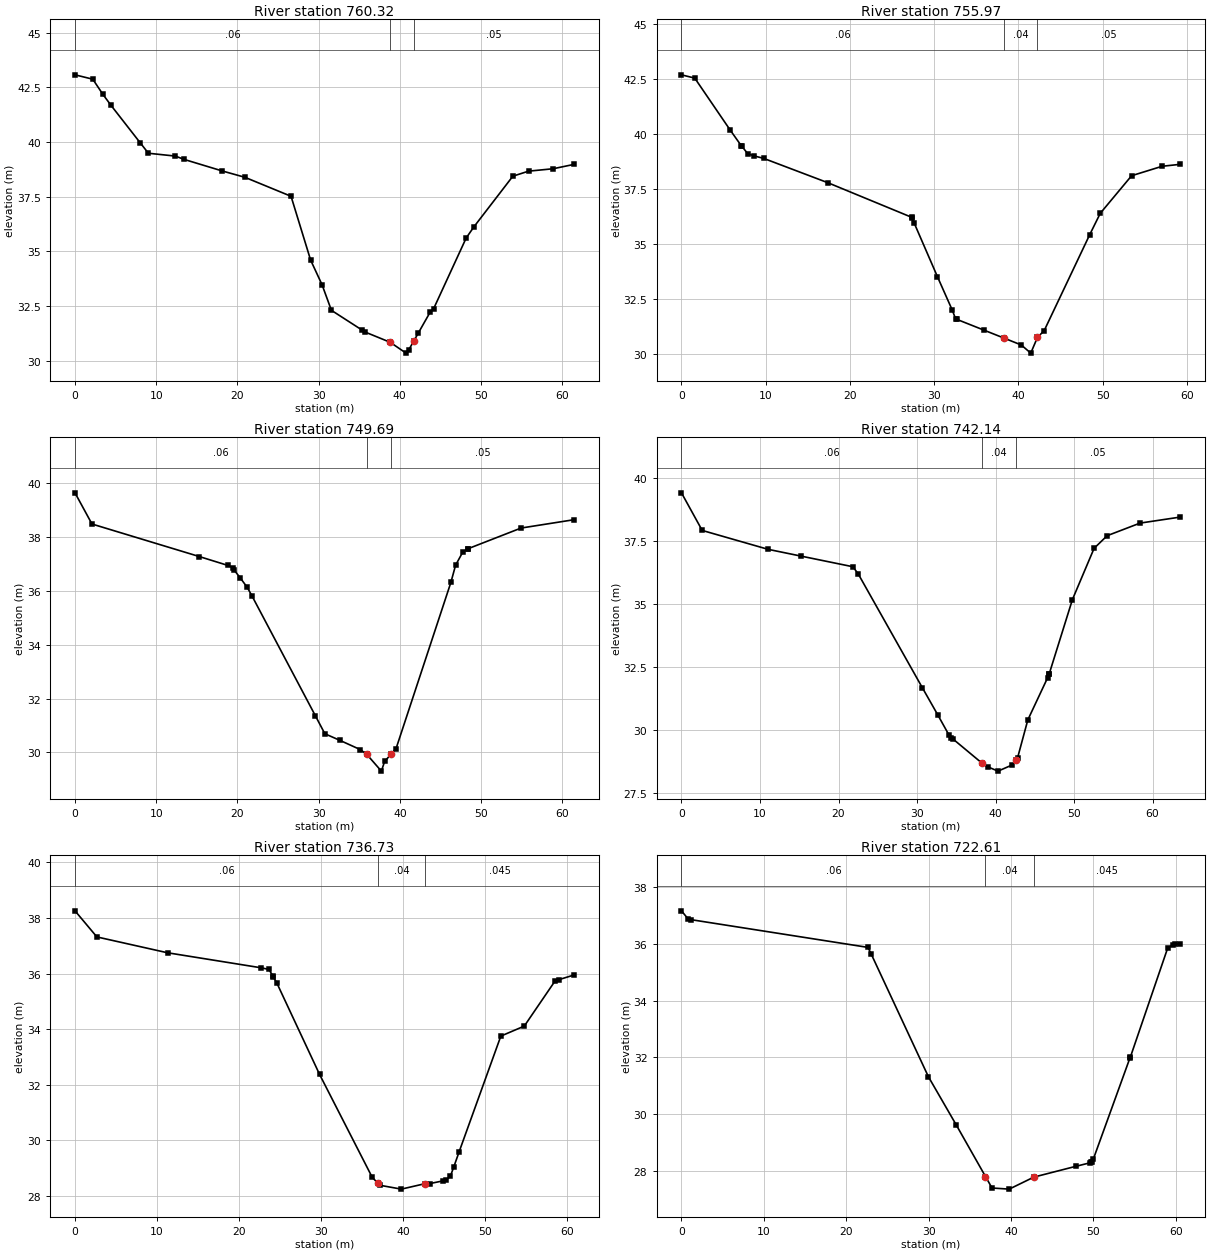
Type RM Length L Ch R = 1 ,760.32  ,4.45,4.35,4.33
XS GIS Cut Line= 6
344610.9622802735423450.17810059344618.5858764655423447.58087158
344628.6354980475423448.27349854     344640.93755423447.92712402
 344657.224670415423438.75030518344663.2891235355423428.01507568
#Sta/Elev= 29
       0   43.08    2.19   42.88    3.43   42.19    4.42   41.69    8.05   39.96
    9.04   39.49   12.37   39.36   13.42   39.21   18.13   38.68   20.92   38.39
   26.61   37.52   29.02    34.6   30.43   33.47   31.58    32.3   35.38   31.39
    35.7   31.31   38.83  30.835   40.77   30.34   41.11   30.49    41.7  30.877
   42.28  31.257   43.72    32.2   44.18   32.38   48.18   35.61   49.13   36.12
   53.93   38.44   55.86   38.67   58.88   38.78   61.46   38.98
#Mann= 3 , 0 , 0
       0     .06       0   38.83     .04       0    41.7     .05       0
Bank Sta=38.83,41.7
XS Rating Curve= 0 ,0
Exp/Cntr=0.3,0.1

Type RM Length L Ch R = 1 ,755.97  ,6.93,6.28,5.82
XS GIS Cut Line= 6
344613.3878784185423453.64111328344618.9324951175423452.08270264
344630.5415039065423451.39007568344643.5364990235423451.39007568
344659.3038940435423442.55950928344663.6356811525423432.69012451
#Sta/Elev= 27
       0   42.71    1.58   42.56    5.76   40.21    7.11   39.48    7.19   39.45
    7.87   39.12    8.64   39.02    9.75   38.91   17.39    37.8   27.32   36.23
   27.35   36.19   27.62   35.97   30.38   33.53   32.14   32.01   32.53   31.62
   32.66   31.59   35.88    31.1   38.27  30.736   40.34   30.42   41.46   30.05
   42.26   30.77   43.05   31.07   48.46   35.44   49.71   36.41   53.43   38.12
   57.05   38.55   59.23   38.64
#Mann= 3 , 0 , 0
       0     .06       0   38.27     .04       0   42.26     .05       0
Bank Sta=38.27,42.26
XS Rating Curve= 0 ,0
Exp/Cntr=0.3,0.1

Type RM Length L Ch R = 1 ,749.69  ,6.48,7.55,8.4
XS GIS Cut Line= 6
344622.0639038095423457.50012207344637.3115234385423458.88531494
344643.2026977545423459.40472412344650.4799194345423455.24908447
344665.7274780275423444.34069824344667.4600830085423431.35467529
#Sta/Elev= 25
       0   39.65    2.09   38.49   15.31   37.28   18.83   36.95   19.51   36.86
   19.62   36.77   20.34   36.49   21.22   36.13   21.77   35.83    29.6   31.36
   30.77   30.69   32.58   30.45   35.14    30.1   35.94   29.92   37.73    29.3
   38.13   29.66   38.92  29.929   39.54   30.14   46.29   36.32   46.87   36.96
   47.76   37.45   48.35   37.56   48.39   37.57   54.93   38.34   61.45   38.65
#Mann= 3 , 0 , 0
       0     .06       0   35.94     .04       0   38.92     .05       0
Bank Sta=35.94,38.92
XS Rating Curve= 0 ,0
Exp/Cntr=0.3,0.1

Type RM Length L Ch R = 1 ,742.14  ,6.02,5.42,4.95
XS GIS Cut Line= 6
344624.4896850595423463.56030273344639.7373046885423464.07971191
344647.0145263675423464.25292969344664.6879272465423454.72967529
344667.1135253915423451.26672363344670.0590820315423434.81750488
#Sta/Elev= 26
       0   39.41    2.64   37.92   11.04   37.17   15.26    36.9   21.84   36.48
   22.54   36.18   30.67   31.69   32.64   30.61   34.09    29.8   34.39    29.7
   34.63   29.64   38.26    28.7   39.01   28.55   40.32   28.38   42.08   28.62
   42.61   28.81    42.8    28.9   44.11   30.41   46.63   32.08    46.8   32.21
   46.84   32.24   49.79   35.18   52.55   37.21   54.21   37.71    58.4   38.21
   63.55   38.45
#Mann= 3 , 0 , 0
       0     .06       0   38.26     .04       0   42.61     .05       0
Bank Sta=38.26,42.61
XS Rating Curve= 0 ,0
Exp/Cntr=0.3,0.1

Type RM Length L Ch R = 1 ,736.73  ,13.29,14.13,15.08
XS GIS Cut Line= 4
344627.0886840825423470.83251953344638.3510742195423471.52508545
344656.1976928715423466.50372314344681.3214721685423448.32312012
#Sta/Elev= 25
       0   38.26    2.67   37.32   11.28   36.75   22.67   36.21   23.65   36.15
   24.11   35.92   24.18   35.88   24.61   35.66   29.82   32.37   36.23   28.67
   36.93   28.45   37.15   28.38   39.79   28.24   42.73   28.44   43.27   28.44
   44.91   28.54   45.28   28.58   45.76    28.7   46.16   29.02   46.83   29.58
   51.92   33.75   54.78   34.11   58.52   35.73   58.98   35.78   60.84   35.95
#Mann= 3 , 0 , 0
       0     .06       0   36.93     .04       0   42.73    .045       0
Bank Sta=36.93,42.73
XS Rating Curve= 0 ,0
Exp/Cntr=0.3,0.1

Type RM Length L Ch R = 1 ,722.61  ,9.42,10.56,11.32
XS GIS Cut Line= 4
344629.6876831055423479.31671143344652.7322998055423478.62408447
344662.9550781255423477.23907471344686.8660888675423464.25292969
#Sta/Elev= 22
       0   37.17     .82   36.88    1.12   36.86   22.64   35.88   23.06   35.63
   29.99   31.31   33.37   29.61   36.91  27.795    37.7   27.39   39.79   27.35
   42.78  27.774   47.95   28.16   49.62   28.28   49.74   28.29   49.88    28.3
   49.99    28.4   54.46   31.99    54.5   32.01   59.02   35.85   59.69   35.98
   59.87   35.99   60.58   36.01
#Mann= 3 , 0 , 0
       0     .06       0   36.91     .04       0   42.78    .045       0
Bank Sta=36.91,42.78
XS Rating Curve= 0 ,0
Exp/Cntr=0.3,0.1

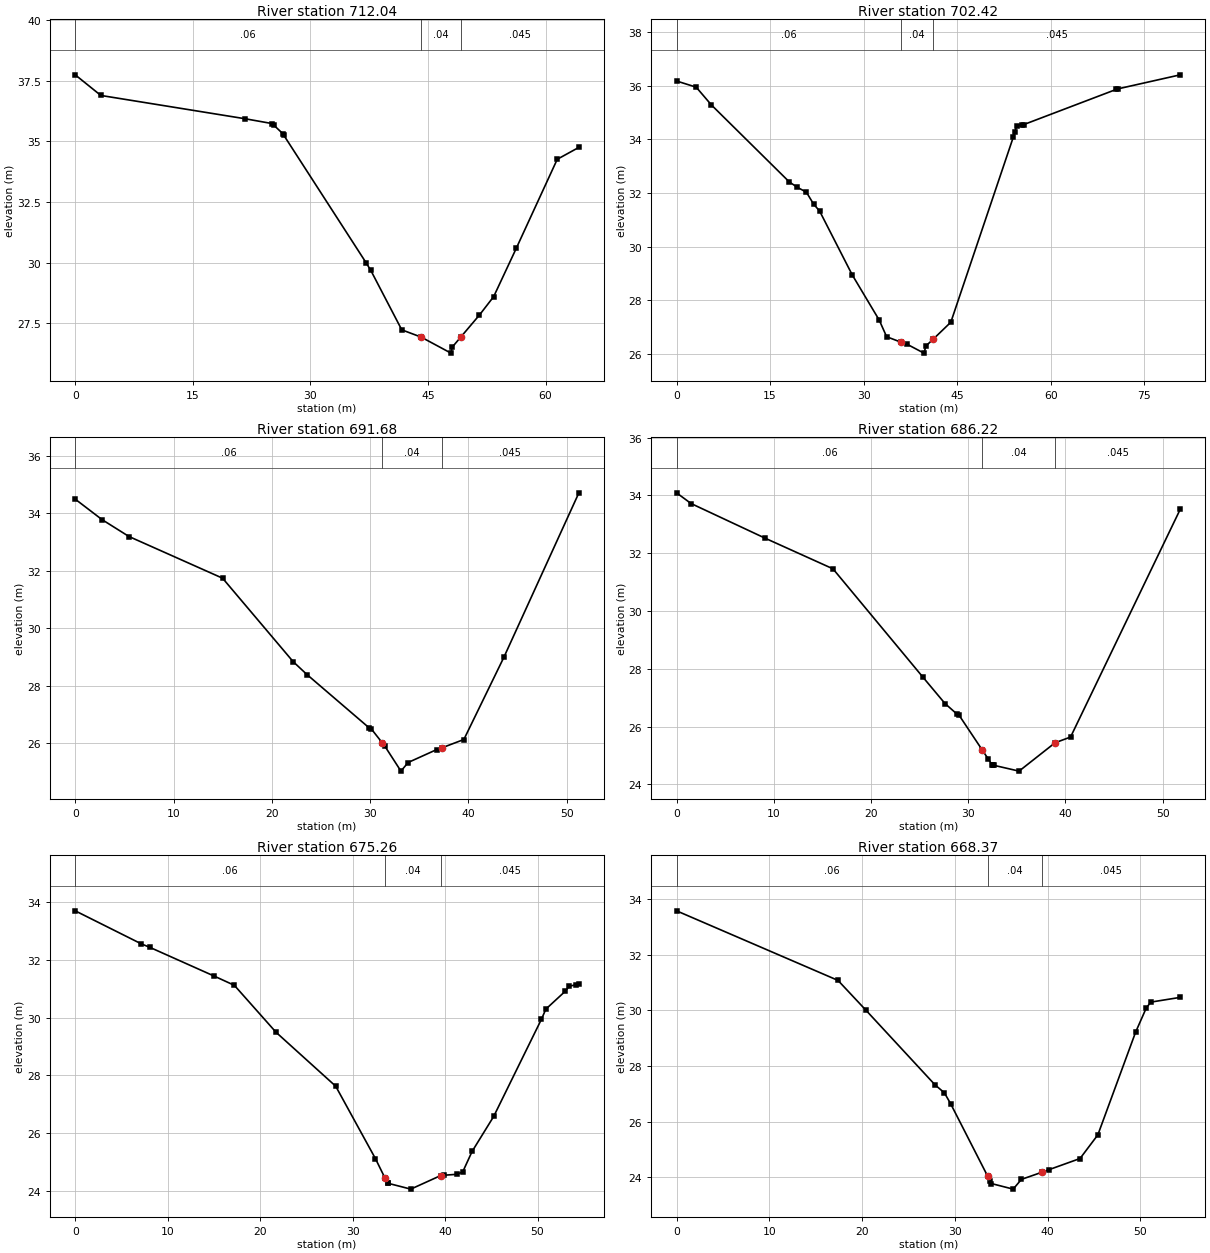
Type RM Length L Ch R = 1 ,712.04  ,12.16,9.62,7.82
XS GIS Cut Line= 5
344628.3016967775423483.12609863344653.4254760745423486.24267578
344665.2077026375423485.89648438344678.8958740235423481.22149658
344688.7720947275423473.25653076
#Sta/Elev= 19
       0   37.74    3.27   36.89   21.67   35.93   25.14   35.73   25.32   35.67
   26.47   35.32   26.61   35.25    37.1      30   37.71   29.68   41.66   27.23
   44.14   26.93   47.94   26.27   48.08   26.51   49.16   26.92   51.57   27.84
   53.39    28.6   56.27   30.59    61.5   34.26   64.26   34.75
#Mann= 3 , 0 , 0
       0     .06       0   44.14     .04       0   49.16    .045       0
Bank Sta=44.14,49.16
XS Rating Curve= 0 ,0
Exp/Cntr=0.3,0.1

Type RM Length L Ch R = 1 ,702.42  ,9.35,10.74,11.82
XS GIS Cut Line= 4
344644.978088379 5423506.1138916344664.2185058595423503.77630615
344691.3189086915423480.11047363344701.4177246095423456.81347656
#Sta/Elev= 25
       0   36.17    3.15   35.94    5.58   35.28   18.09   32.41   19.38   32.21
   20.82   32.03   21.96   31.59   22.93   31.33   28.17   28.95   32.49   27.27
   33.68   26.65   35.95   26.45   36.96   26.37   39.66   26.04   39.99   26.31
   41.19   26.57   43.97   27.19      54   34.09   54.22   34.26   54.55   34.51
   55.36   34.55   55.69   34.55   70.52   35.86    70.8   35.88   80.75    36.4
#Mann= 3 , 0 , 0
       0     .06       0   35.95     .04       0   41.19    .045       0
Bank Sta=35.95,41.19
XS Rating Curve= 0 ,0
Exp/Cntr=0.3,0.1

Type RM Length L Ch R = 1 ,691.68  ,5.19,5.46,5.76
XS GIS Cut Line= 3
344653.627319336 5423511.9519043344676.1520996095423505.02587891
344699.8898925785423490.82788086
#Sta/Elev= 17
       0   34.49    2.72   33.78    5.47   33.19   14.99   31.74   22.16   28.84
   23.57   28.39   29.88   26.54   30.09   26.51   31.24   26.01   31.47   25.91
   33.13   25.03   33.86   25.33   36.77   25.78   37.29   25.84   39.53   26.13
    43.6   28.99   51.23   34.71
#Mann= 3 , 0 , 0
       0     .06       0   31.24     .04       0   37.29    .045       0
Bank Sta=31.24,37.29
XS Rating Curve= 0 ,0
Exp/Cntr=0.3,0.1

Type RM Length L Ch R = 1 ,686.22  ,10.65,10.96,11.43
XS GIS Cut Line= 3
344655.3601074225423517.49267578344679.2708740235423509.00848389
344702.4888916025423496.36853027
#Sta/Elev= 17
       0   34.09    1.49   33.72    9.11   32.52   16.09   31.46   25.37    27.7
   27.61    26.8   28.89   26.42   29.07   26.39   31.47  25.178   32.08   24.87
   32.49   24.66   32.57   24.66   32.66   24.66   35.23   24.46   38.93   25.44
   40.53   25.64   51.81   33.52
#Mann= 3 , 0 , 0
       0     .06       0   31.47     .04       0   38.93    .045       0
Bank Sta=31.47,38.93
XS Rating Curve= 0 ,0
Exp/Cntr=0.3,0.1

Type RM Length L Ch R = 1 ,675.26  ,6.79,6.88,6.51
XS GIS Cut Line= 3
344658.9987182625423525.97692871344673.726501465 5423523.0335083
344709.4196777345423506.23809814
#Sta/Elev= 24
       0   33.68    7.15   32.54    8.07   32.42   15.02   31.43   17.21   31.11
   21.72   29.49   28.17   27.63   32.47   25.13    33.5  24.462   33.78   24.28
   33.85   24.28   36.29   24.08   39.54   24.55    39.9   24.56   41.24   24.59
    41.9   24.67   42.92   25.38   45.26   26.59   50.42   29.94    50.9   30.29
   53.01   30.91   53.42   31.08   54.18   31.13   54.47   31.14
#Mann= 3 , 0 , 0
       0     .06       0    33.5     .04       0   39.54    .045       0
Bank Sta=33.5,39.54
XS Rating Curve= 0 ,0
Exp/Cntr=0.3,0.1

Type RM Length L Ch R = 1 ,668.37  ,13.39,12.92,12.63
XS GIS Cut Line= 4
344661.4244995125423531.86407471344681.176879883 5423526.8427124
344699.1967163095423518.70471191344711.3255004885423511.43249512
#Sta/Elev= 19
       0   33.58    17.4   31.08   20.38   30.02   27.85   27.33   28.87   27.04
   29.54   26.65   33.52  24.053   33.77   23.89   33.94   23.78   36.28   23.58
   37.17   23.93   39.41   24.19   40.15   24.28   43.49   24.68   45.41   25.53
   49.48   29.22   50.63   30.09   51.12    30.3   54.29   30.47
#Mann= 3 , 0 , 0
       0     .06       0   33.52     .04       0   39.41    .045       0
Bank Sta=33.52,39.41
XS Rating Curve= 0 ,0
Exp/Cntr=0.3,0.1

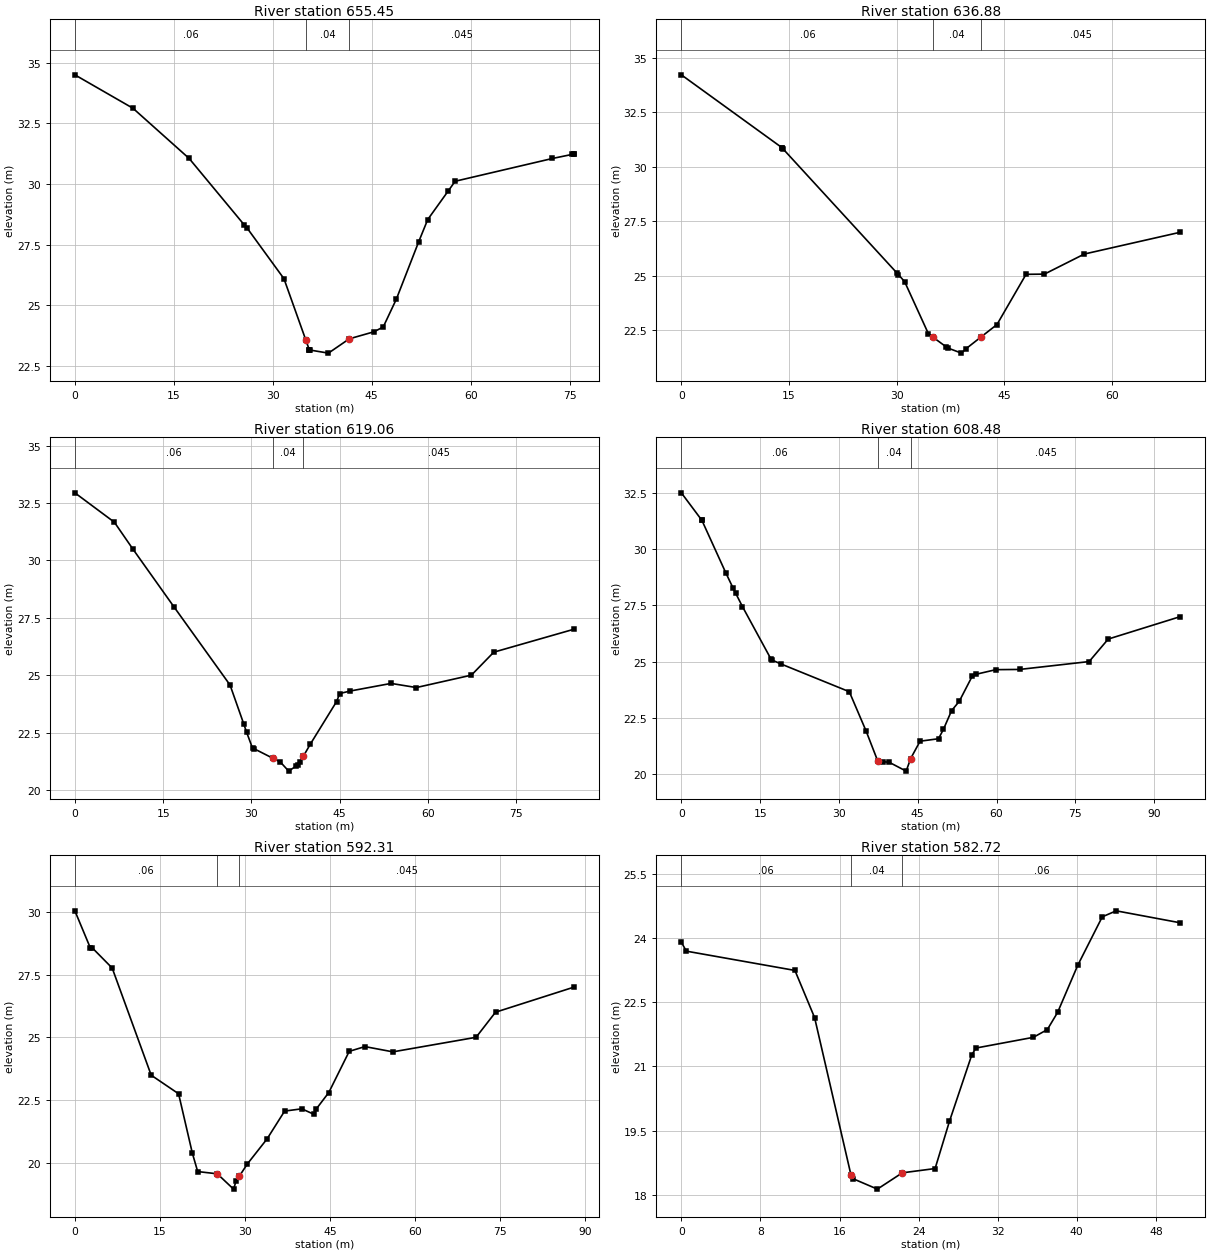
Type RM Length L Ch R = 1 ,655.45  ,16.35,18.57,21.74
XS GIS Cut Line= 4
344664.9114990235423543.94927979344689.9675292975423538.37432861
344712.8703002935423525.14770508344724.0916748055423504.46069336
#Sta/Elev= 23
       0    34.5    8.81   33.12   17.32   31.05   25.67   28.31   26.05    28.2
   31.69   26.09   35.02  23.547   35.54   23.15   35.54   23.14   35.58   23.15
   38.43   23.02   41.59   23.61   45.33    23.9   46.74    24.1   48.73   25.25
   52.12   27.62   53.48   28.53   56.56    29.7   57.64   30.11   72.39   31.05
   75.42   31.22   75.61   31.24   75.65   31.25
#Mann= 3 , 0 , 0
       0     .06       0   35.02     .04       0   41.59    .045       0
Bank Sta=35.02,41.59
XS Rating Curve= 0 ,0
Exp/Cntr=0.3,0.1

Type RM Length L Ch R = 1 ,636.88  ,17.22,17.82,17.39
XS GIS Cut Line= 5
      344668.528     5423552.642      344679.042     5423551.849
      344716.376      5423548.58      344719.838     5423541.659
       344717.77     5423528.044
#Sta/Elev= 19
       0   34.21   14.03   30.87   14.04   30.86   14.13   30.83   29.98   25.15
   30.24   25.06   31.11   24.73   34.43   22.34   35.11  22.176   36.84   21.76
   37.08    21.7   39.02   21.46   39.69   21.67   41.75    22.2   43.97   22.77
   48.02   25.07   50.58   25.08   56.14      26   69.53      27
#Mann= 3 , 0 , 0
       0     .06       0   35.11     .04       0   41.75    .045       0
Bank Sta=35.11,41.75
XS Rating Curve= 0 ,0
Exp/Cntr=0.3,0.1

Type RM Length L Ch R = 1 ,619.06  ,13.53,10.59,7.5
XS GIS Cut Line= 6
      344672.687     5423565.109      344707.514     5423567.186
      344719.296     5423565.455      344721.895     5423554.547
      344720.211     5423541.042      344718.217     5423528.029
#Sta/Elev= 25
       0   32.94    6.71   31.66    9.83    30.5    16.9   27.95   26.36   24.57
   28.71   22.86   29.18   22.51   30.19   21.81   30.49   21.79   33.64   21.38
   34.89   21.22   36.33   20.82   37.57   21.04   37.93   21.07   38.28   21.23
   38.83  21.475   40.01      22   44.46   23.85      45    24.2    46.8   24.31
   53.72   24.64   58.01   24.46   67.36      25   71.16      26   84.79      27
#Mann= 3 , 0 , 0
       0     .06       0   33.64     .04       0   38.83    .045       0
Bank Sta=33.64,38.83
XS Rating Curve= 0 ,0
Exp/Cntr=0.3,0.1

Type RM Length L Ch R = 1 ,608.48  ,19.38,16.17,7
XS GIS Cut Line= 6
      344677.992     5423599.323      344719.493     5423571.641
      344724.268     5423557.956      344721.134     5423544.957
      344720.396     5423540.345       344718.66     5423527.883
#Sta/Elev= 29
       0    32.5    3.84    31.3    3.87    31.3    8.51   28.92    9.86   28.26
   10.31   28.05   11.64   27.44   17.02   25.13   17.23   25.07      19   24.89
   31.97   23.66   35.17   21.91   37.38   20.58   38.42   20.55   39.59   20.52
   42.79   20.13   43.65   20.69   45.44   21.46   48.95   21.57   49.89   21.99
   51.44   22.82   52.89   23.23   55.39   24.36      56   24.43   59.87   24.64
   64.38   24.65   77.62      25   81.25      26      95      27
#Mann= 3 , 0 , 0
       0     .06       0   37.38     .04       0   43.65    .045       0
Bank Sta=37.38,43.65
XS Rating Curve= 0 ,0
Exp/Cntr=0.3,0.1

Type RM Length L Ch R = 1 ,592.31  ,13.08,9.58,7.18
XS GIS Cut Line= 6
       344709.42     5423609.608      344720.336     5423595.929
      344723.801     5423583.462      344720.509     5423574.459
      344725.014     5423559.048      344719.064     5423527.701
#Sta/Elev= 25
       0   30.04    2.73   28.56    3.04   28.57    6.58   27.76   13.46   23.49
   18.29   22.75   20.72   20.38   21.66   19.65   25.12   19.56   27.98   18.95
   28.43   19.27   29.03  19.476   30.44   19.96   33.89   20.95   36.99   22.06
   40.02   22.15   42.17   21.93   42.59   22.15   44.78    22.8   48.38   24.44
   51.15   24.63   56.08   24.42   70.75      25   74.18      26   88.02      27
#Mann= 3 , 0 , 0
       0     .06       0   25.12     .04       0   29.03    .045       0
Bank Sta=25.12,29.03
XS Rating Curve= 0 ,0
Exp/Cntr=0.3,0.1

Type RM Length L Ch R = 1 ,582.72  ,5.75,4.83,4.18
XS GIS Cut Line= 6
344729.5186767585423605.62530518344734.1968994145423592.98547363
344728.8255004885423581.55767822344723.9741210945423572.38067627
344723.2808837895423568.57147217344726.2265014655423558.87530518
#Sta/Elev= 19
       0    23.9      .5   23.69   11.49   23.24   13.48   22.14   17.16   18.47
    17.4   18.38   19.83   18.14   22.35   18.52   25.67   18.62   27.12   19.72
   29.38   21.27    29.8   21.43   35.61   21.68   37.02   21.86   38.06   22.26
    40.1   23.36   42.58   24.49   43.99   24.63   50.49   24.35
#Mann= 3 , 0 , 0
       0     .06       0   17.16     .04       0   22.35     .06       0
Bank Sta=17.16,22.35
XS Rating Curve= 0 ,0
Exp/Cntr=0.3,0.1

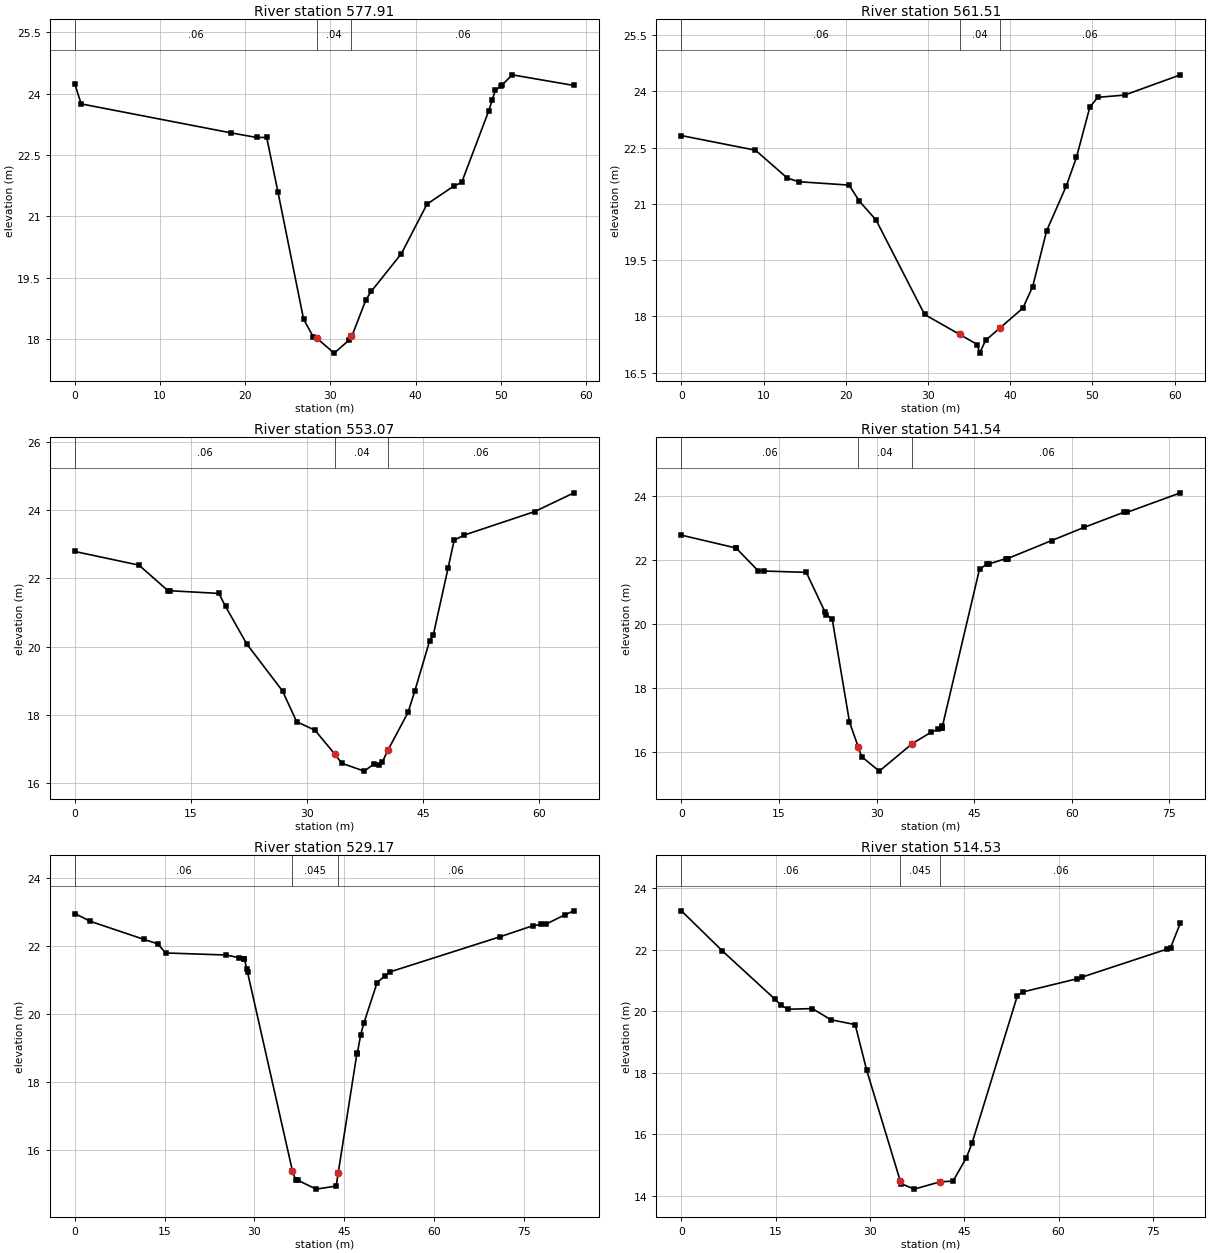
Type RM Length L Ch R = 1 ,577.91  ,17.27,16.39,15.08
XS GIS Cut Line= 5
344734.3701171885423610.30029297344741.8206787115423593.50488281
344732.4641113285423579.99932861344726.9196777345423565.80108643
344727.9592895515423557.31689453
#Sta/Elev= 26
       0   24.23     .74   23.75   18.37   23.04   21.33   22.93   22.52   22.93
   23.85   21.59   26.85   18.49   27.98   18.06   28.43   18.02   30.44   17.66
   32.15   17.97   32.47   18.07   32.55   18.09   34.18   18.97    34.8   19.17
   38.33   20.09   41.34    21.3   44.47   21.74   45.41   21.83   48.57   23.57
   48.99   23.84   49.36   24.08   50.05   24.19   50.11    24.2   51.33   24.46
   58.59    24.2
#Mann= 3 , 0 , 0
       0     .06       0   28.43     .04       0   32.47     .06       0
Bank Sta=28.43,32.47
XS Rating Curve= 0 ,0
Exp/Cntr=0.3,0.1

Type RM Length L Ch R = 1 ,561.51  ,6.39,8.44,10.26
XS GIS Cut Line= 3
344761.5350952155423601.67852783344762.1672973635423588.82788086
344729.5651245125423553.82312012
#Sta/Elev= 22
       0   22.82    9.01   22.43   12.87   21.69   14.26   21.59    20.4    21.5
   21.65   21.07   23.67   20.57   29.58   18.05   33.84   17.52   35.99   17.25
   36.28   17.02   36.99   17.36   38.69   17.68   41.53   18.22   42.72   18.79
   44.42   20.28   46.82   21.48   48.05   22.24   49.68   23.58   50.64   23.84
   53.91    23.9    60.7   24.44
#Mann= 3 , 0 , 0
       0     .06       0   33.84     .04       0   38.69     .06       0
Bank Sta=33.84,38.69
XS Rating Curve= 0 ,0
Exp/Cntr=0.3,0.1

Type RM Length L Ch R = 1 ,553.07  ,8.06,11.53,13.46
XS GIS Cut Line= 6
344761.9196777345423601.29669189344763.6522827155423589.17608643
344761.5731201175423582.25030518 344754.642517095423569.95672607
344748.2315063485423556.79748535344733.6771240235423549.52508545
#Sta/Elev= 27
       0   22.79    8.28   22.39   12.04   21.64   12.24   21.64   18.61   21.56
   19.47   21.18   22.21   20.08   26.84    18.7   28.66    17.8   31.03   17.55
   33.59   16.85    33.6   16.84   34.51   16.58   37.39   16.35   38.61   16.55
   39.25   16.54   39.72   16.61   40.47   16.97   43.06   18.07   43.92   18.69
   45.85   20.17   46.31   20.33   48.23    22.3   49.02   23.12   50.31   23.27
   59.43   23.96    64.5   24.51
#Mann= 3 , 0 , 0
       0     .06       0    33.6     .04       0   40.47     .06       0
Bank Sta=33.6,40.47
XS Rating Curve= 0 ,0
Exp/Cntr=0.3,0.1

Type RM Length L Ch R = 1 ,541.54  ,10.36,12.37,14.02
XS GIS Cut Line= 6
344762.612670898 5423601.6428833 344766.771301275423579.99932861
344763.3059082035423563.03088379344765.7316894535423555.58532715
344758.1079101565423549.69830322344738.7019042975423545.71588135
#Sta/Elev= 30
       0   22.77    8.38   22.37     8.4   22.37   11.78   21.66   12.76   21.65
   19.19   21.61    22.1   20.36   22.25   20.29   23.17   20.16   25.83   16.94
   27.17  16.166    27.7   15.86   30.41   15.41   35.49   16.27   38.34   16.62
   39.41   16.71   40.01   16.75   40.04   16.75   40.11   16.81   45.81   21.71
   46.93   21.86   47.25   21.87   49.88   22.04   50.04   22.04   50.13   22.04
   56.88    22.6   61.86   23.01   67.95   23.48   68.46   23.48   76.69   24.09
#Mann= 3 , 0 , 0
       0     .06       0   27.17     .04       0   35.49     .06       0
Bank Sta=27.17,35.49
XS Rating Curve= 0 ,0
Exp/Cntr=0.3,0.1

Type RM Length L Ch R = 1 ,529.17  ,14.76,14.64,14.39
XS GIS Cut Line= 6
344766.251281738 5423608.9151001344771.6226806645423598.69927979
344775.954284668 5423582.0770874344777.3405151375423559.04827881
344769.8900756845423541.21411133344758.4542846685423536.71228027
#Sta/Elev= 30
       0   22.96     2.6   22.73   11.54    22.2   13.84   22.07   15.17    21.8
   25.26   21.74   27.44   21.66   28.29   21.63   28.34   21.62   28.72   21.33
   28.86   21.23   36.37   15.38   36.92   15.11   37.28   15.11   40.32   14.85
   43.67   14.94   44.01  15.322   47.12   18.82   47.21   18.85   47.78    19.4
   48.31   19.74   50.52   20.93   51.79   21.12   52.62   21.24   71.12   22.28
   76.51    22.6   77.96   22.64   78.76   22.65   81.98   22.93   83.41   23.04
#Mann= 3 , 0 , 0
       0     .06       0   36.37    .045       0   44.01     .06       0
Bank Sta=36.37,44.01
XS Rating Curve= 0 ,0
Exp/Cntr=0.3,0.1

Type RM Length L Ch R = 1 ,514.53  ,42.9,46.97,53.68
XS GIS Cut Line= 3
344783.4863281255423607.42108154344790.5899047855423594.30987549
344792.0429077155423529.85552979
#Sta/Elev= 23
       0   23.26     6.5   21.96   14.91   20.38   15.85   20.19   16.95   20.06
   20.83   20.08   23.76   19.72   27.64   19.56   29.48   18.07   34.82  14.471
   34.94   14.39   37.02   14.21   41.21   14.45   43.21   14.47   45.32   15.23
   46.22    15.7   53.44    20.5   54.27   20.62   62.92   21.05   63.66    21.1
   77.31   22.02    77.8   22.06   79.38   22.87
#Mann= 3 , 0 , 0
       0     .06       0   34.82    .045       0   41.21     .06       0
Bank Sta=34.82,41.21
XS Rating Curve= 0 ,0
Exp/Cntr=0.3,0.1

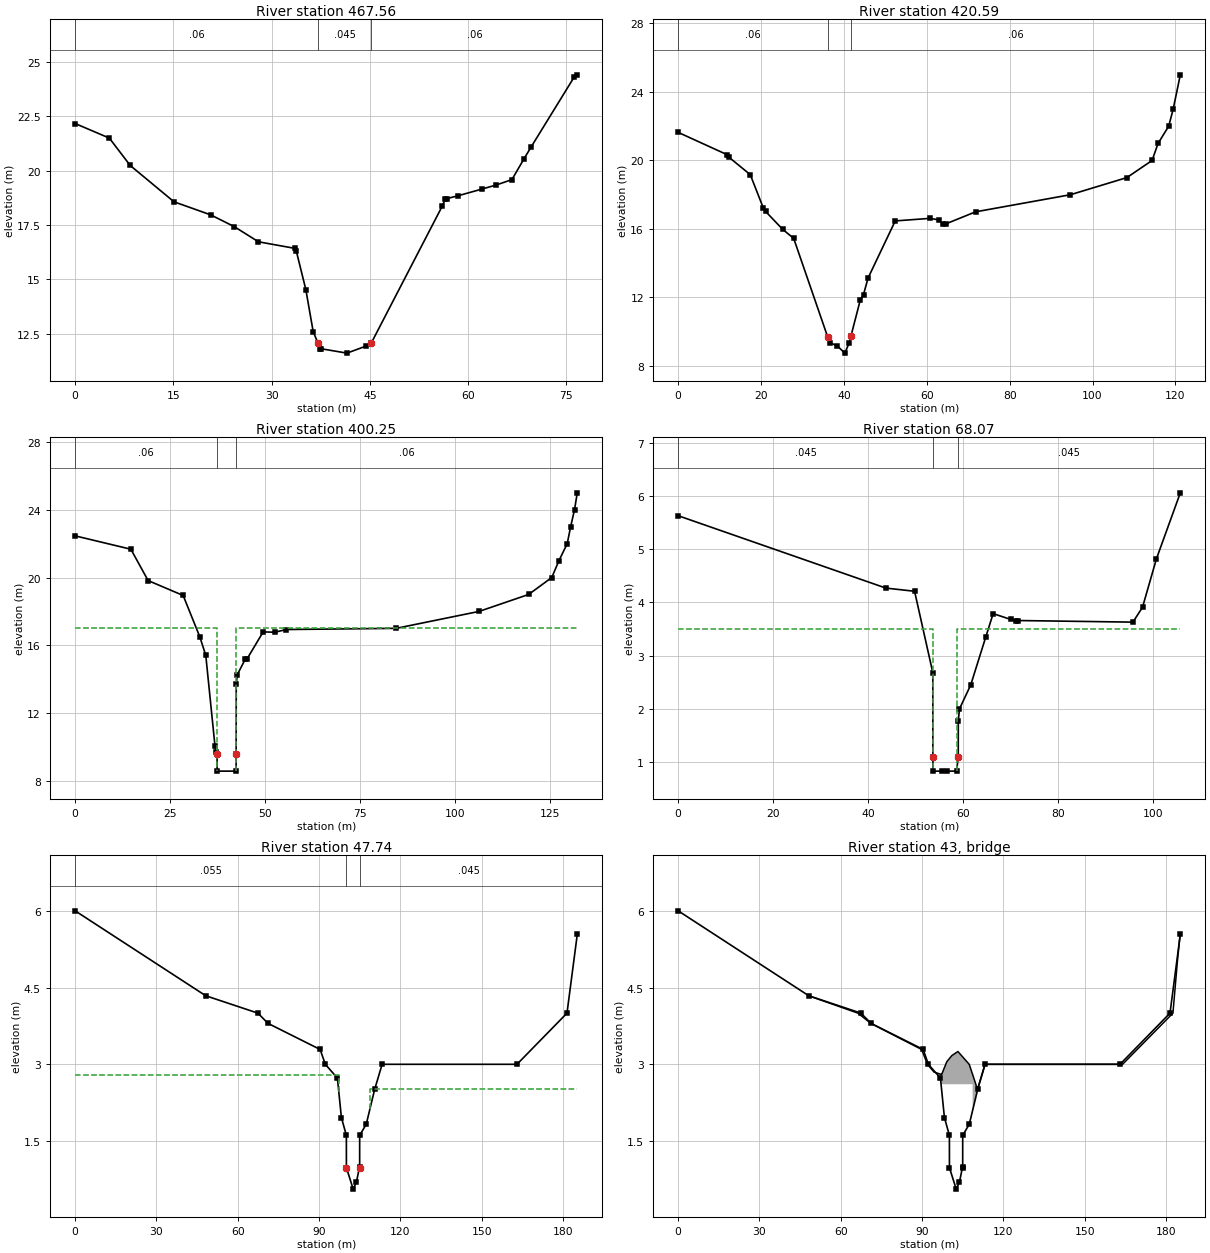
Type RM Length L Ch R = 1 ,467.56  ,45.12,46.97,48.91
XS GIS Cut Line= 3
344799.2758789065423609.05450439344849.7756958015423573.01531982
344857.0006713875423560.30133057
#Sta/Elev= 28
       0   22.17    5.22    21.5    8.41   20.24   15.09   18.57   20.69   17.97
   24.28   17.43   27.99   16.73   33.52   16.43   33.76   16.31   35.22   14.53
   36.34    12.6   37.06  12.078   37.43   11.81   37.58   11.81    41.5   11.61
   44.46   11.94   45.22   12.08   56.06   18.38   56.53   18.71   56.78   18.72
   58.48   18.85   62.04   19.15   64.25   19.34   66.68   19.59   68.53   20.55
   69.65   21.11   76.21   24.32   76.66   24.41
#Mann= 3 , 0 , 0
       0     .06       0   37.06    .045       0   45.22     .06       0
Bank Sta=37.06,45.22
XS Rating Curve= 0 ,0
Exp/Cntr=0.3,0.1

Type RM Length L Ch R = 1 ,420.59  ,21.99,20.34,18.45
Node Photo=..\..\..\..\Corner Brook\Windshield Survey\CB photos\P1000693.JPG
XS GIS Cut Line= 6
      344810.865     5423635.201      344866.616     5423625.711
      344865.268     5423614.426      344861.458     5423602.301
      344859.051     5423584.465      344863.363      5423562.32
#Sta/Elev= 30
       0   21.64   11.87   20.33   12.15   20.21    17.4   19.17   20.54   17.23
   21.11   17.02   25.21   15.98   27.88   15.45    36.1   9.682   36.59    9.37
   38.44    9.16   40.23    8.75   41.28    9.35   41.68    9.73   43.97   11.87
   44.73   12.17   45.82   13.13   52.39   16.47   60.82   16.62   62.83   16.53
   64.03   16.29   64.63    16.3   71.77      17   94.68      18   108.3      19
  114.38      20  115.83      21  118.39      22  119.47      23  121.19      25
#Mann= 3 , 0 , 0
       0     .06       0    36.1    .045       0   41.68     .06       0
Bank Sta=36.1,41.68
XS Rating Curve= 0 ,0
Exp/Cntr=0.3,0.1

Type RM Length L Ch R = 1 ,400.25  ,338,338,338
Node Photo=..\..\..\..\Corner Brook\Windshield Survey\CB photos\P1000692.JPG
XS GIS Cut Line= 6
      344824.718     5423671.386      344870.066     5423636.305
      344867.443     5423614.785      344863.372     5423601.656
      344860.966     5423584.273      344864.667     5423562.637
#Sta/Elev= 28
       0   22.46   14.68   21.67   19.22   19.82   28.45   18.94   32.87   16.48
   34.41    15.4   36.82   10.08   37.05    9.72   37.39    9.56    37.4    8.57
    42.4    8.57   42.41    9.56   42.43    13.7   42.68   14.25   44.79   15.17
   45.21   15.17   49.52   16.79   52.58   16.77   55.66   16.93   84.57      17
  106.41      18  119.45      19  125.54      20  127.44      21  129.61      22
  130.51      23  131.53      24  132.26      25
#Mann= 3 , 0 , 0
       0     .06       0   37.39    .045       0   42.41     .06       0
#XS Ineff= 2 , 0
       0    37.4      17    42.4       0      17
Permanent Ineff=
       F       F
Bank Sta=37.39,42.41
XS Rating Curve= 0 ,0
Exp/Cntr=0.5,0.3

Type RM Length L Ch R = 1 ,68.07   ,27.5,28.4,28.6
Node Photo=..\..\..\..\Corner Brook\Windshield Survey\CB photos\P1000646.JPG
XS GIS Cut Line= 5
345028.2824707035423869.57769775345068.4484863285423852.24151611
345068.4484863285423831.15710449345068.4484863285423824.75372314
345046.0264892585423798.47808838
#Sta/Elev= 22
       0    5.63   43.75    4.27    49.8    4.21   53.64    2.68   53.65     1.1
   53.66     .83   55.65     .83   56.58     .83   58.66     .83      59     1.1
   59.01    1.77   59.26       2   61.63    2.45   64.83    3.36   66.35    3.79
   70.08    3.68   71.24    3.66   71.68    3.66    95.8    3.63   97.82    3.91
  100.75    4.82  105.78    6.06
#Mann= 3 , 0 , 0
       0    .045       0   53.65    .035       0      59    .045       0
#XS Ineff= 2 , 0
       0   53.66     3.5   58.66       0     3.5
Permanent Ineff=
       F       F
Bank Sta=53.65,59
XS Rating Curve= 0 ,0
Exp/Cntr=0.5,0.3

Type RM Length L Ch R = 1 ,47.74   ,5.2,5.5,5.7
Node Photo=..\..\..\..\Corner Brook\Windshield Survey\CB photos\P1000644.JPG
XS GIS Cut Line= 6
      345015.284        5423884.       345061.38     5423871.775
      345078.464     5423852.934      345096.641     5423849.292
      345082.981     5423789.378      345058.179     5423770.541
#Sta/Elev= 21
       0       6   48.19    4.34   67.45       4   71.17     3.8   90.41    3.29
   92.32       3   96.78    2.73   98.25    1.96  100.09    1.61   100.1     .98
   102.6     .56  103.81      .7  104.96       1  104.99     .98     105    1.61
  107.43    1.83  110.53    2.51  113.28       3  163.05       3   181.5       4
   185.3    5.54
#Mann= 3 , 0 , 0
       0    .055       0   100.1    .035       0  104.99    .045       0
#XS Ineff= 2 , 0
       0   97.29     2.8  108.74       0    2.51
Permanent Ineff=
       F       F
Bank Sta=100.1,104.99
XS Rating Curve= 0 ,0
Exp/Cntr=0.5,0.3

Type RM Length L Ch R = 3 ,43      ,,,
Node Photo=..\..\..\..\Corner Brook\Windshield Survey\CB photos\P1000643.JPG
BEGIN DESCRIPTION:
Pedestrian Bridge (Structure 2114)
END DESCRIPTION:
Bridge Culvert--1,0,-1,-1, 0
Deck Dist Width WeirC Skew NumUp NumDn MinLoCord MaxHiCord MaxSubmerge Is_Ogee
1.9,1.36,1.67,0, 23, 19, 2.51, , 0.98, 0, 0,0,,
   48.12   66.33    71.1   89.84   91.99   94.37   97.22   97.23   99.12  100.98
  103.23   107.4  108.66  108.67  110.45  113.21  119.18  124.55  143.04  163.99
  182.58  184.21  185.23
    4.34       4     3.8    3.29       3    2.85     2.8     2.8    3.05    3.17
    3.25       3     2.8     2.8    2.51       3       3       3       3       3
       4       5    5.54
                                                      .5    2.61    2.61    2.61
    2.61    2.61    2.61      .5
                        
   47.69   48.46   66.95   96.99  101.83  101.84  103.73  107.84  110.09  111.99
  113.28  113.29  115.07  118.09  130.09   152.1  173.15   191.5  196.01
    4.74    4.74       4       3     2.8     2.8    3.05    3.25    3.18       3
     2.8     2.8    3.01       3       3       3       3       4    5.54
                                      .5    2.61    2.61    2.61    2.61    2.61
    2.61      .5
BR Coef=-1 , 0 , 0 ,, 0 ,,,0.8,-1,,0,
WSPro=,,,, 1 ,,,, 0 ,,,, 0 ,,,,-1 ,-1 ,-1 , 0 , 0 , 0 , 0 , 0
BC Design=,, 0 ,, 0 ,,,,,,
BC Use User HTab Curves=0
BC User HTab FreeFlow(D)= 0

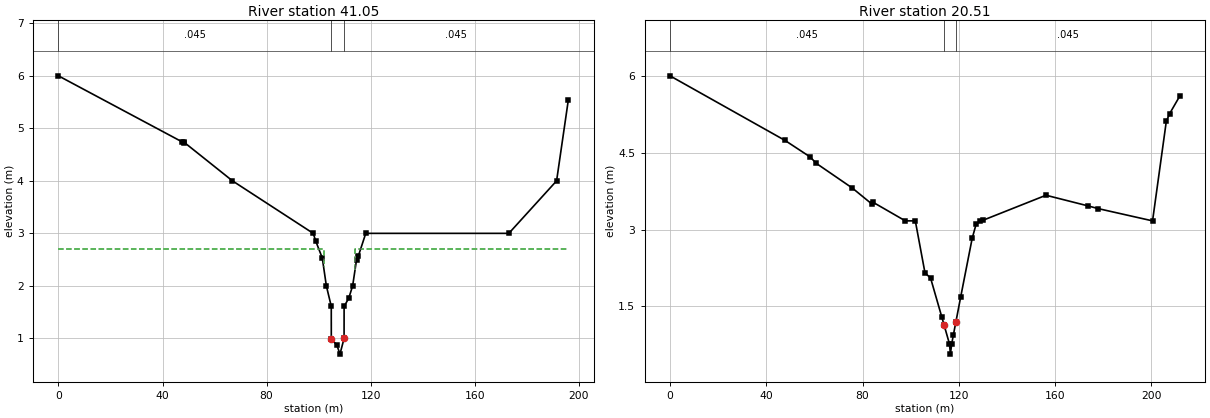
Type RM Length L Ch R = 1 ,41.05   ,7.95,13.7,10.9
Node Photo=..\..\..\..\Corner Brook\Windshield Survey\CB photos\P1000642.JPG
XS GIS Cut Line= 6
      345016.411     5423885.404      345062.372     5423872.953
      345101.758     5423851.043      345102.862     5423823.523
      345086.893     5423787.499       345060.13     5423765.541
#Sta/Elev= 23
       0       6   47.62    4.74   48.39    4.74   48.41    4.73   66.88       4
   97.91       3    98.9    2.85   101.4    2.53  102.96       2  104.85    1.61
  104.86     .98  106.94     .88  108.19      .7  109.77       1  109.78    1.61
  111.53    1.76  113.06       2  114.57     2.5  115.26    2.57   118.1       3
  173.08       3  191.43       4  195.94    5.54
#Mann= 3 , 0 , 0
       0    .045       0  104.86    .035       0  109.77    .045       0
#XS Ineff= 2 , 0
       0  101.91     2.7  113.97       0     2.7
Permanent Ineff=
       F       F
Bank Sta=104.86,109.77
XS Rating Curve= 0 ,0
Exp/Cntr=0.5,0.3

Type RM Length L Ch R = 1 ,20.51   ,17.7,20.51,20.51
XS GIS Cut Line= 6
      345017.135     5423887.085      345063.128     5423874.161
      345115.966     5423844.273      345115.966     5423831.778
      345090.668     5423786.743      345061.371     5423762.099
#Sta/Elev= 30
       0       6   47.77    4.74   58.14    4.42   60.85    4.29   75.76    3.81
   83.84     3.5   84.47    3.53   97.78    3.17  101.92    3.17  105.92    2.16
  108.29    2.05  112.89     1.3  113.84   1.144  116.11     .77   116.5     .57
  117.04     .77  117.76     .95  118.75   1.192  120.79    1.69  125.55    2.83
  127.16     3.1  128.66    3.16  129.94    3.18  156.22    3.67  173.87    3.46
  177.82    3.41  200.49    3.17   206.2    5.11  207.56    5.26  211.86    5.61
#Mann= 3 , 0 , 0
       0    .045       0  113.84    .035       0  118.75    .045       0
Bank Sta=113.84,118.75
XS Rating Curve= 0 ,0
Exp/Cntr=0.3,0.1

River Reach=CornerB         ,M004

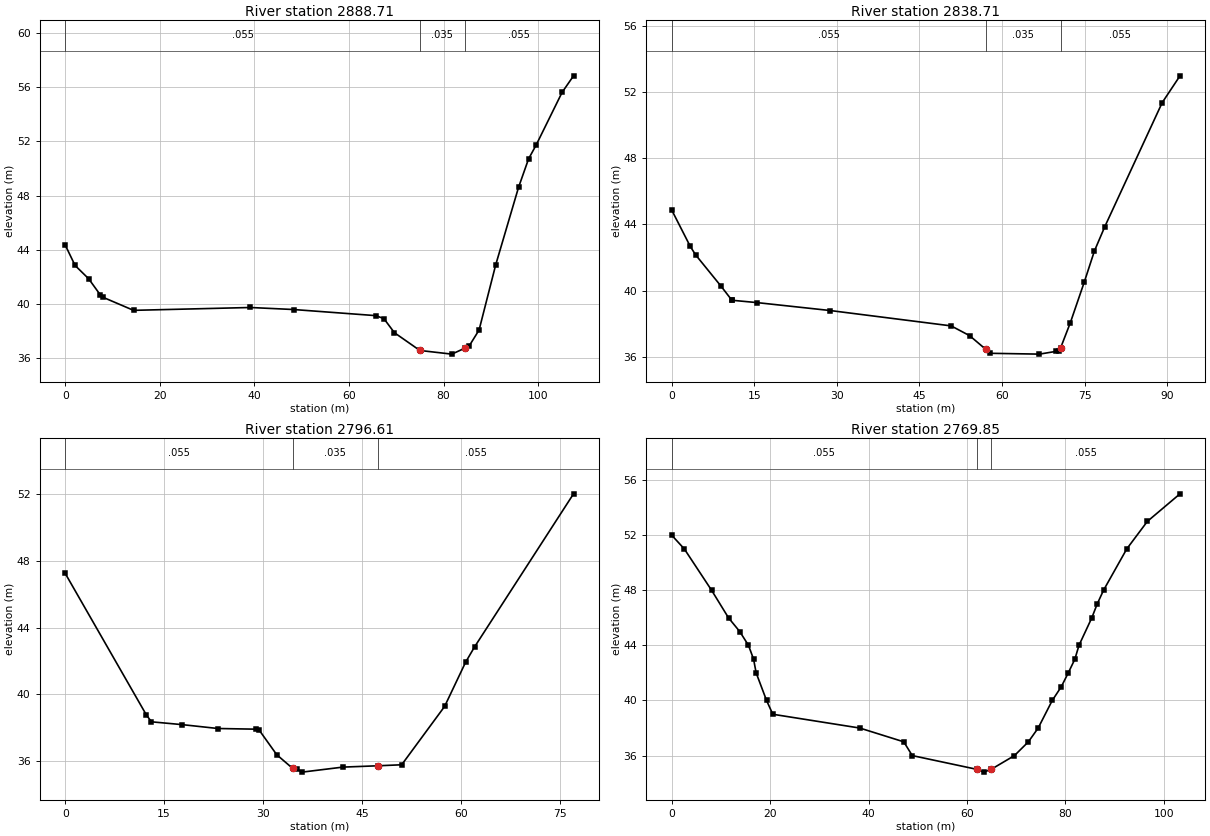
Type RM Length L Ch R = 1 ,2888.71 ,53.97,50,52.11
XS GIS Cut Line= 3
346669.0935058595422691.59967041346700.2282714845422715.34289551
 346740.142517095422770.79528809
#Sta/Elev= 22
       0   44.36    2.09   42.85    4.96   41.87     7.4   40.69    8.08   40.49
   14.45   39.54   39.16   39.75   48.31    39.6   65.65   39.15   67.38   38.93
   69.61   37.89   74.99   36.58   81.74   36.31   84.51   36.75   85.36   36.88
   87.51   38.09   91.02   42.89   95.85   48.61   97.98   50.72   99.57   51.73
  105.06   55.62  107.48   56.84
#Mann= 3 , 0 , 0
       0    .055       0   74.99    .035       0   84.51    .055       0
Bank Sta=74.99,84.51
XS Rating Curve= 0 ,0
Exp/Cntr=0.3,0.1

Type RM Length L Ch R = 1 ,2838.71 ,41.35,42.1,43.3
XS GIS Cut Line= 3
346641.8192749025422721.61871338346666.2966918955422736.76367188
346688.8312988285422796.17889404
#Sta/Elev= 22
       0   44.88    3.38   42.67    4.35   42.16    8.95   40.27   10.92   39.42
      11   39.41   15.49   39.27   28.78   38.79   50.76   37.86   54.11   37.27
   57.05   36.44    57.9    36.2    66.8   36.15   69.88   36.32    70.4   36.32
   70.66   36.54   72.42   38.06   74.94   40.51   76.78   42.39   78.66   43.86
    89.1   51.38   92.33      53
#Mann= 3 , 0 , 0
       0    .055       0   57.05    .035       0   70.66    .055       0
Bank Sta=57.05,70.66
XS Rating Curve= 0 ,0
Exp/Cntr=0.3,0.1

Type RM Length L Ch R = 1 ,2796.61 ,68.67,61.76,53.15
XS GIS Cut Line= 3
346623.3356933595422739.63427734346631.9049072275422755.19750977
346645.7158813485422812.87988281
#Sta/Elev= 18
       0   47.24   12.31   38.77   13.08   38.36   17.77   38.19   23.16   37.96
   28.87   37.92   29.42   37.86   32.08   36.39   34.47   35.58   35.08   35.54
   35.92   35.35    42.1   35.65   47.44   35.73   51.02   35.79   57.53   39.28
   60.72   41.93   62.07   42.84   77.08      52
#Mann= 3 , 0 , 0
       0    .055       0   34.47    .035       0   47.44    .055       0
Bank Sta=34.47,47.44
XS Rating Curve= 0 ,0
Exp/Cntr=0.3,0.1

Type RM Length L Ch R = 1 ,2769.85 ,72.21,71.38,82.76
XS GIS Cut Line= 5
       346606.19     5422741.889      346606.461     5422757.442
      346609.303     5422769.343      346602.942     5422789.899
      346639.752     5422829.388
#Sta/Elev= 30
       0      52    2.57      51    8.11      48   11.55      46   13.84      45
   15.61      44   16.64      43   17.17      42   19.28      40   20.55      39
   38.22      38   47.16      37   48.89      36   62.05      35   63.41    34.8
   64.91      35   69.65      36   72.48      37   74.47      38   77.33      40
   79.17      41   80.58      42   81.93      43   82.76      44   85.37      46
   86.46      47   87.75      48   92.47      51   96.66      53  103.29      55
#Mann= 3 , 0 , 0
       0    .055       0   62.05    .035       0   64.91    .055       0
Bank Sta=62.05,64.91
XS Rating Curve= 0 ,0
Exp/Cntr=0.3,0.1

River Reach=CornerB         ,TR001