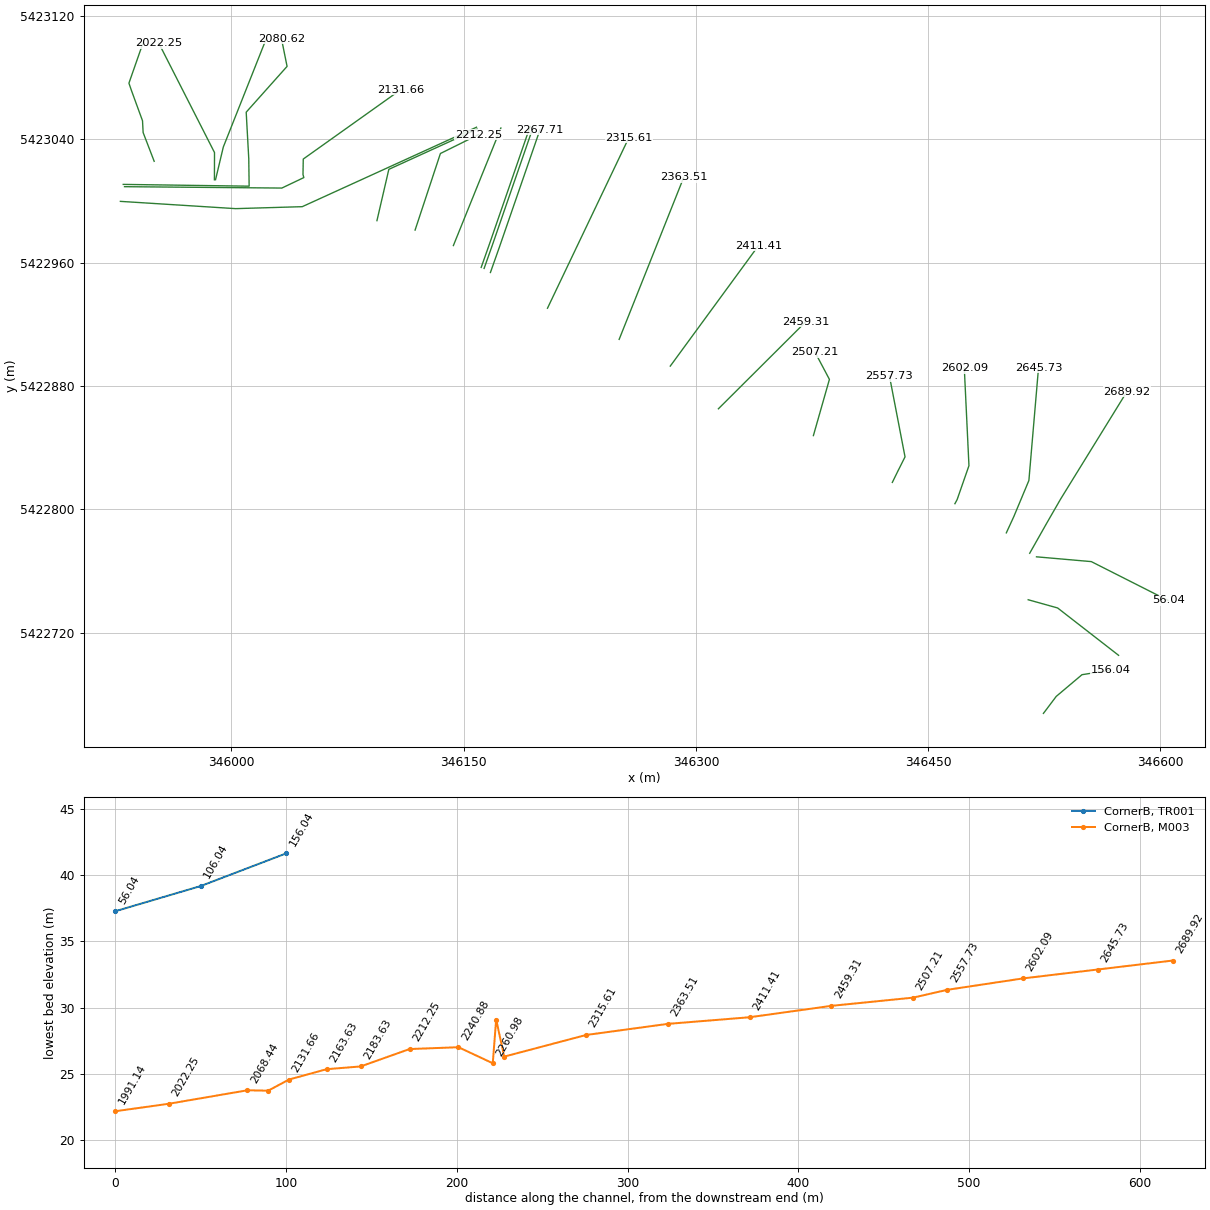
HEC-RAS study Corner_Brook2.prj: Corner_Brook2

--- Corner_Brook2.g02 (geometry) --- (continued)

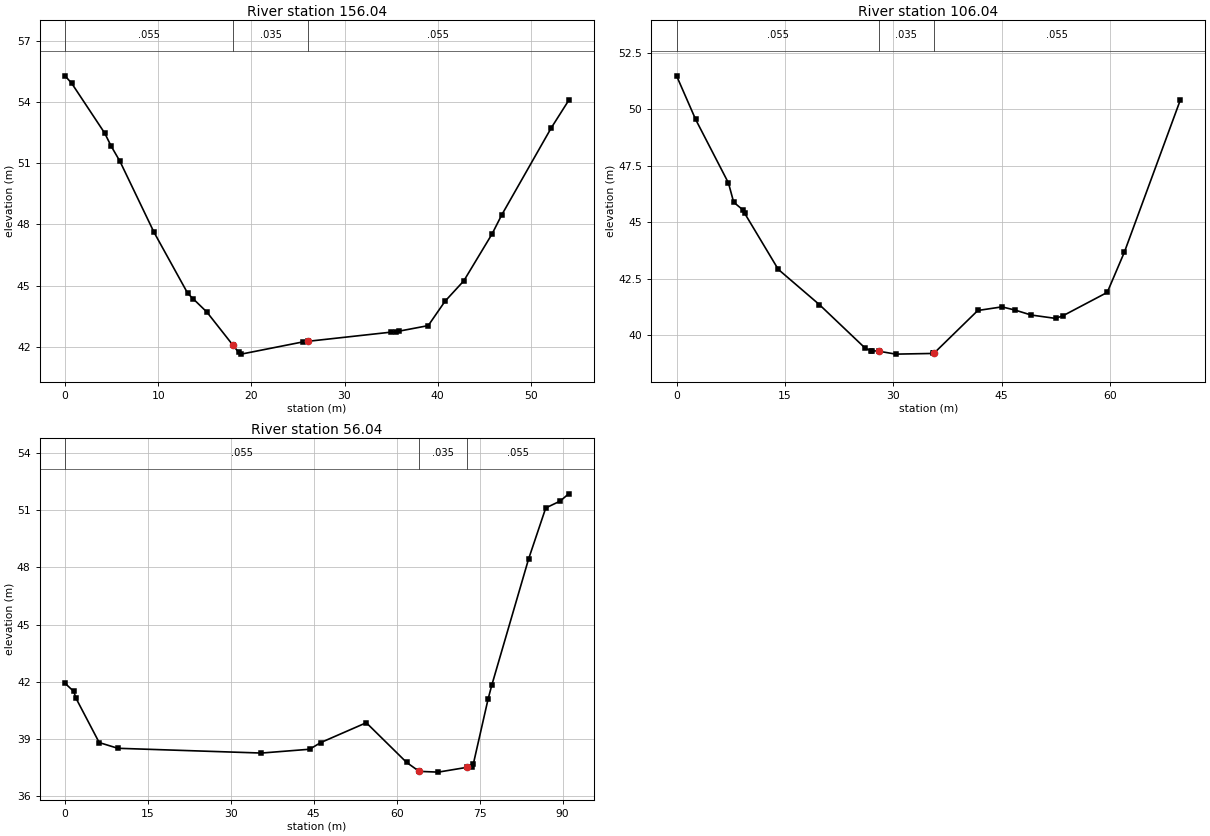
Type RM Length L Ch R = 1 ,156.04  ,60.89,50,30.28
XS GIS Cut Line= 4
346524.4650878915422667.72167969346532.7161254885422678.71990967
346549.3566894535422692.80627441346567.6198730475422695.73712158
#Sta/Elev= 24
       0    55.3     .71   54.94    4.27   52.48    4.94   51.86     5.9    51.1
    9.56   47.61   13.18   44.61   13.75   44.35   15.22    43.7   18.04   42.06
   18.63   41.72   18.91   41.63   25.53   42.23   26.08   42.26      35   42.71
   35.55   42.73   35.87   42.76   38.98   43.03   40.79   44.23    42.8   45.23
   45.84   47.54   46.86   48.46   52.18   52.74   54.05   54.09
#Mann= 3 , 0 , 0
       0    .055       0   18.04    .035       0   26.08    .055       0
Bank Sta=18.04,26.08
XS Rating Curve= 0 ,0
Exp/Cntr=0.3,0.1

Type RM Length L Ch R = 1 ,106.04  ,34.27,50,45.57
XS GIS Cut Line= 3
 346514.613281255422741.43011475346533.6350708015422736.08831787
346572.9965209965422705.37109375
#Sta/Elev= 25
       0   51.48    2.64   49.55    7.18   46.74     7.9   45.89    9.14   45.56
    9.42    45.4   14.07   42.92   19.76   41.36   26.11   39.43   26.85   39.33
   26.99   39.32   27.96    39.3   30.33   39.17   35.46    39.2   35.59   39.21
   35.62   39.21   41.68    41.1   45.02   41.26   46.82   41.12   49.06    40.9
   52.45   40.75   53.48   40.87   59.59    41.9   61.96   43.68   69.69    50.4
#Mann= 3 , 0 , 0
       0    .055       0   27.96    .035       0   35.59    .055       0
Bank Sta=27.96,35.59
XS Rating Curve= 0 ,0
Exp/Cntr=0.3,0.1

Type RM Length L Ch R = 1 ,56.04   ,20.84,20,20.51
XS GIS Cut Line= 3
346519.9874877935422769.26611328346555.3927001955422766.15808105
346604.9232788095422740.98547363
#Sta/Elev= 21
       0   41.93    1.59    41.5    1.98   41.15    6.19   38.82    9.56   38.52
   35.54   38.27   44.25   38.47   46.27   38.82    54.5   39.86   61.79   37.78
   64.07   37.31   67.51   37.27   72.69   37.52   73.54   37.55   73.88   37.72
   76.53    41.1   77.19   41.82   83.84   48.43   86.96   51.12   89.57   51.48
    91.1   51.86
#Mann= 3 , 0 , 0
       0    .055       0   64.07    .035       0   72.69    .055       0
Bank Sta=64.07,72.69
XS Rating Curve= 0 ,0
Exp/Cntr=0.3,0.1

River Reach=CornerB         ,M003

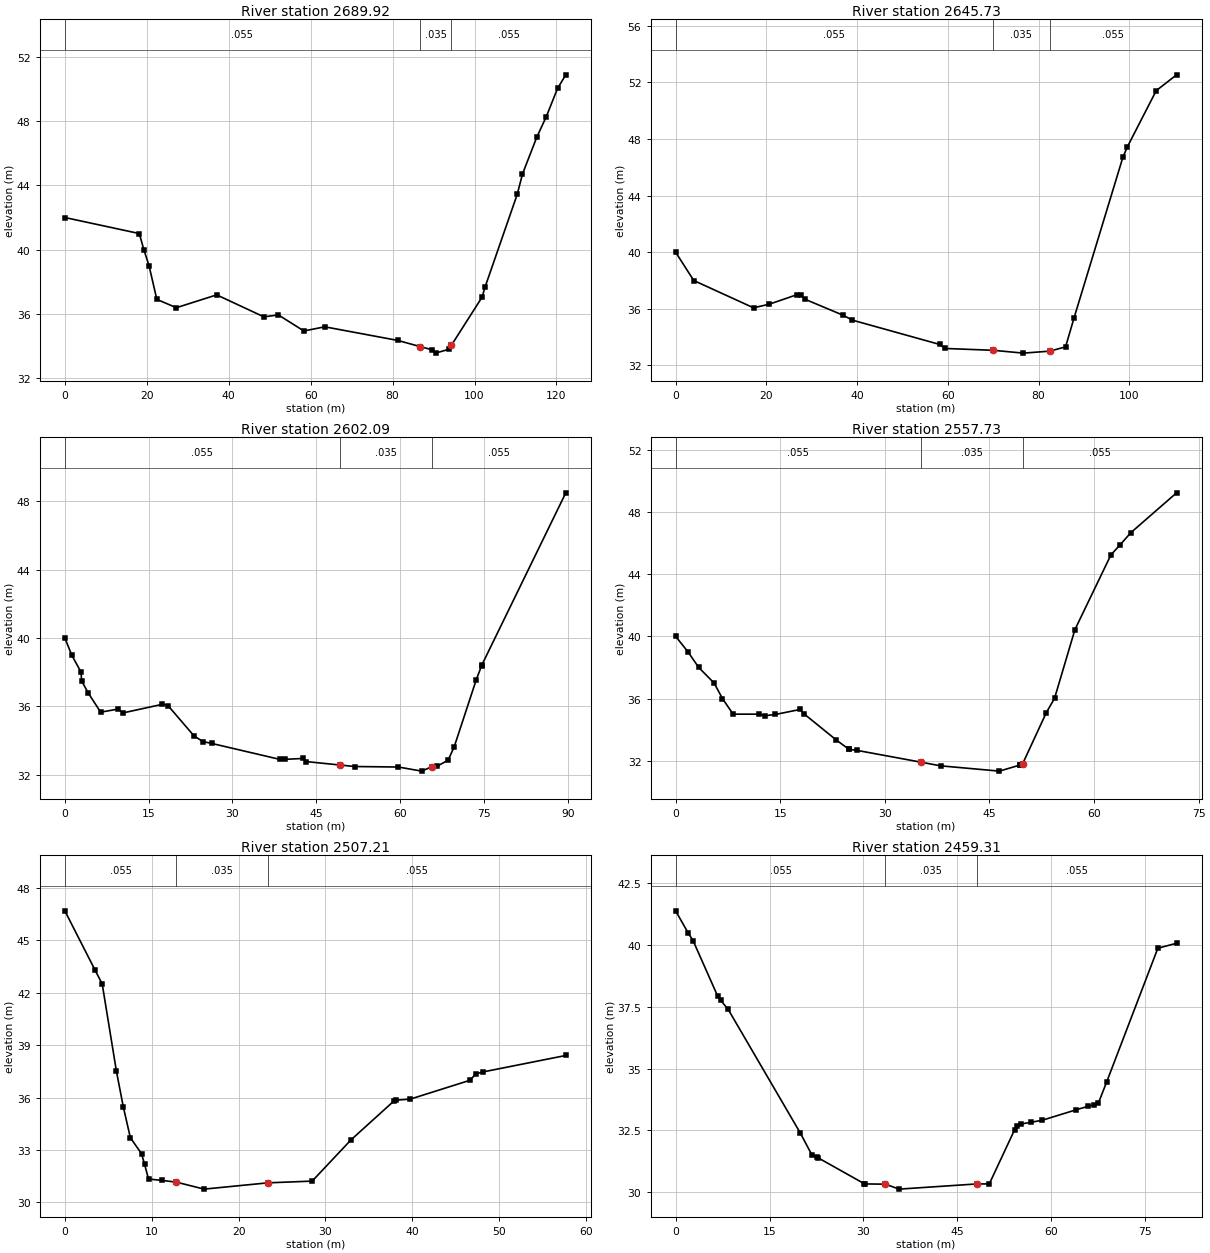
Type RM Length L Ch R = 1 ,2689.92 ,32.25,44.19,49.16
XS GIS Cut Line= 4
      346515.586      5422771.58      346526.609     5422791.136
      346535.579      5422806.78      346578.413     5422876.471
#Sta/Elev= 25
       0      42   18.18      41   19.28      40   20.55      39   22.45    36.9
   27.22   36.38   37.07   37.18   48.59   35.81   52.13   35.93   58.35   34.93
   63.44   35.19   81.29   34.34   86.68   33.96   89.61   33.76   90.48   33.55
   93.72   33.79   94.38   34.05  101.85   37.04  102.55   37.65  110.42   43.44
  111.71   44.71  115.19      47  117.51   48.28  120.26   50.04  122.28   50.89
#Mann= 3 , 0 , 0
       0    .055       0   86.68    .035       0   94.38    .055       0
Bank Sta=86.68,94.38
XS Rating Curve= 0 ,0
Exp/Cntr=0.3,0.1

Type RM Length L Ch R = 1 ,2645.73 ,40.6,43.64,45.07
XS GIS Cut Line= 4
      346500.489     5422784.788      346505.341     5422795.388
      346515.063     5422818.771      346521.292      5422891.95
#Sta/Elev= 20
       0      40       4      38   17.18   36.07   20.68   36.33   26.85   37.01
   27.61   36.99   28.49   36.68   36.97   35.54   38.97    35.2   58.25   33.48
   59.35    33.2      70   33.07   76.68   32.87   82.46   33.01   85.96   33.31
   87.83   35.36   98.61   46.72   99.58   47.44  105.94   51.41  110.43   52.53
#Mann= 3 , 0 , 0
       0    .055       0      70    .035       0   82.46    .055       0
Bank Sta=70,82.46
XS Rating Curve= 0 ,0
Exp/Cntr=0.3,0.1

Type RM Length L Ch R = 1 ,2602.09 ,43.5,44.36,45.77
XS GIS Cut Line= 4
      346467.292     5422803.732      346468.721     5422806.377
      346476.357     5422828.375      346473.353     5422891.646
#Sta/Elev= 29
       0      40    1.22      39    2.89      38    3.01   37.48    4.19   36.77
    6.41   35.65    9.47   35.83   10.44   35.61   17.44   36.11   18.45   36.04
   23.12   34.26   24.71   33.93    26.3   33.82   38.44   32.89   39.32   32.89
   42.54   32.94   43.17   32.76   49.15   32.56   51.87   32.47    59.7   32.44
   63.85    32.2   65.67   32.46   66.63   32.49   68.58   32.84   69.67   33.62
   73.63   37.56   74.57   38.37   74.66   38.44   89.64   48.49
#Mann= 3 , 0 , 0
       0    .055       0   49.15    .035       0   65.67    .055       0
Bank Sta=49.15,65.67
XS Rating Curve= 0 ,0
Exp/Cntr=0.3,0.1

Type RM Length L Ch R = 1 ,2557.73 ,20.72,20,21.87
XS GIS Cut Line= 4
      346426.875     5422817.542      346430.293     5422824.542
      346435.073     5422834.093      346425.021     5422886.513
#Sta/Elev= 28
       0      40    1.78      39    3.31      38    5.52      37    6.72      36
    8.25      35   12.02      35   12.81    34.9   14.31   34.98   17.83    35.3
   18.47      35   23.07   33.33   24.84   32.75   24.88   32.74   26.06   32.67
   35.13   31.92   38.01   31.68   46.44   31.34   49.37   31.73   49.41   31.74
   49.77   31.81   53.17    35.1   54.35   36.02   57.27   40.43   62.43   45.23
   63.79    45.9   65.29   46.66   71.85   49.22
#Mann= 3 , 0 , 0
       0    .055       0   35.13    .035       0   49.77    .055       0
Bank Sta=35.13,49.77
XS Rating Curve= 0 ,0
Exp/Cntr=0.3,0.1

Type RM Length L Ch R = 1 ,2507.21 ,53.89,47.9,41.51
XS GIS Cut Line= 3
346375.898681641 5422847.8994751346386.2429199225422884.35992432
346377.0280761725422901.84527588
#Sta/Elev= 22
       0    46.7    3.47   43.31     4.3   42.51    5.94    37.5    6.73   35.46
    7.54    33.7    8.83   32.78    9.18   32.17    9.63   31.33   11.17   31.25
   12.84   31.15   16.03   30.75   23.36   31.11   28.47   31.21   32.95   33.58
    37.9   35.81   38.14   35.85   39.77   35.91   46.64   36.99   47.28   37.35
   48.16   37.47   57.66   38.41
#Mann= 3 , 0 , 0
       0    .055       0   12.84    .035       0   23.36    .055       0
Bank Sta=12.84,23.36
XS Rating Curve= 0 ,0
Exp/Cntr=0.3,0.1

Type RM Length L Ch R = 1 ,2459.31 ,45.43,47.9,50.41
XS GIS Cut Line= 2
346314.5562744145422865.28967285346371.1104736335422921.87249756
#Sta/Elev= 28
       0   41.37    2.04   40.46    2.78   40.17    6.69   37.94    7.18   37.76
    8.39   37.39   19.88   32.41   21.81   31.49   22.58   31.42   22.79   31.39
   30.12   30.35   30.31   30.34   33.51   30.33   35.69   30.13   48.13   30.34
   50.09   30.34   54.14   32.53   54.45   32.68   55.17   32.76   56.73   32.83
   58.52   32.91   63.91   33.33   65.93   33.48    66.8   33.54   67.49   33.59
   68.84   34.46   77.01   39.86      80   40.06
#Mann= 3 , 0 , 0
       0    .055       0   33.51    .035       0   48.13    .055       0
Bank Sta=33.51,48.13
XS Rating Curve= 0 ,0
Exp/Cntr=0.3,0.1

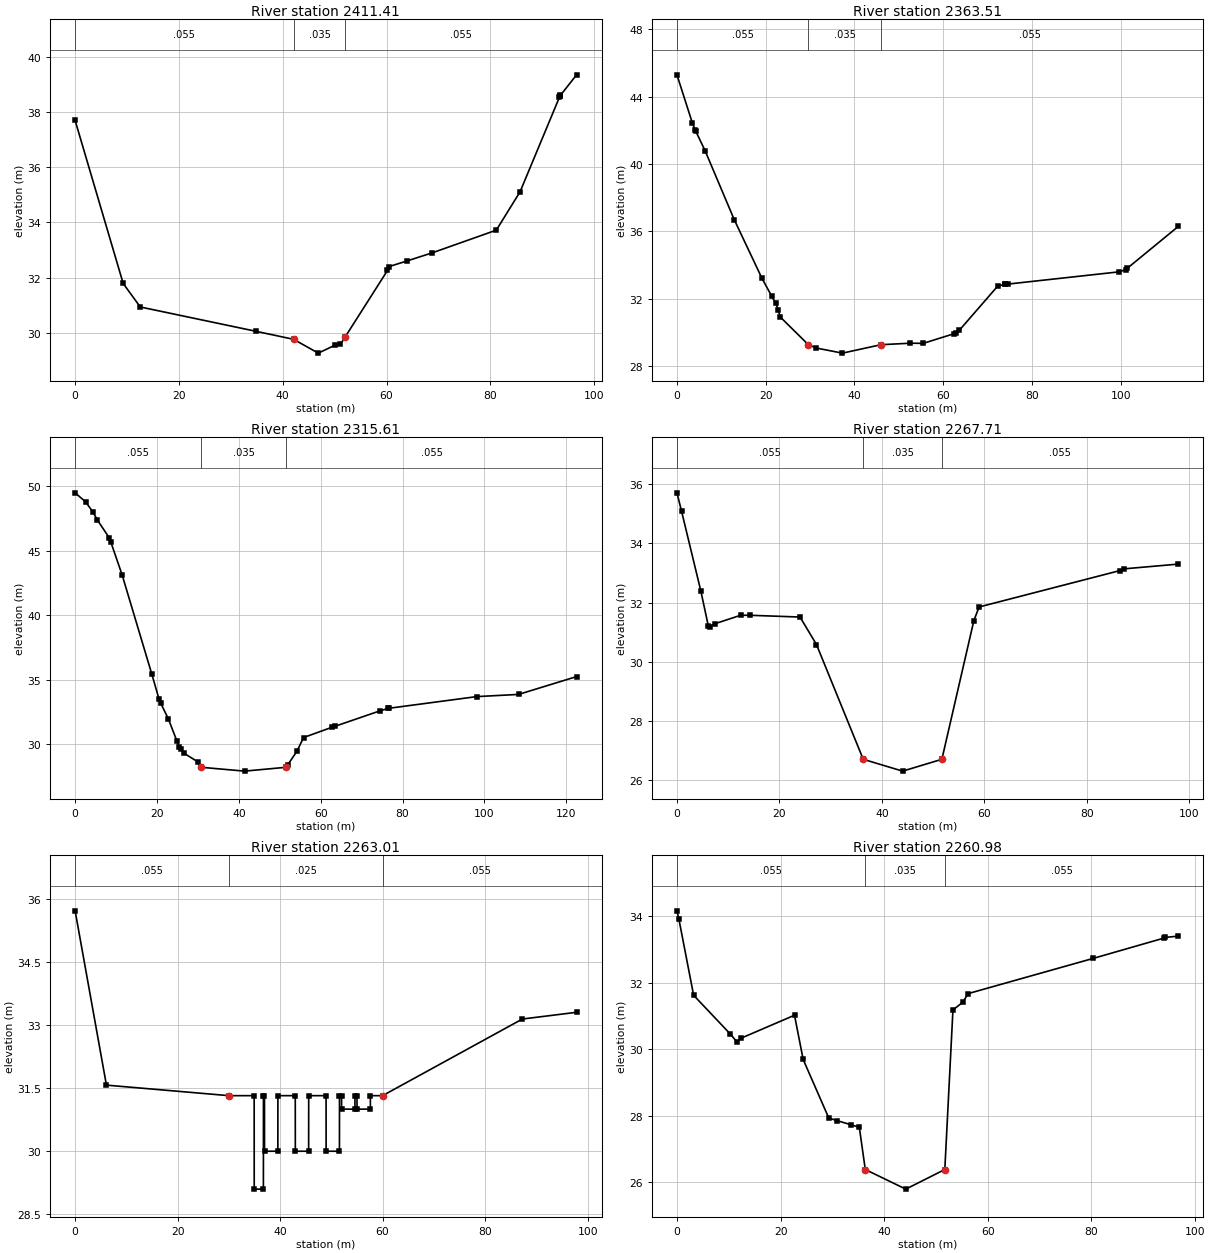
Type RM Length L Ch R = 1 ,2411.41 ,43.95,47.9,53.88
XS GIS Cut Line= 2
346283.4758911135422892.98492432346340.3834838875422971.04272461
#Sta/Elev= 20
       0   37.69    9.26   31.79   12.55   30.94   34.83   30.06   42.09   29.77
   46.84   29.27    50.1   29.56   51.12   29.59   52.05  29.864   60.17   32.26
   60.44    32.4   63.85    32.6   68.81    32.9   81.14   33.72   85.72   35.11
    93.3   38.53   93.36   38.56   93.48   38.59    93.5    38.6    96.6   39.34
#Mann= 3 , 0 , 0
       0    .055       0   42.09    .035       0   52.05    .055       0
Bank Sta=42.09,52.05
XS Rating Curve= 0 ,0
Exp/Cntr=0.3,0.1

Type RM Length L Ch R = 1 ,2363.51 ,48.76,47.9,46.93
XS GIS Cut Line= 2
346250.454711914 5422910.3057251346292.1392822275423015.34210205
#Sta/Elev= 28
       0    45.3    3.45   42.46     4.1   42.04    4.23   41.96    6.35   40.79
   12.91    36.7   19.15   33.22   21.34   32.16   22.28   31.72   22.87   31.33
   23.23   30.93   29.62   29.27   31.45   29.07    37.3   28.77   45.98   29.27
   52.63   29.36   55.51   29.35   62.53   29.93   62.92   29.97   63.62   30.12
   72.32   32.76   73.94   32.85   73.98   32.85   74.55   32.87   99.72    33.6
  101.11   33.73  101.45    33.8  113.01    36.3
#Mann= 3 , 0 , 0
       0    .055       0   29.62    .035       0   45.98    .055       0
Bank Sta=29.62,45.98
XS Rating Curve= 0 ,0
Exp/Cntr=0.3,0.1

Type RM Length L Ch R = 1 ,2315.61 ,48.49,47.9,49.46
XS GIS Cut Line= 2
346204.1672973635422930.50671387346256.7380981455423041.16589355
#Sta/Elev= 30
       0   49.48    2.56   48.78    4.28   48.03    5.45   47.37    8.33      46
    8.74   45.65   11.46   43.15   18.72   35.46   20.46   33.55   20.87   33.22
    22.8   31.96   24.87   30.26   25.41   29.81   25.85   29.66   26.63   29.31
   29.98   28.65   30.71   28.23    41.4   27.93   51.63   28.23   51.99   28.44
    54.2   29.47    55.8   30.53   62.79   31.33   63.38   31.39    74.5    32.6
   76.48   32.78   76.74    32.8    98.1    33.7  108.33   33.87  122.51   35.25
#Mann= 3 , 0 , 0
       0    .055       0   30.71    .035       0   51.63    .055       0
Bank Sta=30.71,51.63
XS Rating Curve= 0 ,0
Exp/Cntr=0.3,0.1

Type RM Length L Ch R = 1 ,2267.71 ,4.71,4.71,4.71
XS GIS Cut Line= 3
       346167.32     5422953.681      346172.939     5422969.644
      346199.281     5423046.168
#Sta/Elev= 18
       0   35.71      .9   35.09    4.65    32.4    6.11   31.22    6.36   31.18
    7.34   31.28   12.44   31.57   14.17   31.57   24.02   31.51   27.23   30.58
   36.35    26.7   44.04    26.3    51.7    26.7   57.94   31.39   58.96   31.85
   86.42   33.08   87.27   33.14   97.85    33.3
#Mann= 3 , 0 , 0
       0    .055       0   36.35    .035       0    51.7    .055       0
Bank Sta=36.35,51.7
XS Rating Curve= 0 ,0
Exp/Cntr=0.5,0.3

Type RM Length L Ch R = 1 ,2263.01 ,2,2,2
Node Photo=..\..\..\Corner Brook\Windshield Survey\CB photos\P1000680.JPG
BEGIN DESCRIPTION:
Bowater Dam
END DESCRIPTION:
XS GIS Cut Line= 3
      346163.246     5422956.327      346168.647     5422971.682
      346194.856     5423047.798
#Sta/Elev= 30
       0   35.71    6.11   31.57      30   31.32   34.94   31.32   34.95    29.1
   36.74    29.1   36.75   31.32   36.95   31.32   36.96      30   39.56      30
   39.57   31.32   42.96   31.32   42.97      30   45.57      30   45.58   31.32
   48.97   31.32   48.98      30   51.58      30   51.59   31.32   51.99   31.32
      52      31    54.6      31   54.61   31.32      55   31.32   55.01      31
   57.61      31   57.62   31.32      60   31.32   87.27   33.14   97.85    33.3
#Mann= 3 , 0 , 0
       0    .055       0      30    .025       0      60    .055       0
Bank Sta=30,60
XS Rating Curve= 35 ,-1
       0    29.1      .1   29.95      25   31.12      50   31.62      75   31.87
     100   32.06   146.8   32.34   163.8   32.43   170.5   32.46   176.3   32.49
   177.9    32.5   179.7   32.51   189.4   32.55   194.1   32.57   200.2    32.6
   229.1   32.72   230.7   32.72   238.7   32.75   246.1   32.78   251.5    32.8
   254.8   32.81   300.9   32.97     303   32.97   315.7   33.01   319.7   33.02
   346.6    33.1   351.1   33.11   351.7   33.11   355.5   33.12   420.9   33.28
   429.5   33.29   481.7    33.4     487   33.42   498.6   33.44     504   33.45
Exp/Cntr=0.5,0.3

Type RM Length L Ch R = 1 ,2260.98 ,23.13,20.09,20.28
Node Photo=..\..\..\Corner Brook\Windshield Survey\CB photos\P1000676.JPG
XS GIS Cut Line= 3
      346161.359     5422956.991       346166.76     5422972.345
      346192.969     5423048.462
#Sta/Elev= 22
       0   34.17     .39   33.91    3.22   31.63   10.33   30.46   11.61   30.22
   12.39   30.34   22.69   31.03   24.36    29.7    29.3   27.94   30.89   27.86
   33.52   27.74    35.2   27.66   36.35   26.39   44.17    25.8    51.7   26.39
   53.27   31.19   55.17   31.42   56.19   31.68   80.35   32.74   93.99   33.35
   94.25   33.37   96.78   33.41
#Mann= 3 , 0 , 0
       0    .055       0   36.35    .035       0    51.7    .055       0
Bank Sta=36.35,51.7
XS Rating Curve= 0 ,0
Exp/Cntr=0.5,0.3

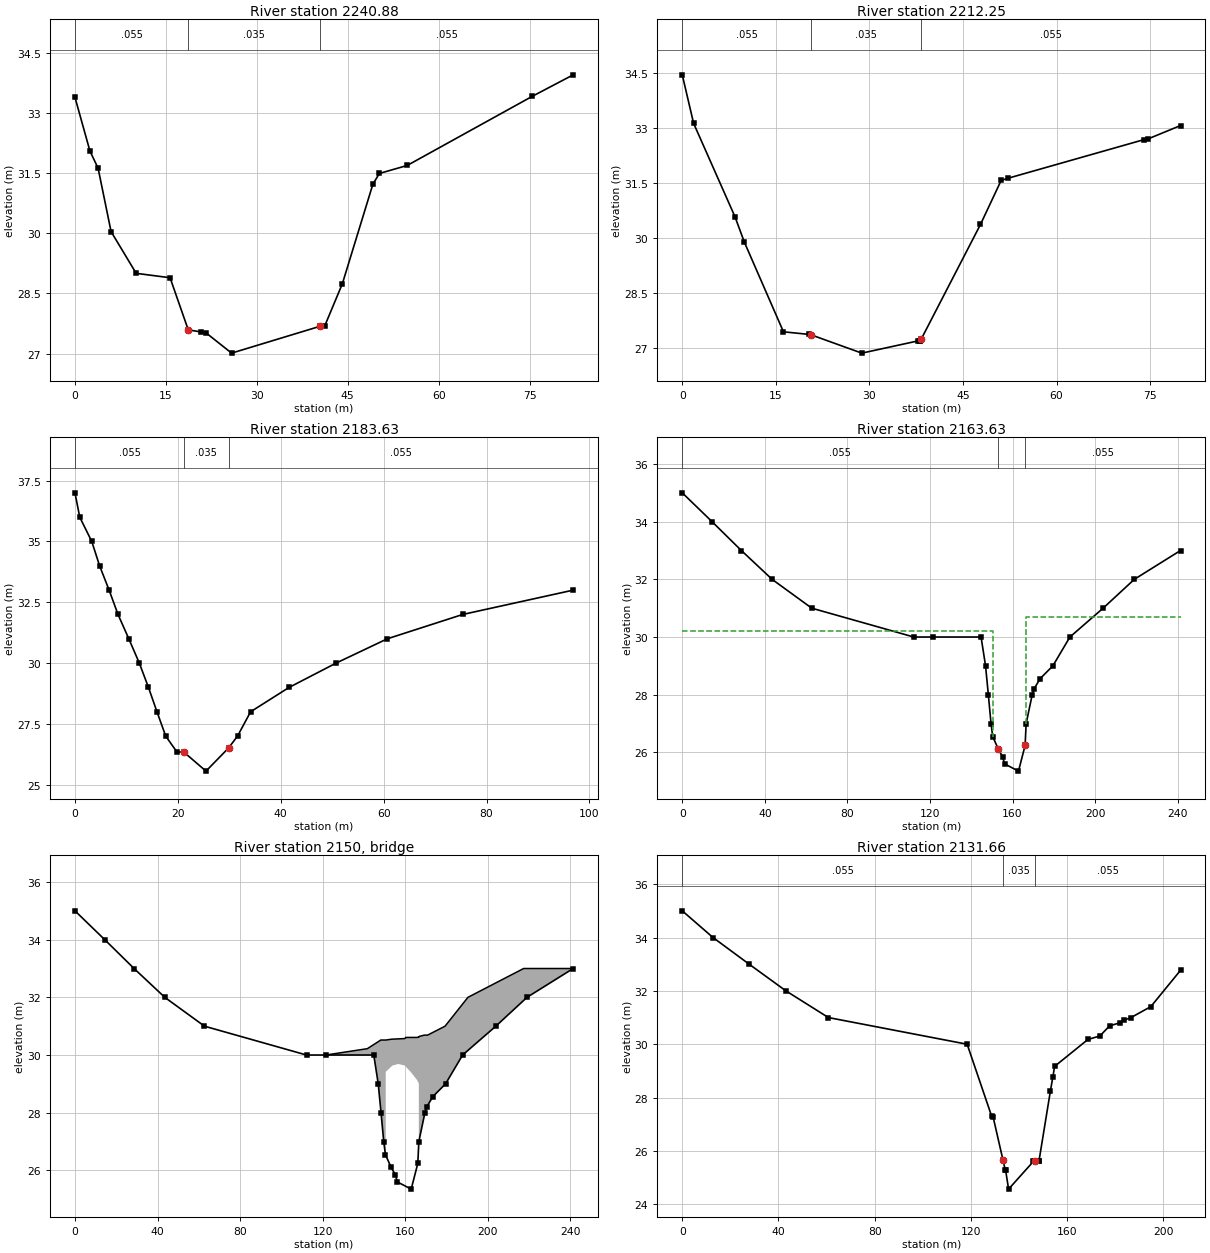
Type RM Length L Ch R = 1 ,2240.88 ,28.07,28.63,29.71
XS GIS Cut Line= 2
346143.3950805665422971.15368652346174.0800781255423047.40252686
#Sta/Elev= 18
       0   33.39    2.47   32.05    3.82   31.62    5.96   30.04    10.1      29
   15.69   28.89   18.69   27.59   20.74   27.54   21.67   27.51   25.84   27.01
   40.44   27.68   41.18   27.68   44.11   28.74   49.14   31.22   50.21   31.49
   54.81   31.69   75.39   33.41   82.19   33.95
#Mann= 3 , 0 , 0
       0    .055       0   18.69    .035       0   40.44    .055       0
Bank Sta=18.69,40.44
XS Rating Curve= 0 ,0
Exp/Cntr=0.3,0.1

Type RM Length L Ch R = 1 ,2212.25 ,26.98,28.63,31.48
XS GIS Cut Line= 3
346118.6710815435422981.20568848346135.0164794925423030.85992432
346159.7166748055423043.15087891
#Sta/Elev= 18
       0   34.44    1.82   33.12    8.45   30.58    9.95   29.89   16.22   27.45
   20.27   27.38   20.61   27.37   28.78   26.87   37.72    27.2   38.12   27.19
   38.14   27.19   38.33   27.26    47.8   30.37   51.12   31.57   52.28   31.63
   74.06   32.68    74.7    32.7   79.86   33.06
#Mann= 3 , 0 , 0
       0    .055       0   20.61    .035       0   38.33    .055       0
Bank Sta=20.61,38.33
XS Rating Curve= 0 ,0
Exp/Cntr=0.3,0.1

Type RM Length L Ch R = 1 ,2183.63 ,26.62,19.98,12.38
XS GIS Cut Line= 3
       346094.03      5422987.31      346101.712     5423020.588
      346158.706     5423046.703
#Sta/Elev= 22
       0      37     .93      36    3.27      35    4.79      34    6.64      33
    8.37      32   10.47      31   12.51      30   14.29      29   15.94      28
   17.64      27   19.81   26.35   21.18   26.34   25.47   25.56   29.85   26.51
    31.6      27   34.14      28   41.61      29   50.75      30   60.71      31
   75.37      32   96.84      33
#Mann= 3 , 0 , 0
       0    .055       0   21.18    .035       0   29.85    .055       0
Bank Sta=21.18,29.85
XS Rating Curve= 0 ,0
Exp/Cntr=0.3,0.1

Type RM Length L Ch R = 1 ,2163.63 ,22.26,22,21.26
Node Photo=..\..\..\..\Corner Brook\Windshield Survey\CB photos\P1000674.JPG
XS GIS Cut Line= 4
      345928.344     5422999.821       346002.75     5422995.103
      346045.799     5422996.378      346158.322     5423047.918
#Sta/Elev= 26
       0      35   14.43      34   28.63      33   43.53      32   62.75      31
  112.18      30  121.52      30  144.77      30  146.94      29  148.29      28
  149.59      27  150.41   26.55  153.14   26.11   155.2   25.85  156.19    25.6
   162.9   25.35   166.1   26.24  166.61      27  169.55      28  170.42    28.2
  173.42   28.56  179.55      29  187.81      30   203.9      31  219.01      32
  241.39      33
#Mann= 3 , 0 , 0
       0    .055       0  153.14    .035       0   166.1    .055       0
#XS Ineff= 2 , 0
       0  150.58   30.22   166.6       0   30.69
Permanent Ineff=
       F       F
Bank Sta=153.14,166.1
XS Rating Curve= 0 ,0
Exp/Cntr=0.5,0.3

Type RM Length L Ch R = 3 ,2150    ,,,
Node Photo=..\..\..\Corner Brook\Windshield Survey\CB photos\P1000666.JPG
BEGIN DESCRIPTION:
O'Connell Drive (Structure 2110C)
END DESCRIPTION:
Bridge Culvert--1,0,-1,-1, 0
Deck Dist Width WeirC Skew NumUp NumDn MinLoCord MaxHiCord MaxSubmerge Is_Ogee
2.8,14,1.67,0, 24, 21, 30, , 0.98, 0, 0,0,,
  121.52  141.64  148.18  150.55  150.58  150.59  153.59  153.63  156.59  159.59
  160.05  160.21  162.59  165.59  166.59   166.6  166.93  167.66  169.24  170.83
   179.3  190.38  217.37  241.39
      30   30.22   30.52   30.52   30.52   30.52   30.55   30.55   30.56   30.57
   30.58   30.61   30.61   30.61   30.62   30.63   30.65   30.66   30.69   30.69
      31      32      33      33
                                      24   29.42   29.62   29.63   29.69   29.64
   29.62    29.6   29.42   29.15   29.02      24
                                
   63.59  121.13  129.24  131.89  132.23  132.24  134.88  135.24  138.24  138.43
  141.24  143.24  147.24  148.23  148.24  148.38  150.89  153.03  155.32  162.74
   171.7
      31   30.13   30.46   30.47   30.48   30.48    30.5  30.505   30.51   30.53
   30.54   30.55   30.58   30.59   30.59   30.59    30.6   30.61   30.56   30.49
   30.58
                                      24   29.42   29.59   29.62   29.69   29.69
   29.64   29.57   29.15   29.02      24
        
BR Coef=-1 , 0 , 0 ,, 0 ,,,0.8,-1,,0,
WSPro=,,,, 1 ,,,, 0 ,,,, 0 ,,,,-1 ,-1 ,-1 , 0 , 0 , 0 , 0 , 0
BC Design=,, 0 ,, 0 ,,,,,,
BC Use User HTab Curves=0
BC User HTab FreeFlow(D)= 0

Type RM Length L Ch R = 1 ,2131.66 ,11.18,12.2,13.35
XS GIS Cut Line= 6
       345931.02     5423009.346      346032.623     5423008.449
       346046.82     5423015.244      346046.274     5423017.228
      346046.445     5423027.265      346109.389     5423072.259
#Sta/Elev= 27
       0      35   12.77      34   27.81      33   43.09      32   60.74      31
  118.41      30   128.6    27.3  129.24   27.26  133.32  25.651  134.21    25.3
  134.39   25.28  135.63   24.57  145.96   25.61   146.8   25.62  148.21   25.63
  148.29   25.64  153.03   28.26  154.04   28.78  154.75   29.17  168.61   30.18
  173.58   30.31  177.62   30.69   181.8    30.8  183.46    30.9   186.3   30.99
  194.75   31.41  207.08   32.77
#Mann= 3 , 0 , 0
       0    .055       0  133.32    .035       0   146.8    .055       0
Bank Sta=133.32,146.8
XS Rating Curve= 0 ,0
Exp/Cntr=0.3,0.1

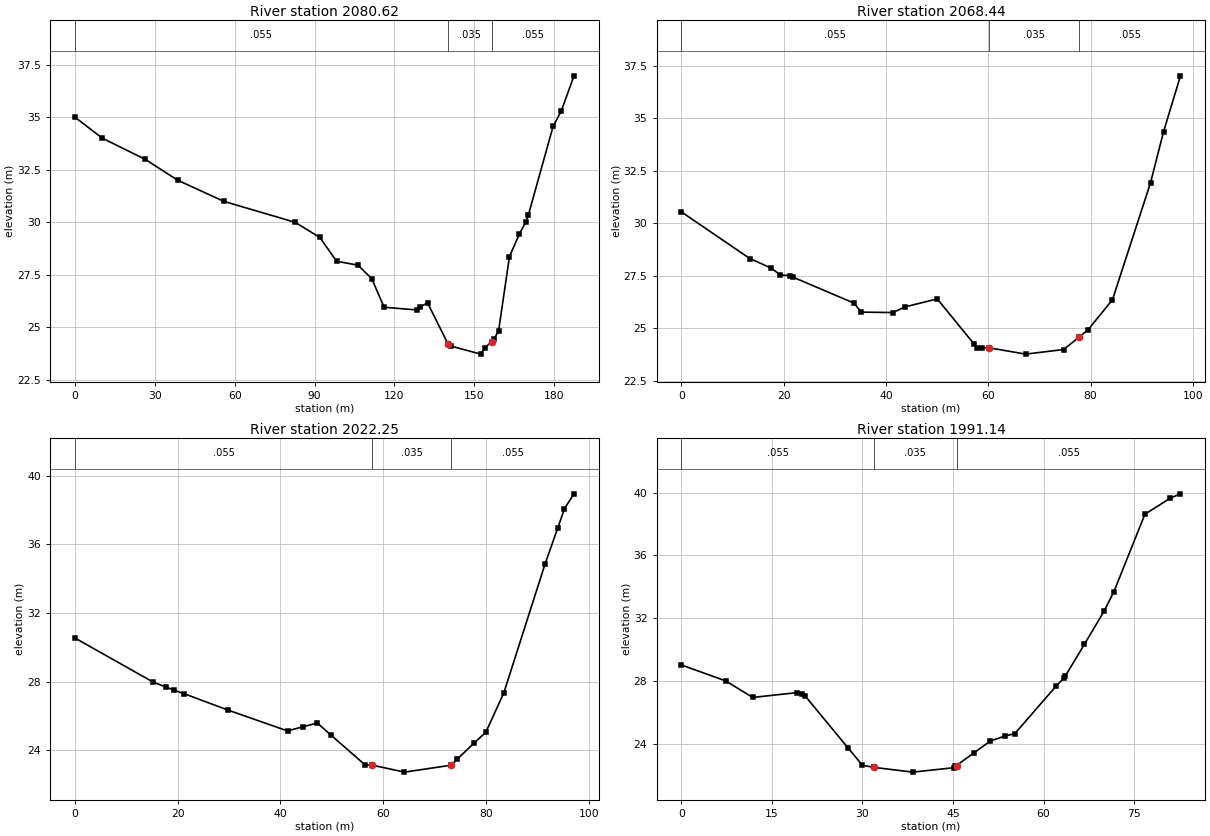
Type RM Length L Ch R = 1 ,2080.62 ,7.82,12.17,17.26
XS GIS Cut Line= 6
      345930.185     5423010.828      346011.495     5423009.672
      346011.251     5423027.508      346009.591     5423057.665
      346035.995      5423087.37      346032.374     5423105.315
#Sta/Elev= 28
       0      35   10.31      34   26.33      33   38.62      32   55.87      31
    82.7      30   91.97   29.28   98.25   28.15   106.3   27.96  111.46   27.32
   116.1   25.96  128.59   25.83  129.56   25.97  132.41   26.17  140.04   24.23
   141.3   24.11  152.37   23.73  153.95   24.03  156.53   24.33  157.34   24.43
   159.1   24.84  163.18   28.37  166.91   29.45  169.37   30.02  170.31   30.36
  179.58   34.57  182.68   35.31  187.42   36.97
#Mann= 3 , 0 , 0
       0    .055       0  140.04    .035       0  156.53    .055       0
Bank Sta=140.04,156.53
XS Rating Curve= 0 ,0
Exp/Cntr=0.3,0.1

Type RM Length L Ch R = 1 ,2068.44 ,33.61,46.19,57.27
XS GIS Cut Line= 3
345989.7929077155423013.86950684345994.8095092775423035.04589844
346022.6514892585423105.56347656
#Sta/Elev= 23
       0   30.53   13.37   28.31   17.52   27.86   19.34   27.53   21.14    27.5
   21.76   27.43   33.72   26.19   35.17   25.76   41.34   25.74   43.75   26.01
   50.02   26.39   57.22   24.24   57.73   24.06    58.7   24.07   60.17   24.06
   67.32   23.76   74.74   23.98   77.71   24.56   79.48   24.91   84.28   26.35
   91.74   31.93   94.27   34.35   97.58   37.01
#Mann= 3 , 0 , 0
       0    .055       0   60.17    .035       0   77.71    .055       0
Bank Sta=60.17,77.71
XS Rating Curve= 0 ,0
Exp/Cntr=0.3,0.1

Type RM Length L Ch R = 1 ,2022.25 ,34.56,31.11,28.31
XS GIS Cut Line= 3
345989.0667114265423013.80352783 345989.132690435423031.48352051
345953.182128906 5423102.3637085
#Sta/Elev= 22
       0   30.55   15.18   27.99   17.68    27.7   19.31   27.51   21.32    27.3
   29.82   26.35   41.38   25.14   44.34   25.38   47.19    25.6   49.86   24.89
   56.52   23.15   57.83   23.15   64.14   22.74   73.19   23.14   74.41   23.49
   77.73   24.44   79.99   25.06    83.5   27.36   91.52   34.86   93.99   36.95
   95.31   38.09   97.16   38.95
#Mann= 3 , 0 , 0
       0    .055       0   57.83    .035       0   73.19    .055       0
Bank Sta=57.83,73.19
XS Rating Curve= 0 ,0
Exp/Cntr=0.3,0.1

Type RM Length L Ch R = 1 ,1991.14 ,4.99,5.33,3.98
XS GIS Cut Line= 6
 345950.168090825423025.80169678345943.0416870125423044.42907715
345942.630493164 5423052.0993042 345935.503906255423071.68548584
345933.8593139655423076.47930908345943.4526977545423104.00952148
#Sta/Elev= 27
       0   29.01    7.36   27.99    11.8   26.94    19.2   27.25   19.94   27.15
   20.51   27.03   27.63   23.71   29.98   22.62   31.83   22.49   31.94   22.48
   38.35   22.18   45.08   22.46   45.34   22.54   45.58    22.6   48.47   23.41
   51.21   24.17   53.54   24.47   55.25   24.64    62.1   27.67   63.45    28.2
   63.58   28.29   66.78   30.33   70.04   32.45   71.67   33.69    76.8   38.62
   81.03   39.65   82.69   39.92
#Mann= 3 , 0 , 0
       0    .055       0   31.83    .035       0   45.58    .055       0
Bank Sta=31.83,45.58
XS Rating Curve= 0 ,0
Exp/Cntr=0.3,0.1