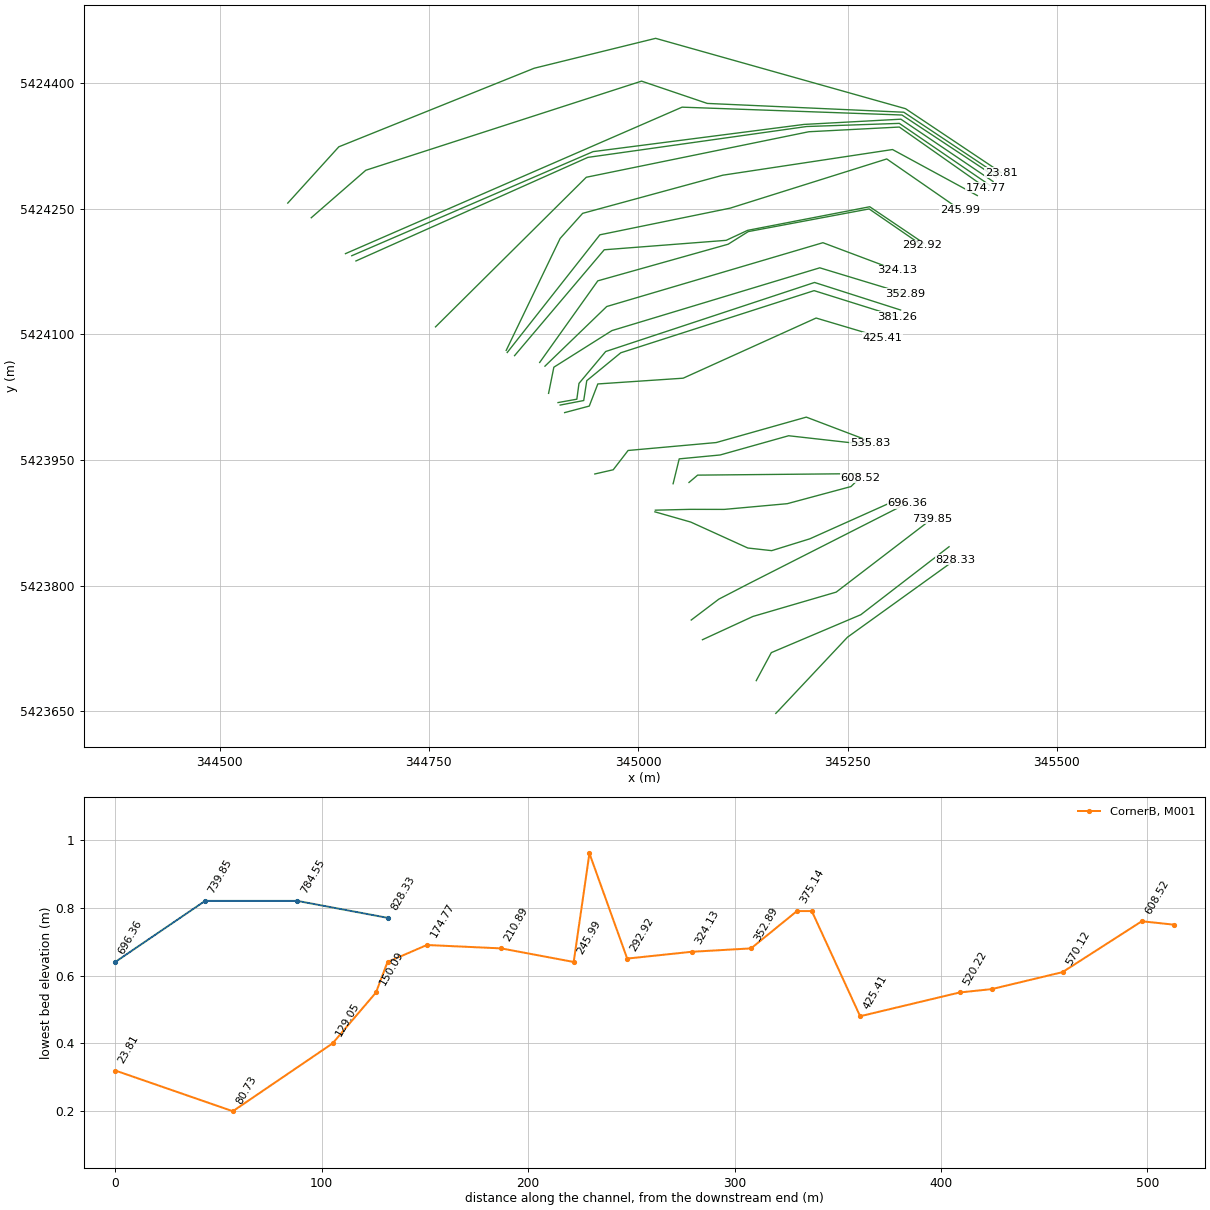
HEC-RAS study Corner_Brook2.prj: Corner_Brook2

--- Corner_Brook2.g02 (geometry) --- (continued)

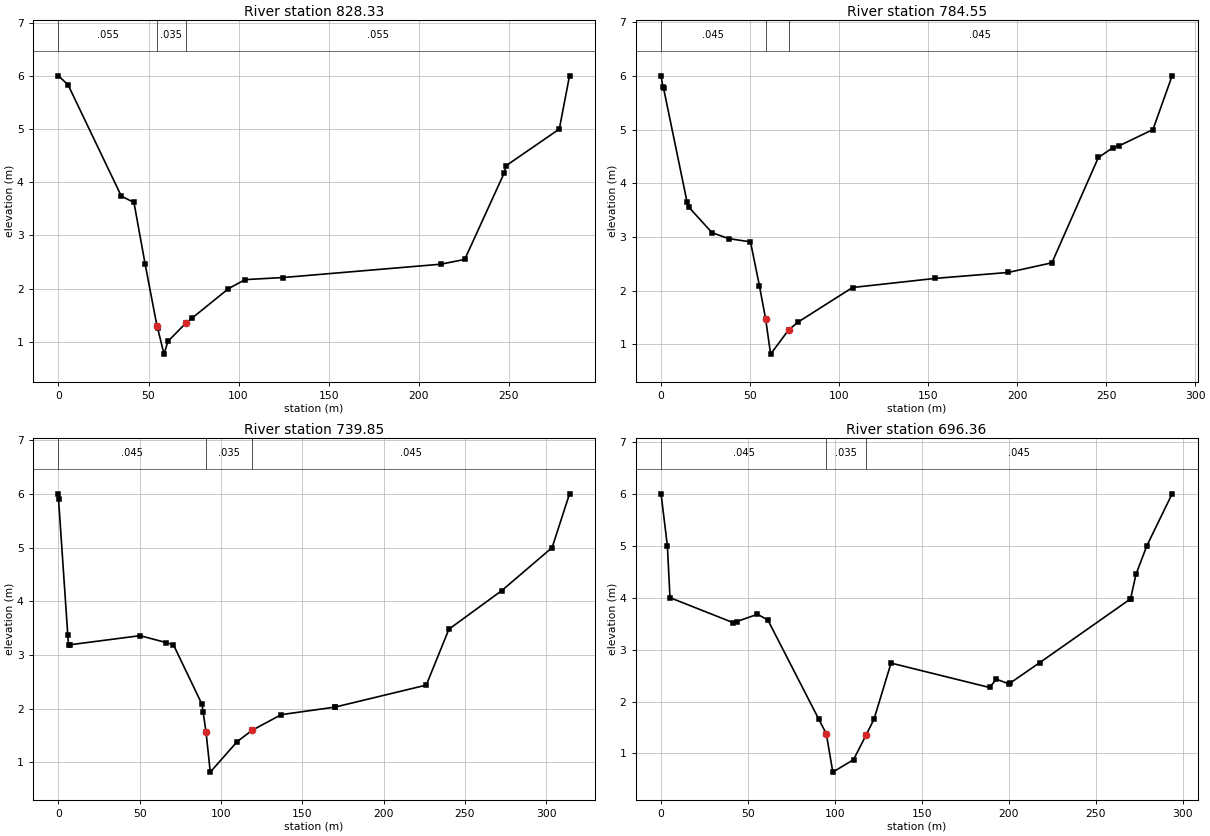
Type RM Length L Ch R = 1 ,828.33  ,50.77,43.78,31.08
XS GIS Cut Line= 4
      345164.294     5423647.316      345168.009     5423651.144
      345249.904     5423738.293      345378.862     5423831.031
#Sta/Elev= 20
       0       6    5.33    5.83   34.89    3.74   41.92    3.62   48.13    2.46
   54.75    1.29   55.06    1.26   58.59     .77   60.77    1.01   70.65    1.35
   73.94    1.44   94.38       2  103.58    2.17  124.92    2.21  212.31    2.46
  225.59    2.55  247.57    4.18  248.51    4.31   278.1       5  283.77       6
#Mann= 3 , 0 , 0
       0    .055       0   54.75    .035       0   70.65    .055       0
Bank Sta=54.75,70.65
XS Rating Curve= 0 ,0
Exp/Cntr=0.3,0.1

Type RM Length L Ch R = 1 ,784.55  ,56.66,44.7,40.93
XS GIS Cut Line= 5
      345140.972     5423686.402       345141.44     5423687.378
      345158.944     5423719.864      345265.845     5423765.156
      345371.196     5423846.325
#Sta/Elev= 22
       0       6    1.08    5.79    1.41    5.77   14.55    3.66   15.48    3.56
   28.65    3.08   37.98    2.97   50.24    2.91   55.27    2.09   58.77    1.47
   61.54     .82   71.65    1.27   77.13    1.42  107.56    2.06  154.08    2.23
  194.93    2.34  219.57    2.52  245.66    4.48   253.7    4.66  257.47     4.7
  276.33       5  287.08       6
#Mann= 3 , 0 , 0
       0    .045       0   58.77    .035       0   71.65    .045       0
Bank Sta=58.77,71.65
XS Rating Curve= 0 ,0
Exp/Cntr=0.3,0.1

Type RM Length L Ch R = 1 ,739.85  ,37.83,43.49,53.15
XS GIS Cut Line= 4
      345076.712     5423735.284      345137.039     5423763.084
      345236.439     5423792.134      345351.066      5423879.91
#Sta/Elev= 22
       0       6     .02    5.91    5.71    3.38    6.21    3.18    6.96    3.19
   50.21    3.36   66.42    3.23   70.74    3.19   88.31    2.08   89.02    1.93
    90.8   1.558   93.38     .82     110    1.39  119.17     1.6  137.07    1.89
  169.98    2.03  170.06    2.03  226.25    2.44  240.15    3.48  272.74     4.2
  303.67       5  314.36       6
#Mann= 3 , 0 , 0
       0    .045       0    90.8    .035       0  119.17    .045       0
Bank Sta=90.8,119.17
XS Rating Curve= 0 ,0
Exp/Cntr=0.3,0.1

Type RM Length L Ch R = 1 ,696.36  ,64.23,36.99,20.23
XS GIS Cut Line= 4
      345063.287     5423758.789      345096.278     5423783.749
      345132.515     5423802.491      345321.259     5423898.327
#Sta/Elev= 24
       0       6    3.63       5    5.14       4   41.37    3.52   43.54    3.54
   55.45    3.68    61.4    3.57   90.68    1.66   95.01    1.38   98.76     .64
  110.67     .88  117.99    1.36  122.44    1.66  132.24    2.74  188.88    2.27
  192.82    2.43  200.02    2.34  200.92    2.36  217.79    2.75  269.67    3.97
  269.99    3.98  273.09    4.45  279.33       5  293.85       6
#Mann= 3 , 0 , 0
       0    .045       0   95.01    .035       0  117.99    .045       0
Bank Sta=95.01,117.99
XS Rating Curve= 0 ,0
Exp/Cntr=0.3,0.1

River Reach=CornerB         ,M001

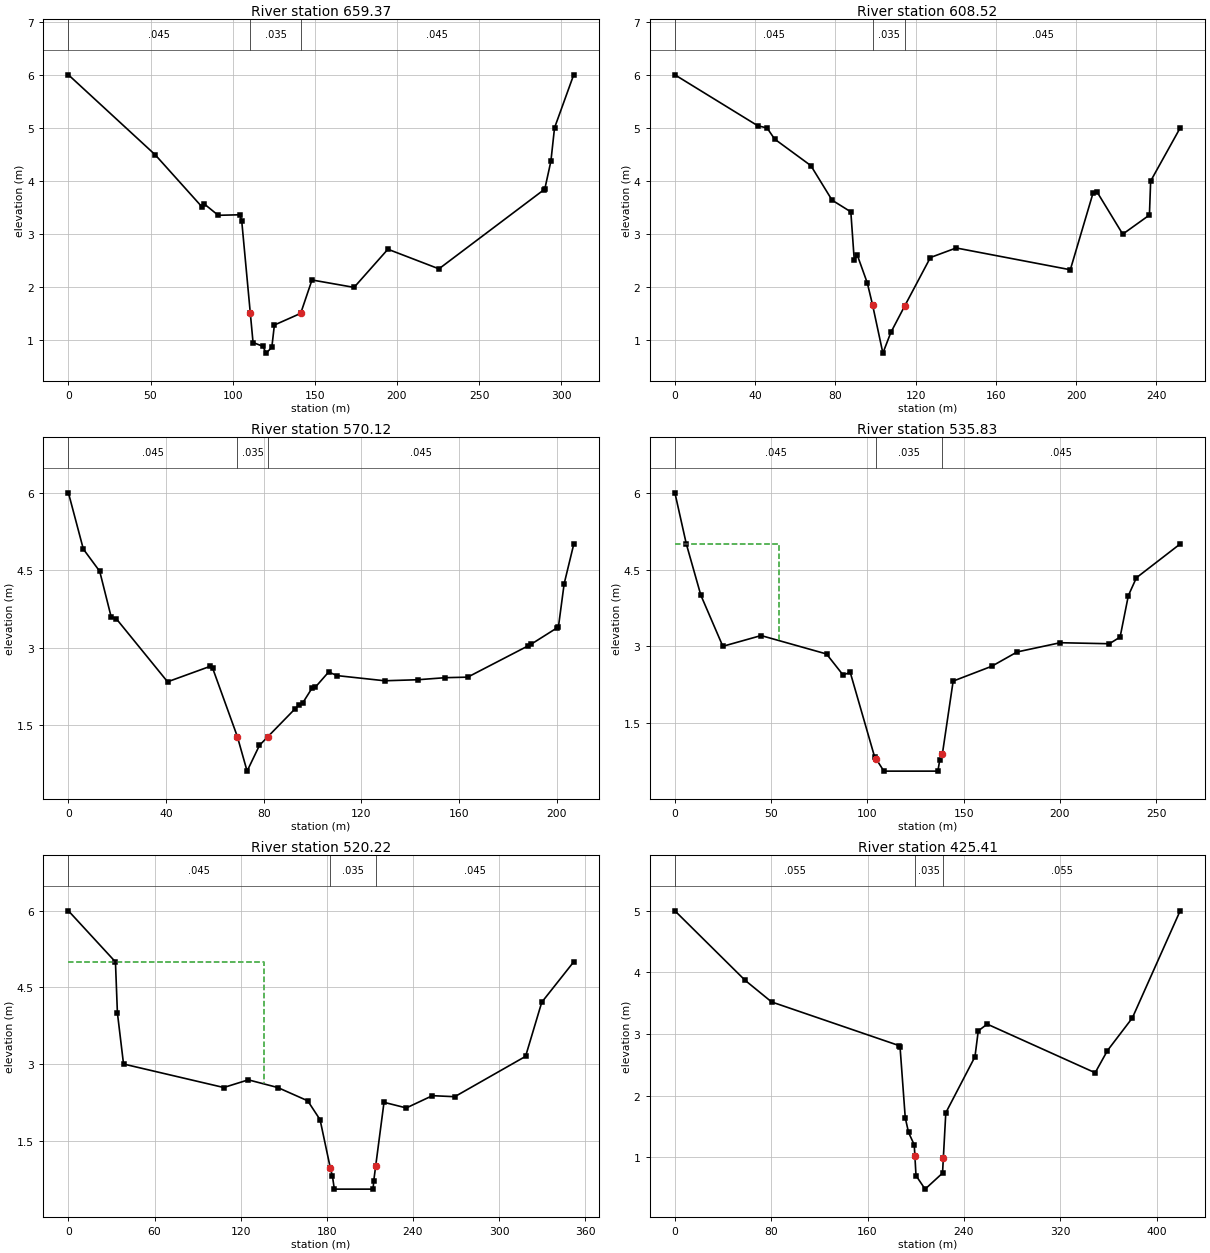
Type RM Length L Ch R = 1 ,659.37  ,6.01,15.44,16.77
XS GIS Cut Line= 6
      345019.923     5423888.005      345062.738     5423875.777
      345130.858       5423844.8      345159.361     5423841.647
      345204.919     5423855.768      345306.953     5423901.466
#Sta/Elev= 23
       0       6   52.88    4.49   81.27    3.51   82.46    3.57   91.21    3.35
  104.43    3.36  105.52    3.24  110.73   1.506   112.4     .95  118.32     .88
  120.42     .75  123.84     .86  125.39    1.28   141.4     1.5  148.29    2.13
  173.91    1.99  194.51    2.71  225.58    2.34  289.42    3.83  290.06    3.85
  293.74    4.37  295.96       5  307.62       6
#Mann= 3 , 0 , 0
       0    .045       0  110.73    .035       0   141.4    .045       0
Bank Sta=110.73,141.4
XS Rating Curve= 0 ,0
Exp/Cntr=0.3,0.1

Type RM Length L Ch R = 1 ,608.52  ,41.15,38.4,36.15
XS GIS Cut Line= 6
      345020.472     5423889.988      345061.819     5423890.967
      345102.693     5423890.907      345177.941      5423897.73
      345254.053     5423918.189      345265.011     5423928.885
#Sta/Elev= 23
       0       6   41.36    5.04   45.94       5   49.74    4.79    67.8    4.29
   78.37    3.64   87.72    3.42   89.41    2.52      91     2.6   95.94    2.08
   98.56   1.668   103.7     .76  107.68    1.15  114.64   1.652  127.39    2.56
  140.25    2.74  197.16    2.33  208.45    3.77   210.4     3.8  223.29       3
   236.6    3.36  237.21       4  251.92       5
#Mann= 3 , 0 , 0
       0    .045       0   98.56    .035       0  114.64    .045       0
Bank Sta=98.56,114.64
XS Rating Curve= 0 ,0
Exp/Cntr=0.3,0.1

Type RM Length L Ch R = 1 ,570.12  ,24.66,34.29,42.16
XS GIS Cut Line= 3
      345060.639     5423923.096      345070.954     5423931.842
      345264.424     5423933.617
#Sta/Elev= 29
       0       6    6.11    4.91   12.82    4.48   17.49     3.6   19.63    3.56
   40.62    2.34    58.1    2.64   59.04    2.61    69.2    1.28    73.2     .61
   78.27    1.11   81.71   1.277   92.91    1.82   94.33    1.89   95.97    1.93
   99.84    2.22  101.05    2.23  106.61    2.53  110.05    2.46  129.57    2.36
  143.11    2.38  154.45    2.42  163.57    2.43  188.48    3.04  189.63    3.07
  200.02    3.38  200.77    3.41   203.1    4.24     207       5
#Mann= 3 , 0 , 0
       0    .045       0    69.2    .035       0   81.71    .045       0
Bank Sta=69.2,81.71
XS Rating Curve= 0 ,0
Exp/Cntr=0.3,0.1

Type RM Length L Ch R = 1 ,535.83  ,15.48,15.61,15.92
XS GIS Cut Line= 6
      345041.667     5423921.564      345048.939     5423951.247
      345097.825      5423955.91      345179.627     5423978.872
      345254.305     5423970.477      345277.023      5423969.84
#Sta/Elev= 23
       0       6    5.94       5   13.47       4   24.91       3   44.79    3.21
   78.78    2.85   87.35    2.44    91.1    2.49  103.75     .84  104.68     .79
  108.59     .56  136.62     .56  137.63     .78  138.99      .9  144.57    2.32
  164.63    2.61  177.83    2.89  200.21    3.07  225.72    3.05  231.31    3.18
  235.59    3.99  239.78    4.34  262.51       5
#Mann= 3 , 0 , 0
       0    .045       0  104.68    .035       0  138.99    .045       0
#XS Ineff= 2 , 0
       0    54.3       5               0
Permanent Ineff=
       F       F
Bank Sta=104.68,138.99
XS Rating Curve= 0 ,0
Exp/Cntr=0.3,0.1

Type RM Length L Ch R = 1 ,520.22  ,48.43,48.15,48.46
XS GIS Cut Line= 6
      344948.158     5423933.212      344970.145     5423938.241
      344987.893     5423961.271      345093.136     5423970.747
      345200.729     5424001.107      345276.787     5423972.194
#Sta/Elev= 22
       0       6   32.75       5   34.12       4   38.38       3  108.19    2.54
  125.31    2.69  145.78    2.54  166.66    2.28  175.28    1.91  182.41    .966
  183.94      .8  185.21     .55  212.24     .55  212.62      .7  214.06    1.01
  219.82    2.25  235.36    2.14  253.53    2.38  269.09    2.36  318.43    3.15
  329.71    4.21  351.95       5
#Mann= 3 , 0 , 0
       0    .045       0  182.41    .035       0  214.06    .045       0
#XS Ineff= 2 , 0
       0   135.9       5               0
Permanent Ineff=
       F       F
Bank Sta=182.41,214.06
XS Rating Curve= 0 ,0
Exp/Cntr=0.3,0.1

Type RM Length L Ch R = 1 ,425.41  ,33.23,23.41,23.54
Node Photo=..\..\..\Corner Brook\Windshield Survey\CB photos\P1000632.JPG
XS GIS Cut Line= 6
      344912.125       5424006.5      344941.527     5424014.313
      344951.749     5424040.729      345053.649     5424047.601
      345212.438     5424119.444      345291.579     5424095.917
#Sta/Elev= 21
       0       5   58.39    3.87   80.33    3.52  186.34    2.81  186.98    2.79
   191.3    1.64  194.05     1.4  198.77     1.2  199.32   1.012  200.23      .7
  207.79     .48  222.27     .74  222.95     .99  224.98    1.72   249.2    2.63
  251.93    3.05  259.35    3.16  349.01    2.37  359.22    2.73  379.88    3.26
   419.6       5
#Mann= 3 , 0 , 0
       0    .055       0  199.32    .035       0  222.95    .055       0
Bank Sta=199.32,222.95
XS Rating Curve= 0 ,0
Exp/Cntr=0.3,0.1

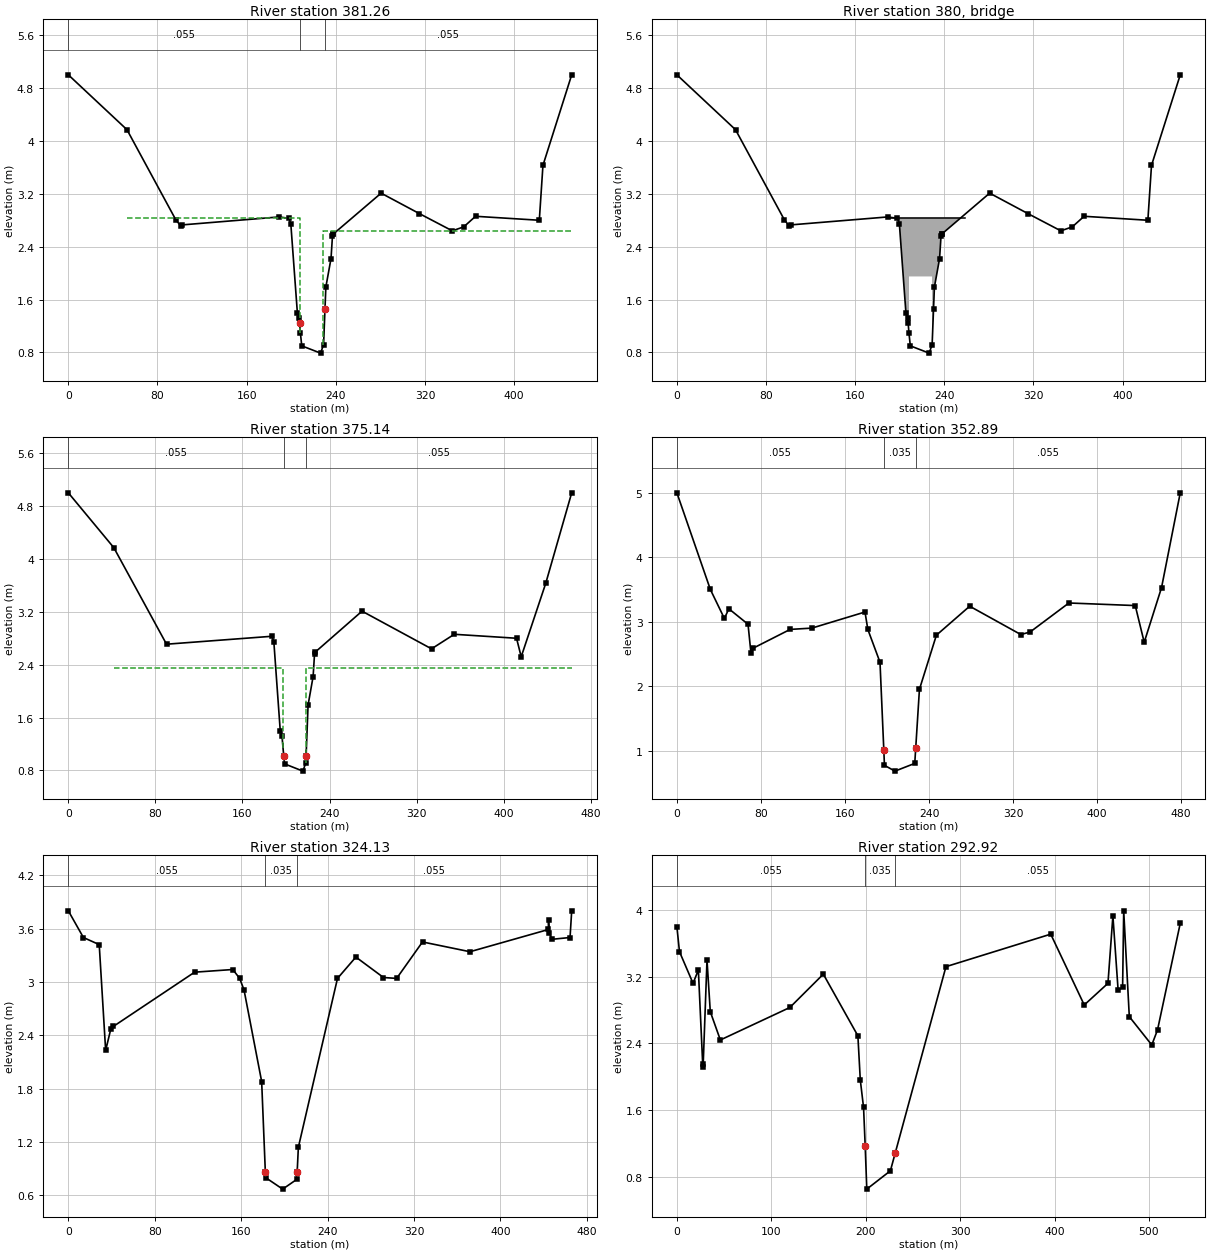
Type RM Length L Ch R = 1 ,381.26  ,7.2,7.2,7.2
Node Photo=..\..\..\Corner Brook\Windshield Survey\CB photos\P1000628.JPG
XS GIS Cut Line= 6
      344906.781       5424015.5      344934.904     5424020.931
      344938.538     5424044.632      344979.135     5424077.939
      345210.052     5424152.158       345309.16     5424121.075
#Sta/Elev= 29
       0       5   52.62    4.17   96.34    2.81  101.04    2.71  102.31    2.73
  189.03    2.85  197.87    2.83  199.63    2.75  205.53     1.4  207.13    1.32
   207.5    1.25  208.28    1.09  209.47      .9  226.38     .79  229.06     .92
  230.32    1.46   231.1    1.79  235.72    2.22  237.03    2.56  237.63    2.59
  237.64    2.59  280.68    3.21   315.1     2.9  344.56    2.64  354.82     2.7
  365.44    2.86  422.65     2.8  425.91    3.63  451.71       5
#Mann= 3 , 0 , 0
       0    .055       0   207.5    .035       0  230.32    .055       0
#XS Ineff= 2 , 0
   52.62  208.28    2.84  228.98   52.62    2.64
Permanent Ineff=
       F       F
Bank Sta=207.5,230.32
XS Rating Curve= 0 ,0
Exp/Cntr=0.5,0.3

Type RM Length L Ch R = 3 ,380     ,,,
Node Photo=..\..\..\Corner Brook\Windshield Survey\CB photos\P1000626.JPG
BEGIN DESCRIPTION:
Corner Brook Pulp & Paper #3 - Foot Bridge (Structure #2104)
END DESCRIPTION:
Bridge Culvert--1,0,-1,-1, 0
Deck Dist Width WeirC Skew NumUp NumDn MinLoCord MaxHiCord MaxSubmerge Is_Ogee
1.3,4,1.67,0, 6, 6, 2.64, , 0.98, 0, 0,0,,
  189.03  208.28  208.29  228.97  228.98  258.65
    2.84    2.84    2.84    2.84    2.84    2.84
      .9      .9    1.95    1.95      .9      .9
  178.22  197.47  197.48  218.16  218.17  247.84
    2.84    2.84    2.84    2.84    2.84    2.84
      .9      .9    1.95    1.95      .9      .9
BR Coef=-1 , 0 , 0 ,, 0 ,,,0.8,-1,,0,
WSPro=,,,, 1 ,,,, 0 ,,,, 0 ,,,,-1 ,-1 ,-1 , 0 , 0 , 0 , 0 , 0
BC Design=,, 0 ,, 0 ,,,,,,
BC Use User HTab Curves=0
BC User HTab FreeFlow(D)= 0

Type RM Length L Ch R = 1 ,375.14  ,22.33,22.25,22.11
Node Photo=..\..\..\Corner Brook\Windshield Survey\CB photos\P1000623.JPG
XS GIS Cut Line= 6
       344904.25       5424018.5      344926.692     5424022.519
      344929.243     5424041.353      344961.126     5424079.461
      345210.563     5424161.925      345313.322     5424129.032
#Sta/Elev= 23
       0       5   41.81    4.17   90.23    2.71  187.06    2.83  188.82    2.75
  194.72     1.4  196.32    1.32  197.94   1.015  198.66      .9  215.57     .79
  218.25     .92  218.48   1.019  220.29    1.79  224.91    2.22  226.22    2.56
  226.82    2.59  269.87    3.21  333.75    2.64  354.63    2.86  411.84     2.8
  416.13    2.52  438.65    3.63  462.52       5
#Mann= 3 , 0 , 0
       0    .055       0  197.94    .035       0  218.48    .055       0
#XS Ineff= 2 , 0
   41.81  197.47    2.35  218.17   41.81    2.35
Permanent Ineff=
       F       F
Bank Sta=197.94,218.48
XS Rating Curve= 0 ,0
Exp/Cntr=0.5,0.3

Type RM Length L Ch R = 1 ,352.89  ,29.06,28.77,28.44
Node Photo=..\..\..\..\Corner Brook\Windshield Survey\CB photos\P1000622.JPG
BEGIN DESCRIPTION:
Grade change in stream
END DESCRIPTION:
XS GIS Cut Line= 5
      344892.938       5424029.5      344899.236      5424060.72
      344968.628     5424104.451      345216.814     5424179.417
       345318.23     5424148.638
#Sta/Elev= 27
       0       5   31.85     3.5   45.19    3.05   49.47     3.2   67.71    2.96
   70.52    2.51   72.78    2.59  107.82    2.88  128.46     2.9  179.05    3.15
  181.74    2.88  193.33    2.37  196.94   1.014  197.56     .77  207.57     .68
  226.41      .8  227.35   1.042  230.87    1.95     247    2.79   278.7    3.24
   327.4     2.8  336.24    2.84  373.13    3.29  436.28    3.25  444.82    2.68
  461.33    3.53  479.12       5
#Mann= 3 , 0 , 0
       0    .055       0  196.94    .035       0  227.35    .055       0
Bank Sta=196.94,227.35
XS Rating Curve= 0 ,0
Exp/Cntr=0.3,0.1

Type RM Length L Ch R = 1 ,324.13  ,31.82,31.21,30.62
XS GIS Cut Line= 4
344888.6082763675424061.96929932344962.3762817385424133.18768311
345220.5648803715424209.40411377345308.7117309575424176.29370117
#Sta/Elev= 29
       0     3.8   13.94     3.5   28.59    3.42   34.54    2.23   39.29    2.47
   41.68     2.5  116.89    3.11  152.25    3.14  158.58    3.04  162.62    2.91
  178.94    1.88  182.35     .86  182.56      .8  198.39     .67  211.49     .78
   211.8    .859   212.9    1.14  249.12    3.04  266.15    3.28   291.7    3.05
  303.88    3.04  327.81    3.45  371.74    3.34  444.33    3.59  444.45     3.7
  445.07    3.55  447.87    3.48  464.37     3.5   465.9     3.8
#Mann= 3 , 0 , 0
       0    .055       0  182.35    .035       0   211.8    .055       0
Bank Sta=182.35,211.8
XS Rating Curve= 0 ,0
Exp/Cntr=0.3,0.1

Type RM Length L Ch R = 1 ,292.92  ,27.57,18.3,8.5
XS GIS Cut Line= 6
 344882.333923345424066.41009521344951.7260742195424163.86712646
345107.3892822275424207.59771729345131.3881225595424222.67687988
345275.7416992195424249.74768066345338.8267211915424206.36010742
#Sta/Elev= 30
       0     3.8    2.73     3.5   17.11    3.12   22.75    3.28   27.45    2.12
   27.87    2.15   31.89     3.4   35.37    2.78   46.02    2.44  119.64    2.83
  155.08    3.23  191.69    2.49  194.24    1.96   197.7    1.63  199.44   1.165
  201.12     .65  226.12     .87  231.16    1.08  284.97    3.32  395.93    3.71
  431.43    2.86  456.54    3.12  461.77    3.93  467.28    3.04  472.05    3.07
  473.22    3.99  479.15    2.72  502.95    2.38  509.01    2.56   533.1    3.84
#Mann= 3 , 0 , 0
       0    .055       0  199.44    .035       0  231.16    .055       0
Bank Sta=199.44,231.16
XS Rating Curve= 0 ,0
Exp/Cntr=0.3,0.1

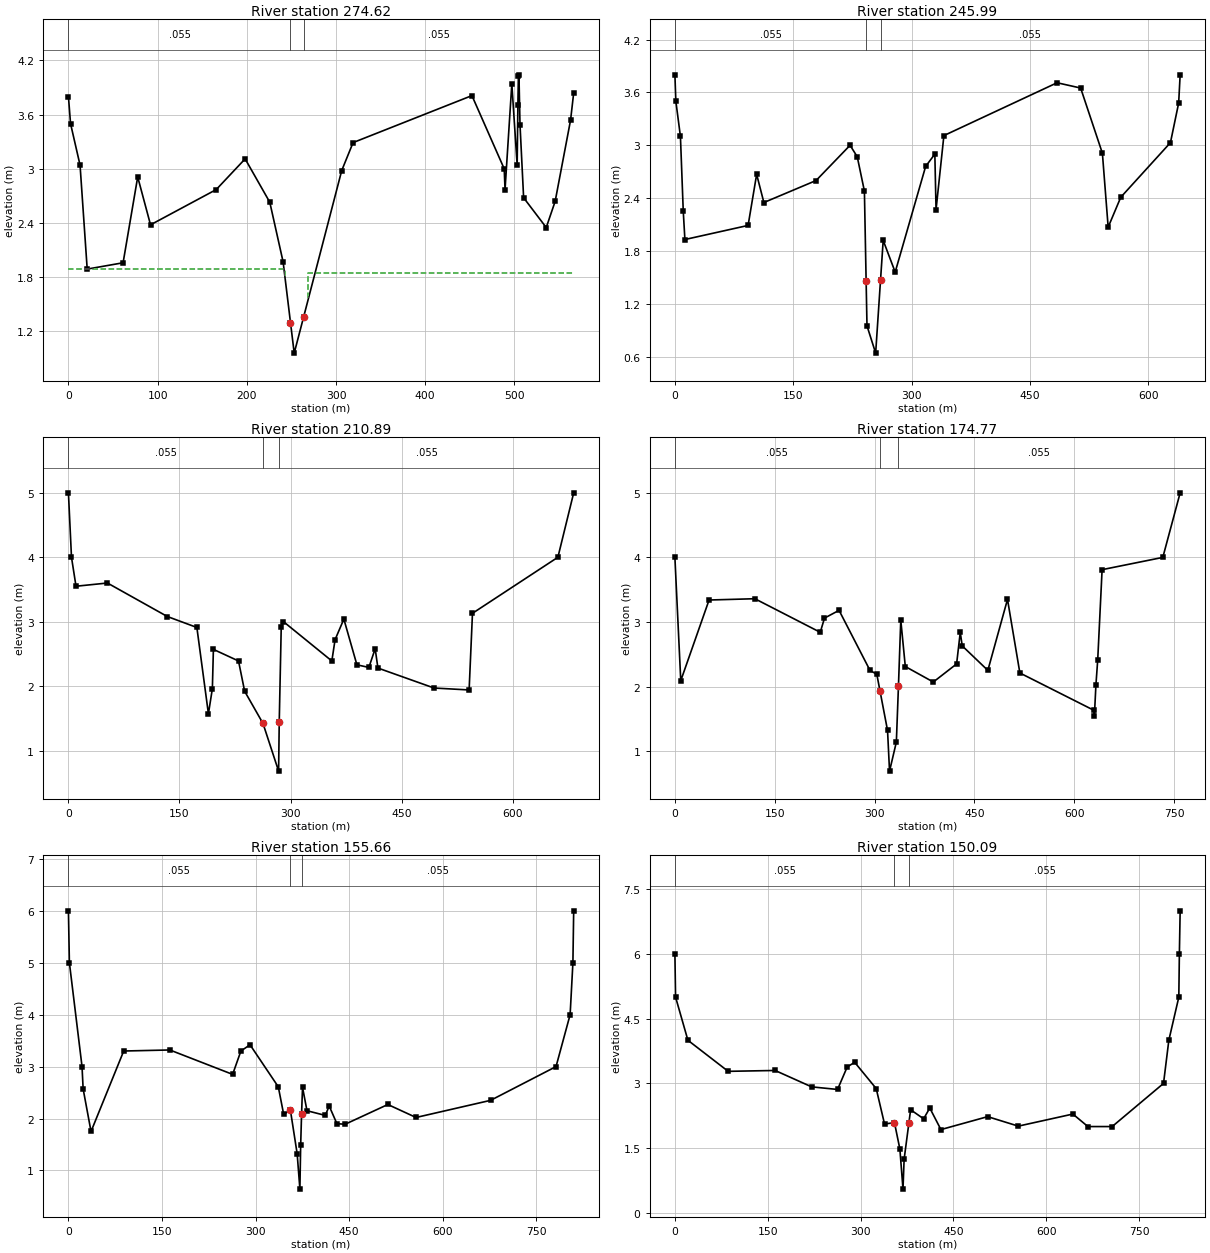
Type RM Length L Ch R = 1 ,274.62  ,7.58,7.62,7.75
Node Photo=..\..\..\..\Corner Brook\Windshield Survey\CB photos\P1000620.JPG
XS GIS Cut Line= 6
344852.3264770515424074.53149414344959.4033203135424200.96429443
345105.0242919925424212.23687744345130.6458740235424224.16027832
345276.4838867195424252.34350586345341.0532836915424208.77050781
#Sta/Elev= 30
       0     3.8    2.37     3.5   13.04    3.04   21.04    1.89   61.28    1.96
   77.66    2.91   92.03    2.38  165.68    2.77  198.09    3.11  225.74    2.63
  240.67    1.97  248.95   1.298  253.11     .96  263.72   1.362  306.36    2.98
   319.1    3.29  452.36    3.81  488.54       3  489.47    2.77  497.08    3.94
  503.06    3.04  503.88    3.71  504.45    4.03  505.06    4.04  506.24    3.49
   510.3    2.68  535.66    2.35  545.66    2.64  562.95    3.54  566.43    3.84
#Mann= 3 , 0 , 0
       0    .055       0  248.95    .035       0  263.72    .055       0
#XS Ineff= 2 , 0
       0  242.99    1.89  269.06       0    1.85
Permanent Ineff=
       F       F
Bank Sta=248.95,263.72
XS Rating Curve= 0 ,0
Exp/Cntr=0.5,0.3

Type RM Length L Ch R = 1 ,245.99  ,31.94,35.1,38.27
XS GIS Cut Line= 5
      344843.574      5424078.28      344954.227     5424218.843
       345109.89     5424250.704      345296.811     5424309.428
      345384.333      5424248.83
#Sta/Elev= 30
       0     3.8     1.2     3.5    7.02     3.1    10.6    2.25   12.67    1.93
   92.75    2.09  103.58    2.67  112.74    2.35  178.89     2.6  221.94       3
  231.03    2.87  240.11    2.48  242.29   1.458  243.38     .95  254.36     .64
  260.54    1.47  263.91    1.92   279.1    1.56  317.69    2.76  329.35     2.9
  330.88    2.27  340.82    3.11  484.25    3.71  514.08    3.65  541.63    2.91
  548.95    2.07  564.92    2.41  627.86    3.03  638.27    3.48  640.16     3.8
#Mann= 3 , 0 , 0
       0    .055       0  242.29    .035       0  260.54    .055       0
Bank Sta=242.29,260.54
XS Rating Curve= 0 ,0
Exp/Cntr=0.3,0.1

Type RM Length L Ch R = 1 ,210.89  ,38.68,35.99,33.1
XS GIS Cut Line= 6
      344842.324     5424080.779      344906.715      5424214.47
      344933.596     5424244.456      345101.138     5424290.061
      345303.688     5424320.673      345404.963     5424265.697
#Sta/Elev= 28
       0       5    4.13       4   10.23    3.55   52.68     3.6  133.57    3.08
  173.47    2.91  189.06    1.57   194.4    1.96  195.79    2.57  229.71    2.39
  237.99    1.92  262.78    1.42  283.86     .68   284.7   1.438  287.41    2.92
  290.45       3  355.75    2.39  360.11    2.72  371.98    3.04  389.61    2.33
  405.78    2.29  414.27    2.58  417.98    2.28  493.81    1.97  541.16    1.94
  545.69    3.13  661.06       4  682.38       5
#Mann= 3 , 0 , 0
       0    .055       0  262.78    .035       0   284.7    .055       0
Bank Sta=262.78,284.7
XS Rating Curve= 0 ,0
Exp/Cntr=0.3,0.1

Type RM Length L Ch R = 1 ,174.77  ,22.25,19.11,16.6
XS GIS Cut Line= 5
      344757.928     5424108.891      344937.972     5424287.562
      345203.663     5424341.913      345311.815     5424347.536
      345414.965     5424275.068
#Sta/Elev= 30
       0       4    8.81    2.09   51.34    3.34  120.15    3.36  218.42    2.84
  224.78    3.06  246.67    3.18  293.16    2.25   303.4    2.19  308.15   1.934
  319.52    1.32  322.52     .69  332.76    1.14  335.93    2.01  339.41    3.03
  346.21    2.31   388.3    2.07  423.29    2.35  428.78    2.84  431.71    2.63
  470.25    2.25  499.77    3.35  518.36    2.21  629.98    1.63  630.35    1.55
  632.66    2.03  635.32    2.41  641.92    3.81  733.15       4   759.2       5
#Mann= 3 , 0 , 0
       0    .055       0  308.15    .035       0  335.93    .055       0
Bank Sta=308.15,335.93
XS Rating Curve= 0 ,0
Exp/Cntr=0.3,0.1

Type RM Length L Ch R = 1 ,155.66  ,6.01,5.58,5.11
Node Photo=..\..\..\Corner Brook\Windshield Survey\CB photos\P1000612.JPG
XS GIS Cut Line= 5
      344662.905     5424187.607      344939.848     5424311.302
      345201.162     5424348.161      345311.815     5424351.909
      345420.591     5424277.567
#Sta/Elev= 30
       0       6    1.54       5    21.8       3   23.57    2.57   36.22    1.75
   88.59     3.3   162.5    3.32  263.15    2.85  276.38     3.3  291.02    3.42
  336.33    2.61  344.93    2.08  355.72    2.16  366.56    1.32  370.92     .64
  372.17   1.483  373.59    2.08  375.16     2.6  382.29    2.15  411.58    2.06
  417.88    2.24  430.26     1.9  443.51    1.89  511.86    2.27  557.05    2.02
  676.56    2.35  781.39       3  803.97       4  808.43       5  809.68       6
#Mann= 3 , 0 , 0
       0    .055       0  355.72    .035       0  373.59    .055       0
#XS Ineff= 2 , 0
       0  355.72    2.08  373.59       0    1.89
Permanent Ineff=
       F       F
Bank Sta=355.72,373.59
XS Rating Curve= 0 ,0
Exp/Cntr=0.4,0.2

Type RM Length L Ch R = 1 ,150.09  ,8.19,21.03,33.59
Node Photo=..\..\..\Corner Brook\Windshield Survey\CB photos\P1000610.JPG
XS GIS Cut Line= 5
      344657.904     5424193.854      344946.099     5424318.174
      345198.037     5424350.659       345313.69     5424356.907
      345423.717     5424282.565
#Sta/Elev= 30
       0       6     1.1       5   21.03       4   86.09    3.28  161.96     3.3
  221.01    2.92  262.85    2.86   278.4    3.38  290.49    3.49  325.33    2.88
  338.75    2.06  354.83    2.09  363.56    1.48  368.61     .55  370.41    1.24
  378.07   2.077  380.93    2.39  401.95    2.18   411.9    2.43  429.89    1.93
  505.42    2.23  554.96    2.01  643.15    2.29  667.43       2  706.63       2
  789.62       3  798.21       4  814.33       5  815.24       6   816.5       7
#Mann= 3 , 0 , 0
       0    .055       0  354.83    .035       0  378.07    .055       0
#XS Ineff= 2 , 0
       0  354.83    2.06  378.07       0    1.91
Permanent Ineff=
       F       F
Bank Sta=354.83,378.07
XS Rating Curve= 0 ,0
Exp/Cntr=0.4,0.2

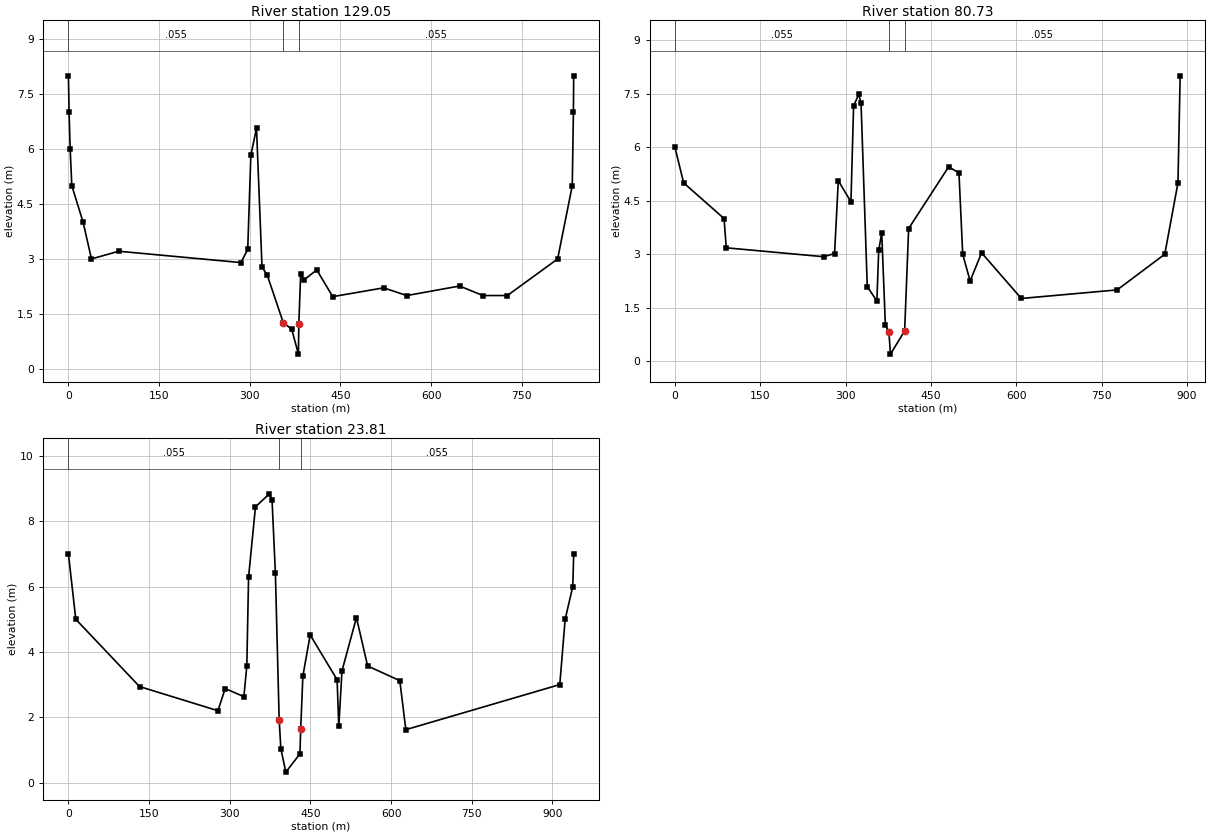
Type RM Length L Ch R = 1 ,129.05  ,48.12,48.32,47.32
XS GIS Cut Line= 5
      344650.402     5424196.353      344946.099     5424325.046
      345052.376     5424371.275       345314.94     5424361.904
      345427.468     5424287.562
#Sta/Elev= 30
       0       8    1.08       7     2.9       6    5.57       5   24.33       4
   38.08       3   83.26    3.21  285.42     2.9  296.64    3.26  301.83    5.83
   311.2    6.57   320.3    2.78  329.09    2.55  355.45    1.26  369.46    1.08
  380.53      .4  381.21   1.234  384.24    2.58  390.04    2.43  410.86     2.7
  437.31    1.97   521.5    2.21  559.94       2  647.23    2.26  685.77       2
  726.23       2  809.44       3  833.62       5  835.52       7  835.98       8
#Mann= 3 , 0 , 0
       0    .055       0  355.45    .035       0  381.21    .055       0
Bank Sta=355.45,381.21
XS Rating Curve= 0 ,0
Exp/Cntr=0.3,0.1

Type RM Length L Ch R = 1 ,80.73   ,61.44,56.94,50.51
XS GIS Cut Line= 6
      344609.509     5424239.208      344674.667     5424295.925
      345003.964     5424402.357      345082.434     5424375.749
      345317.145     5424365.246      345430.647     5424289.623
#Sta/Elev= 30
       0       6   15.38       5   86.42       4   90.25    3.18  261.49    2.93
  280.63    3.02  287.18    5.06   309.4    4.47  314.06    7.16  323.23    7.48
  327.16    7.23   338.1    2.09  354.99    1.69  358.19    3.11  363.51     3.6
  369.86    1.03  376.11     .81  378.91      .2  403.76     .85  410.81    3.72
  481.14    5.45  499.25    5.28  505.82       3  518.84    2.25     539    3.04
  608.87    1.76  777.28       2  860.94       3  884.12       5  887.98       8
#Mann= 3 , 0 , 0
       0    .055       0  376.11    .035       0  403.76    .055       0
Bank Sta=376.11,403.76
XS Rating Curve= 0 ,0
Exp/Cntr=0.3,0.1

Type RM Length L Ch R = 1 ,23.81   ,26,23.8,24.26
XS GIS Cut Line= 6
      344581.484     5424256.713      344642.438     5424323.933
      344875.748     5424417.761      345020.779     5424453.472
      345319.247     5424369.447       345433.45     5424293.124
#Sta/Elev= 30
       0       7   13.67       5  132.18    2.94  278.01     2.2   291.5    2.88
  326.26    2.63  331.69    3.57  334.97    6.29  347.76    8.44  373.57    8.84
  378.62    8.65  384.84    6.41  391.86    1.93  394.97    1.04  404.26     .32
  430.52     .88  431.89    1.65  435.95    3.26  449.49    4.52  499.58    3.15
  502.73    1.72  508.67    3.42  535.57    5.05  556.33    3.57   616.2    3.12
  627.38    1.62  913.66       3  923.64       5  937.79       6  939.51       7
#Mann= 3 , 0 , 0
       0    .055       0  391.86    .035       0  431.89    .055       0
Bank Sta=391.86,431.89
XS Rating Curve= 0 ,0
Exp/Cntr=0.3,0.1

--- Corner_Brook2.g03 (geometry) ---

Geom Title=CB_with_below_waterline_gates
Program Version=4.10
BEGIN GEOM DESCRIPTION:
Created based on a TIN with 1 z tolerance
END GEOM DESCRIPTION:

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
River Reach=BellsB          ,TR001

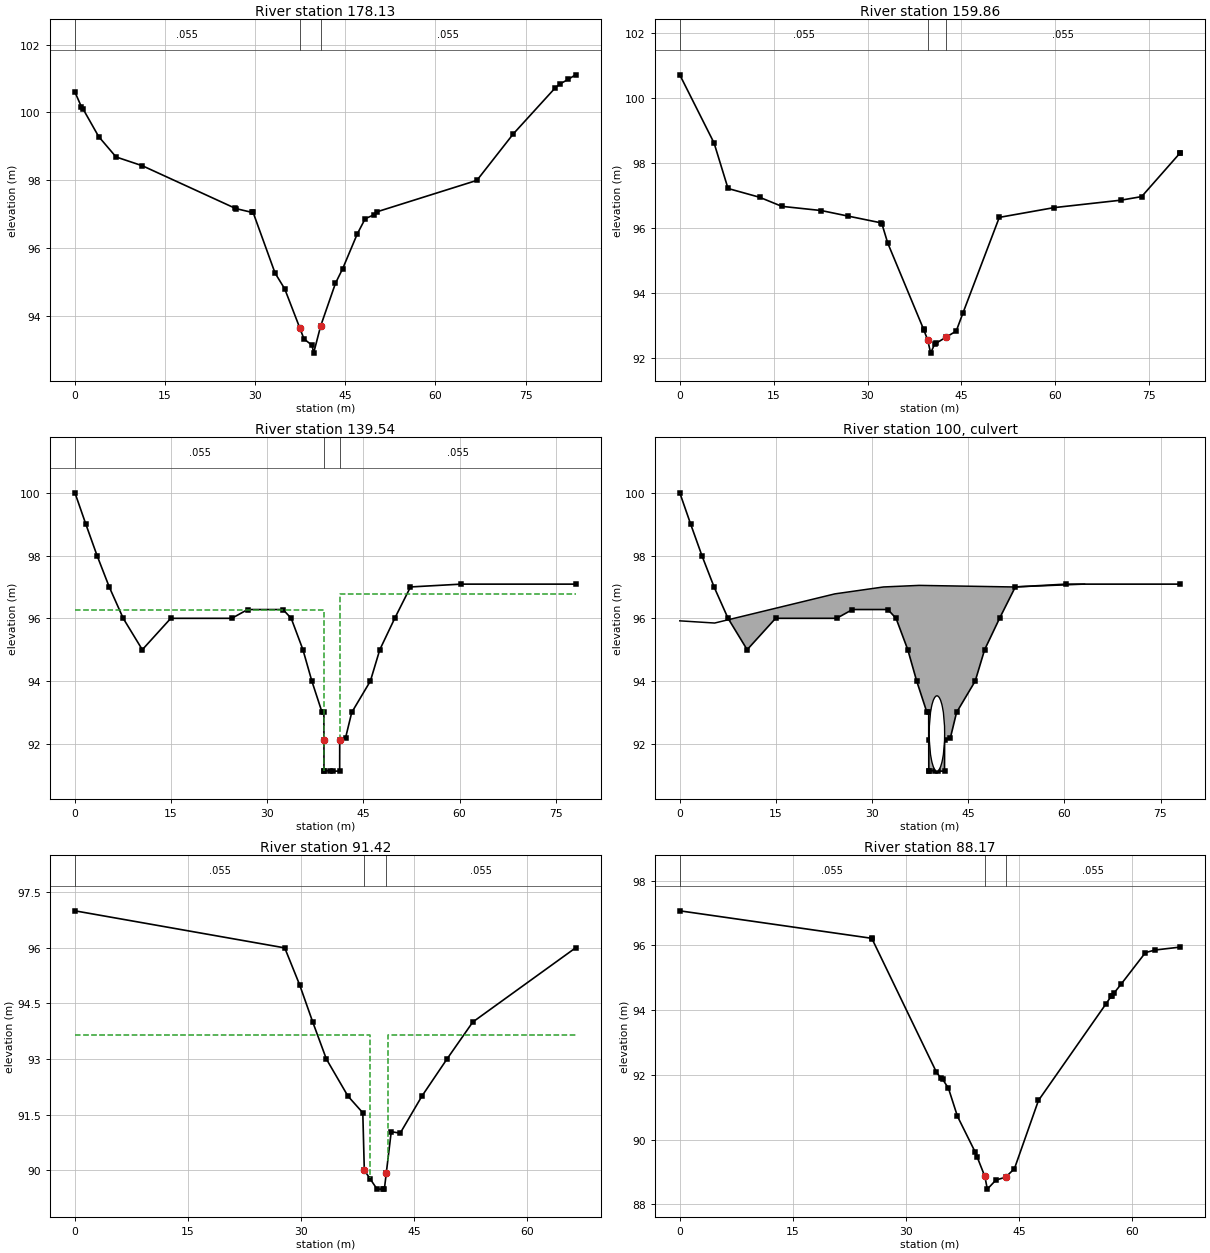
Type RM Length L Ch R = 1 ,178.13  ,18.25,18.27,18.06
XS GIS Cut Line= 6
344234.4996948245422720.95068359344238.9260864265422731.27270508
344238.0407104495422749.41009521344253.2380981455422758.25750732
344279.2062988285422758.69989014344288.9442749025422755.16088867
#Sta/Elev= 29
       0   100.6    1.07  100.17    1.36   100.1    3.95   99.29    6.84   98.69
   11.23   98.43   26.64   97.18   26.75   97.17   29.39   97.06   29.64   97.06
    33.3   95.27   34.92    94.8    37.4   93.66   38.11   93.33   39.46   93.14
   39.72   92.91   40.89  93.708   43.36   94.97   44.56    95.4   46.98   96.42
    48.3   96.87   49.69   96.98   50.19   97.07   66.89      98   72.95   99.37
    79.9  100.72   80.71  100.84   82.12  100.98   83.31  101.11
#Mann= 3 , 0 , 0
       0    .055       0    37.4    .035       0   40.89    .055       0
Bank Sta=37.4,40.89
XS Rating Curve= 0 ,0
Exp/Cntr=0.3,0.1

Type RM Length L Ch R = 1 ,159.86  ,19.69,20.32,20.7
XS GIS Cut Line= 2
344199.8156738285422748.48608398344269.362304688 5422788.0244751
#Sta/Elev= 25
       0  100.72    5.48   98.62    7.71   97.22   12.75   96.95   16.31   96.67
   22.63   96.54   26.89   96.37   32.21   96.16   32.29   96.14   33.23   95.54
   38.95   92.89      39   92.86   39.61   92.56   40.09   92.15   40.73   92.43
      41   92.46   42.58  92.644   44.18   92.83   45.24   93.38   51.06   96.33
   59.79   96.63    70.5   96.86   73.81   96.97   79.98   98.32      80   98.32
#Mann= 3 , 0 , 0
       0    .055       0   39.61    .035       0   42.58    .055       0
Bank Sta=39.61,42.58
XS Rating Curve= 0 ,0
Exp/Cntr=0.3,0.1

Type RM Length L Ch R = 1 ,139.54  ,49.06,48.13,33.83
Node Photo=..\..\..\..\Corner Brook\Windshield Survey\CB photos\P1000709.JPG
XS GIS Cut Line= 5
       344187.04     5422775.179      344200.338      5422782.01
      344217.269     5422780.434      344217.269     5422780.434
      344255.016     5422806.982
#Sta/Elev= 30
       0     100     1.7      99    3.45      98    5.35      97    7.53      96
   10.51      95   14.95      96   24.47      96   26.94   96.28   32.46   96.28
   33.74      96   35.57      95   36.96      94   38.56      93   38.84   93.02
  38.845   92.11   38.85   91.14   38.92   91.14   39.81   91.14   40.26   91.13
    41.3   91.13   41.31   92.11   42.23    92.2   43.18      93   46.09      94
   47.56      95   49.89      96   52.35      97   60.24   97.09    78.1   97.09
#Mann= 3 , 0 , 0
       0    .055       0  38.845    .035       0   41.31    .055       0
#XS Ineff= 2 , 0
       0   38.92   96.28   41.32       0   96.78
Permanent Ineff=
       F       F
Bank Sta=38.845,41.31
XS Rating Curve= 0 ,0
Exp/Cntr=0.5,0.3

Type RM Length L Ch R = 2 ,100     ,,,
Node Photo=..\..\..\..\Corner Brook\Windshield Survey\CB photos\P1000708.JPG
BEGIN DESCRIPTION:
O'Connell Drive/Mount Batten Road (Structure #2130)
END DESCRIPTION:
Bridge Culvert--1,0,-1,-1, 0
Deck Dist Width WeirC Skew NumUp NumDn MinLoCord MaxHiCord MaxSubmerge Is_Ogee
12,19.2,1.67,0, 7, 8, 95, , 0.98, 0, 0.73,0.57,,
       0    5.44    24.2   31.78   37.33   52.04   63.15
   95.92   95.85   96.78      97   97.05      97   97.09
                                                        
       0   19.48   28.32   36.51   40.19   45.24   49.91   66.38
      97   95.92   95.85      96      96   95.71   95.42      97
                                                                
BR Coef=-1 , 0 , 0 ,, 0 ,,,0.8,-1,,0,
WSPro=,,,, 1 ,,,, 0 ,,,, 0 ,,,,-1 ,-1 ,-1 , 0 , 0 , 0 , 0 , 0
Culvert=1,2.4,,44.2,0.03,0.7,1,2,2,91.13,40.12,89.49,40.27,Culvert #1  , 0 ,1.4
Culvert Bottom n=0.03
BC Design=,, 0 ,, 0 ,,,,,,
BC Use User HTab Curves=0
BC User HTab FreeFlow(D)= 0

Type RM Length L Ch R = 1 ,91.42   ,3.23,3.25,0.95
Node Photo=..\..\..\..\Corner Brook\Windshield Survey\CB photos\P1000713.JPG
XS GIS Cut Line= 6
344176.3275146485422793.74768066344187.5899047855422816.60327148
344192.6146850595422823.52929688344201.1046752935422826.99230957
344212.5405273445422816.77648926344218.2583007815422811.40887451
#Sta/Elev= 19
       0      97   27.82      96    29.8      95   31.53      94   33.34      93
    36.2      92   38.17   91.55   38.37      90   39.17  89.759   40.06   89.49
   40.82   89.49   41.03   89.49   41.29  89.933   41.94   91.04   43.13      91
   46.01      92   49.33      93   52.76      94   66.38      96
#Mann= 3 , 0 , 0
       0    .055       0   38.37    .035       0   41.29    .055       0
#XS Ineff= 2 , 0
       0   39.07   93.65   41.47       0   93.65
Permanent Ineff=
       F       F
Bank Sta=38.37,41.29
XS Rating Curve= 0 ,0
Exp/Cntr=0.5,0.3

Type RM Length L Ch R = 1 ,88.17   ,2.5,4.05,10.03
XS GIS Cut Line= 6
344174.2482910165422796.34509277344185.5106811525422819.20068359
344190.5355224615422826.12652588344199.0255126955422829.58947754
344210.4613037115422819.37371826344216.1790771485422814.00610352
#Sta/Elev= 24
       0   97.07   25.47   96.22   25.48   96.21   34.04   92.08   34.66   91.89
   34.86   91.86   35.62   91.59   36.82   90.72   39.14   89.63   39.42   89.47
   40.45  88.864   40.78   88.47   41.92   88.75   43.21   88.84   44.37    89.1
   47.56   91.21    56.5   94.19   57.23   94.44   57.28   94.45   57.55   94.52
   58.54   94.81   61.75   95.78   63.05   95.86   66.38   95.95
#Mann= 3 , 0 , 0
       0    .055       0   40.45    .035       0   43.21    .055       0
Bank Sta=40.45,43.21
XS Rating Curve= 0 ,0
Exp/Cntr=0.3,0.1

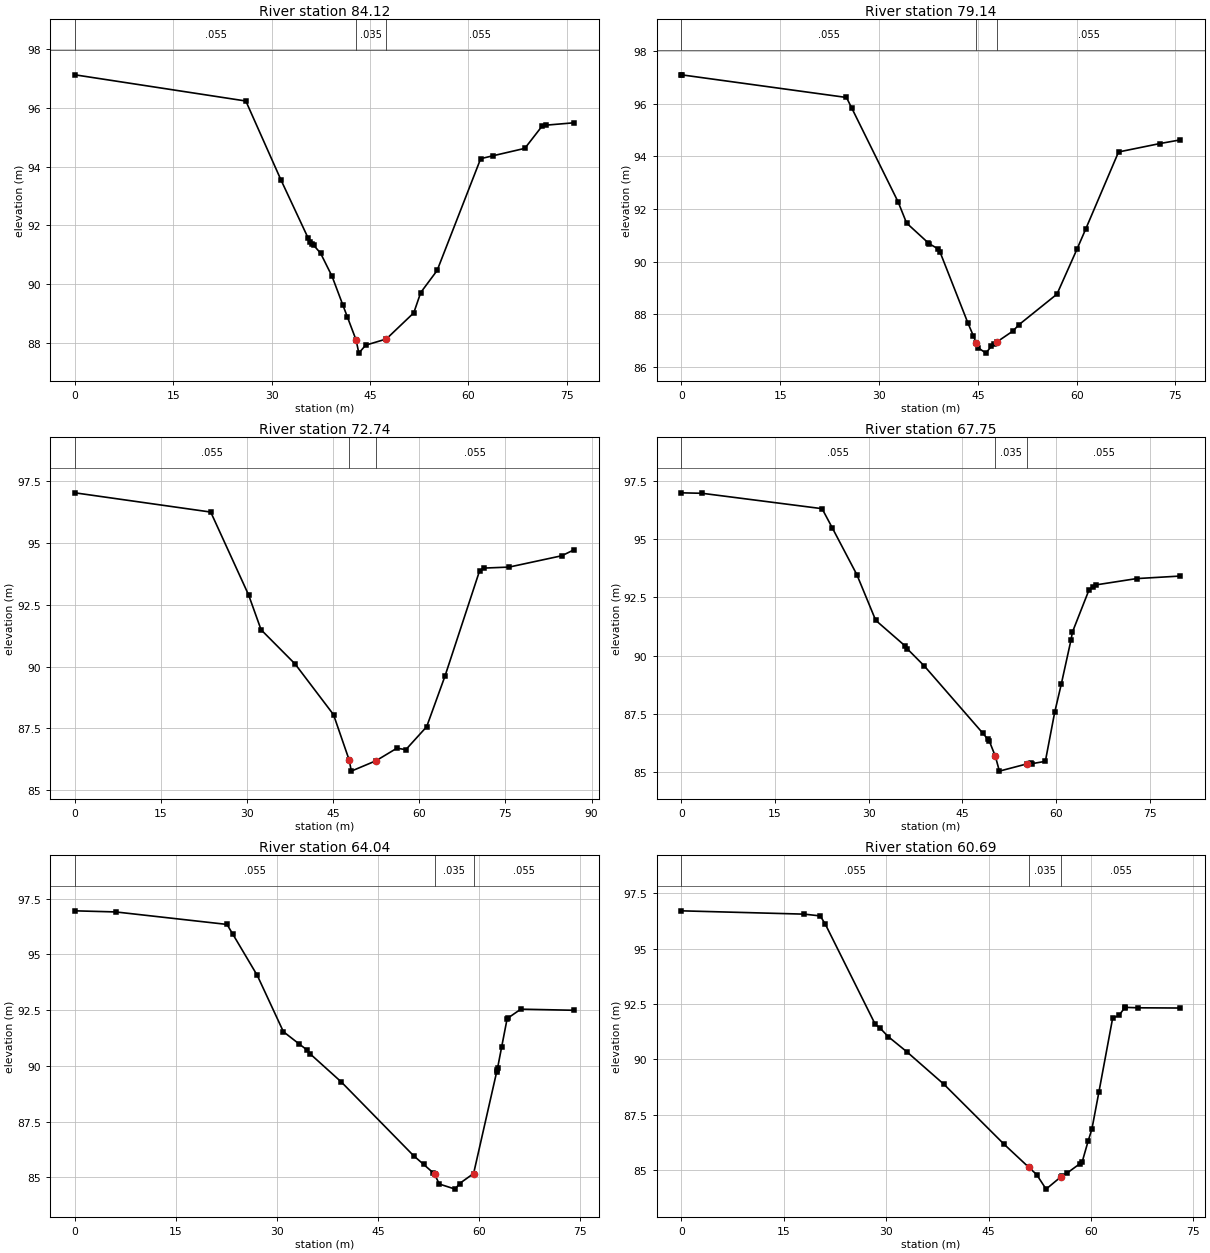
Type RM Length L Ch R = 1 ,84.12   ,3.03,4.98,8.8
XS GIS Cut Line= 6
344172.6889038095422796.34509277344187.4166870125422824.04870605
344193.3076782235422831.49407959344199.372070313 5422834.0914917
344213.0603027345422825.26068115344222.7633056645422817.64227295
#Sta/Elev= 24
       0   97.12   26.05   96.23   31.38   93.56   35.51   91.59   35.77   91.44
    36.2   91.36   36.38   91.33   37.44   91.06    39.2   90.27   40.87   89.28
   41.55   88.88   42.87  88.102   43.28   87.66   44.32   87.93   47.47   88.14
   51.66   89.03   52.72   89.72   55.22   90.47   61.86   94.27   63.76   94.37
   68.59   94.62    71.2   95.37   71.88   95.41   76.09   95.49
#Mann= 3 , 0 , 0
       0    .055       0   42.87    .035       0   47.47    .055       0
Bank Sta=42.87,47.47
XS Rating Curve= 0 ,0
Exp/Cntr=0.3,0.1

Type RM Length L Ch R = 1 ,79.14   ,5.7,6.39,8.69
XS GIS Cut Line= 6
344172.5156860355422797.38391113344184.6442871095422820.23950195
344189.4959106455422830.80151367344192.6146850595422836.86169434
 344198.505676275422838.07373047344222.416687012 5422829.4163208
#Sta/Elev= 26
       0    97.1     .01    97.1   25.05   96.24   25.87   95.83    32.9   92.27
   34.18   91.47    37.5   90.71   37.59   90.69   38.88    90.5   39.24   90.38
   43.48   87.68   44.31   87.19   44.77    86.9   45.02   86.74   46.21   86.53
   47.05   86.79   47.47   86.88   47.98   86.97   50.33   87.37   51.24   87.61
   57.01   88.77   60.07   90.49   61.37   91.24   66.36   94.17   72.64   94.49
   75.76   94.63
#Mann= 3 , 0 , 0
       0    .055       0   44.77    .035       0   47.98    .055       0
Bank Sta=44.77,47.98
XS Rating Curve= 0 ,0
Exp/Cntr=0.3,0.1

Type RM Length L Ch R = 1 ,72.74   ,2.71,4.99,10
XS GIS Cut Line= 6
344171.8225097665422799.11547852344184.1245117195422820.93212891
344188.6295166025422839.97851563344193.3076782235422843.78771973
344216.6989135745422842.22930908344227.2681274415422834.95709229
#Sta/Elev= 18
       0   97.04   23.65   96.26   30.25    92.9   32.42   91.49   38.36    90.1
   45.04   88.05   47.79  86.196   48.14   85.76   52.44   86.18   56.09   86.69
   57.64   86.63   61.27   87.56   64.46   89.61   70.49   93.88   71.28   93.99
   75.63   94.03   84.82   94.49   86.94   94.73
#Mann= 3 , 0 , 0
       0    .055       0   47.79    .035       0   52.44    .055       0
Bank Sta=47.79,52.44
XS Rating Curve= 0 ,0
Exp/Cntr=0.3,0.1

Type RM Length L Ch R = 1 ,67.75   ,2.94,3.71,5.31
XS GIS Cut Line= 5
344170.9561157235422800.32751465344182.3919067385422821.62469482
344188.1096801765422845.86547852344201.4512939455422856.25427246
344215.1395263675422858.85168457
#Sta/Elev= 27
       0   96.98    3.31   96.96   22.52    96.3   24.17   95.47   28.09   93.47
   31.11   91.51   35.87    90.4   36.19   90.28    38.9   89.55   48.29   86.66
   49.08    86.4   49.29   86.34   50.28   85.67   50.92   85.04   55.32   85.35
   55.94   85.37   56.12   85.36   58.28   85.46   59.78   87.57   60.83   88.77
   62.39   90.67   62.61      91   65.25    92.8   65.99   92.96   66.38   93.03
   72.89    93.3   79.92   93.41
#Mann= 3 , 0 , 0
       0    .055       0   50.28    .035       0   55.32    .055       0
Bank Sta=50.28,55.32
XS Rating Curve= 0 ,0
Exp/Cntr=0.3,0.1

Type RM Length L Ch R = 1 ,64.04   ,3.68,3.35,4.35
XS GIS Cut Line= 5
344169.7432861335422800.50048828344180.4859008795422821.27832031
344182.5651245125422830.97467041344185.8572998055422847.59692383
344200.5848999025422866.29711914
#Sta/Elev= 26
       0   96.95    6.05    96.9   22.56   96.34   23.39   95.92   27.06   94.05
   30.93   91.53   33.31   90.97    34.4   90.72   34.92   90.53   39.51   89.28
   50.25   85.97   51.74   85.58   53.17    85.2   53.39   85.13   54.06    84.7
   56.42   84.47   57.07   84.72   59.16   85.17   62.57   89.71   62.64   89.81
   62.73   89.92   63.32   90.84   64.14   92.12    64.2   92.13   66.17   92.54
   74.06   92.49
#Mann= 3 , 0 , 0
       0    .055       0   53.39    .035       0   59.16    .055       0
Bank Sta=53.39,59.16
XS Rating Curve= 0 ,0
Exp/Cntr=0.3,0.1

Type RM Length L Ch R = 1 ,60.69   ,4.56,3.94,4.31
XS GIS Cut Line= 5
344164.1987304695422804.13671875344179.4462890635422833.39868164
 344182.738281255422847.25067139344187.9362792975422857.12011719
344197.6392822275422868.20172119
#Sta/Elev= 27
       0   96.71   18.01   96.56   20.34   96.48   21.09    96.1    28.4   91.58
   29.05   91.43   30.29   91.03      33   90.35   38.48   88.87   47.23   86.18
   50.88   85.13   52.04    84.8   53.43   84.14   55.58   84.69   55.79   84.72
   56.44   84.85   58.39   85.29   58.71   85.36   59.59   86.31   60.14   86.85
   61.16   88.51   63.18   91.86   64.13   91.99   64.96   92.34   65.02   92.35
   66.87   92.33   73.12   92.32
#Mann= 3 , 0 , 0
       0    .055       0   50.88    .035       0   55.58    .055       0
Bank Sta=50.88,55.58
XS Rating Curve= 0 ,0
Exp/Cntr=0.3,0.1