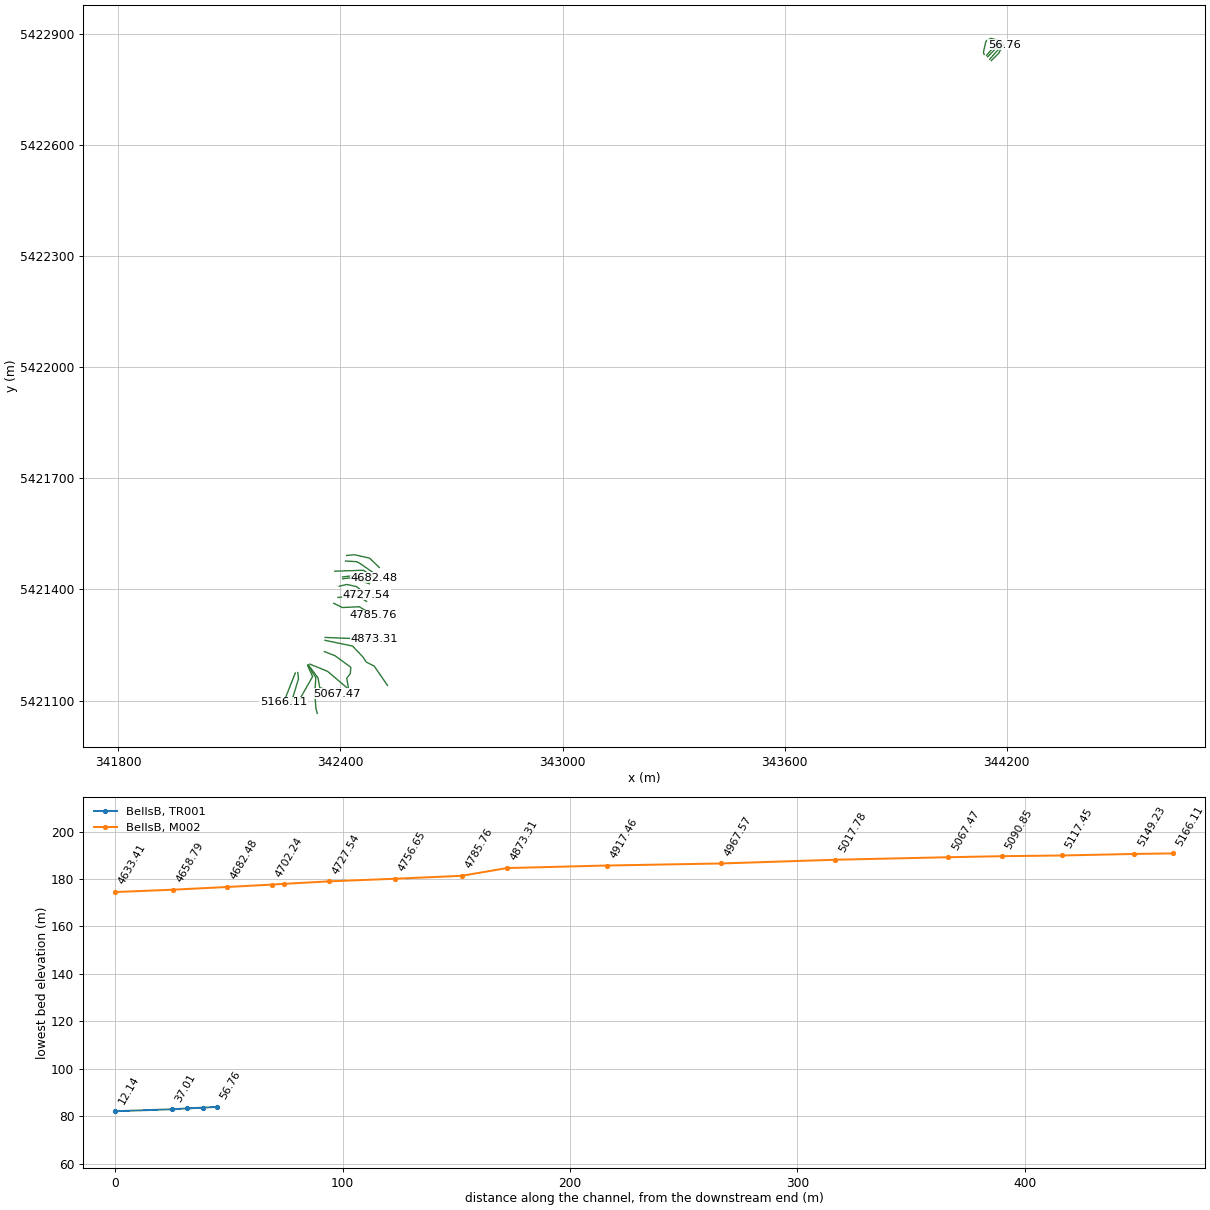
HEC-RAS study Corner_Brook2.prj: Corner_Brook2

--- Corner_Brook2.g03 (geometry) --- (continued)

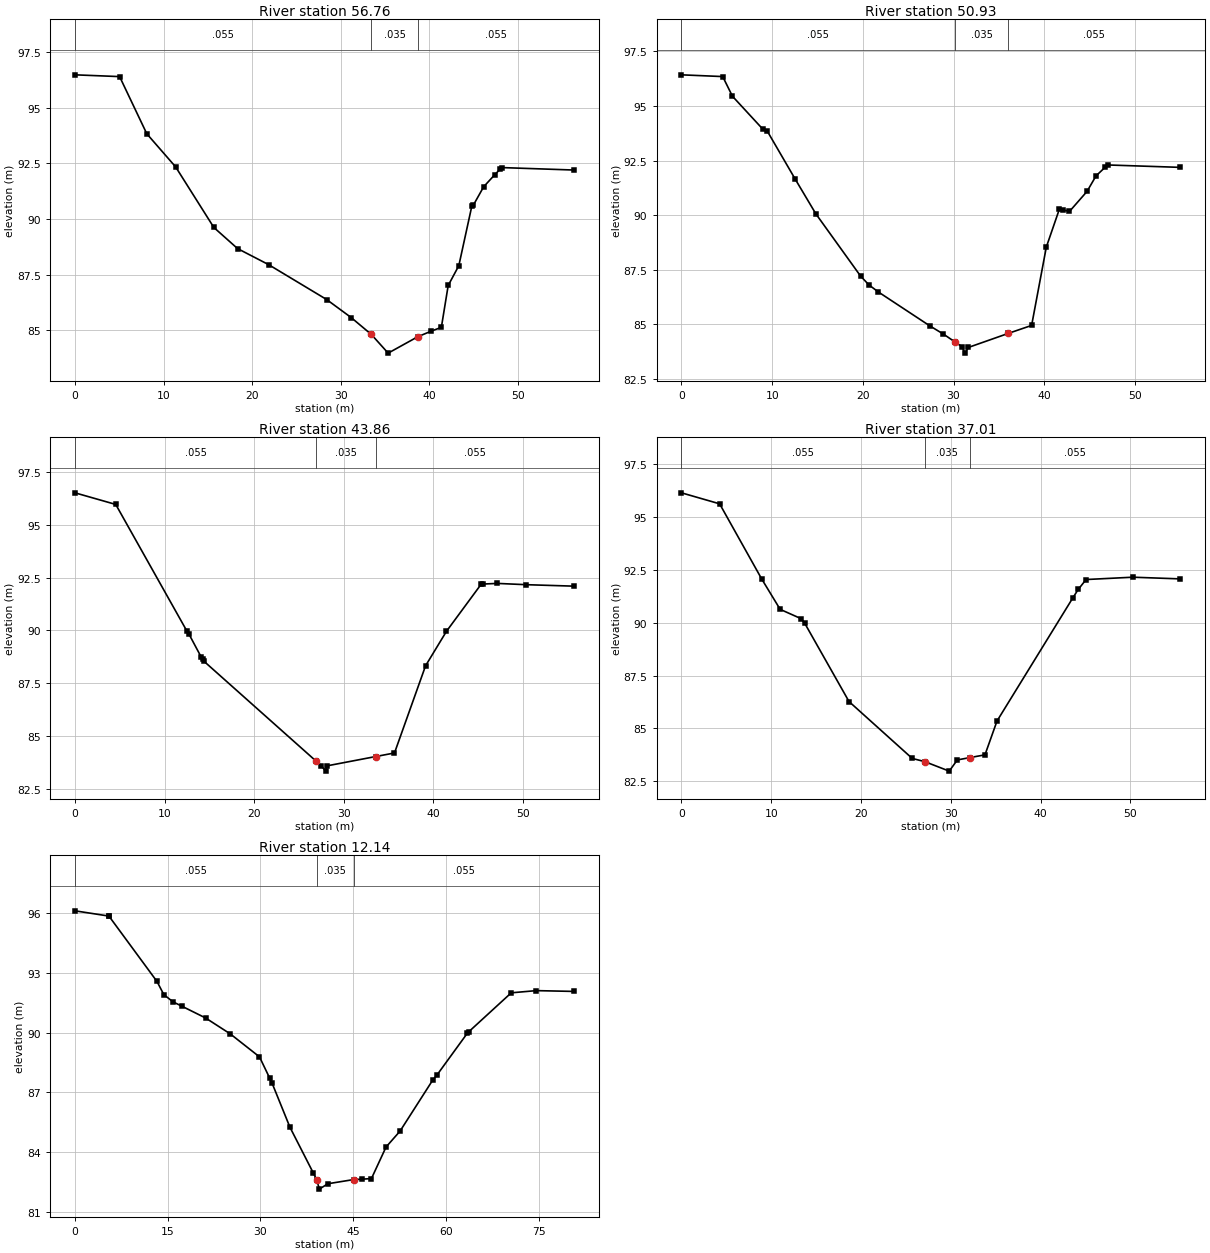
Type RM Length L Ch R = 1 ,56.76   ,7.72,5.83,4.41
XS GIS Cut Line= 4
344158.3076782235422827.16552734 344178.579895025422847.07751465
344186.7235107425422864.21929932344193.4810791025422870.10632324
#Sta/Elev= 23
       0   96.48    5.04    96.4    8.11   93.83   11.37   92.34   15.68   89.62
   18.36   88.67   21.86   87.95   28.42   86.38   31.19   85.57   33.47   84.81
   35.37   83.97   38.73   84.71   40.25   84.96   41.38   85.13   42.15   87.01
   43.35    87.9   44.82   90.58   44.99   90.62   46.16   91.45   47.39   91.98
   47.99   92.23   48.26   92.31   56.36    92.2
#Mann= 3 , 0 , 0
       0    .055       0   33.47    .035       0   38.73    .055       0
Bank Sta=33.47,38.73
XS Rating Curve= 0 ,0
Exp/Cntr=0.3,0.1

Type RM Length L Ch R = 1 ,50.93   ,7.48,7.07,7.18
XS GIS Cut Line= 3
344154.1492919925422830.97467041344182.045288086 5422862.4876709
344192.0949096685422870.62567139
#Sta/Elev= 27
       0   96.43    4.55   96.35    5.62   95.45    8.95   93.95    9.45   93.86
   12.53   91.66   14.82   90.06   19.75   87.21   20.66   86.81   21.68   86.49
   27.38   84.93   28.89   84.55   30.17  84.189   30.91   83.98   31.27   83.68
   31.63   83.94   36.01   84.58   38.61   84.95   40.23   88.54   41.68   90.29
   42.09   90.24   42.78   90.17   44.72   91.09   45.71    91.8    46.7   92.19
   47.04    92.3   55.02   92.19
#Mann= 3 , 0 , 0
       0    .055       0   30.17    .035       0   36.01    .055       0
Bank Sta=30.17,36.01
XS Rating Curve= 0 ,0
Exp/Cntr=0.3,0.1

Type RM Length L Ch R = 1 ,43.86   ,6.35,6.86,7.11
XS GIS Cut Line= 3
344148.4312744145422837.38128662344180.3126831055422869.93310547
344188.4562988285422875.99328613
#Sta/Elev= 20
       0   96.52    4.55   95.97   12.51   89.96   12.71   89.84   14.08   88.75
   14.25   88.65   14.38   88.55   26.94  83.804   27.48    83.6   27.99   83.34
   28.14   83.59   33.56   84.03   35.67    84.2   39.14   88.33   41.47   89.96
   45.36    92.2   45.56    92.2   47.15   92.23   50.35   92.17   55.71    92.1
#Mann= 3 , 0 , 0
       0    .055       0   26.94    .035       0   33.56    .055       0
Bank Sta=26.94,33.56
XS Rating Curve= 0 ,0
Exp/Cntr=0.3,0.1

Type RM Length L Ch R = 1 ,37.01   ,27.23,24.86,22.79
XS GIS Cut Line= 3
344145.4793090825422841.12591553344173.7730712895422874.27587891
 344184.958923345422878.58673096
#Sta/Elev= 19
       0   96.14    4.25   95.62    8.93   92.07   10.99   90.63   13.32   90.19
   13.73   89.97   18.66   86.27    25.7   83.58   27.09   83.43   29.82   82.98
   30.72   83.51   32.12   83.62    33.8   83.75   35.14   85.35   43.58   91.17
   44.18   91.57   45.06   92.04   50.26   92.15   55.57   92.07
#Mann= 3 , 0 , 0
       0    .055       0   27.09    .035       0   32.12    .055       0
Bank Sta=27.09,32.12
XS Rating Curve= 0 ,0
Exp/Cntr=0.3,0.1

Type RM Length L Ch R = 1 ,12.14   ,4.7,12.15,6.96
XS GIS Cut Line= 6
344139.0648803715422843.84472656344136.9857177735422848.86608887
344142.5302734385422874.31890869344145.1292724615422880.89849854
344157.6044921885422887.30487061344184.6342773445422879.51330566
#Sta/Elev= 29
       0    96.1    5.43   95.84    5.48   95.84   13.26   92.56   14.37    91.9
   15.84   91.54   17.28   91.32   21.12   90.73   25.12   89.93   29.84   88.78
   31.48   87.72   31.88   87.46   34.77   85.25   38.56   82.95   39.11  82.606
   39.52   82.15    40.9   82.42   45.09   82.63   46.48   82.65   47.95   82.68
   50.31   84.26   52.58   85.06   57.87   87.62    58.5   87.85   63.47   89.97
   63.73   90.05   70.56   91.99   74.61    92.1   80.71   92.06
#Mann= 3 , 0 , 0
       0    .055       0   39.11    .035       0   45.09    .055       0
Bank Sta=39.11,45.09
XS Rating Curve= 0 ,0
Exp/Cntr=0.3,0.1

River Reach=BellsB          ,M002

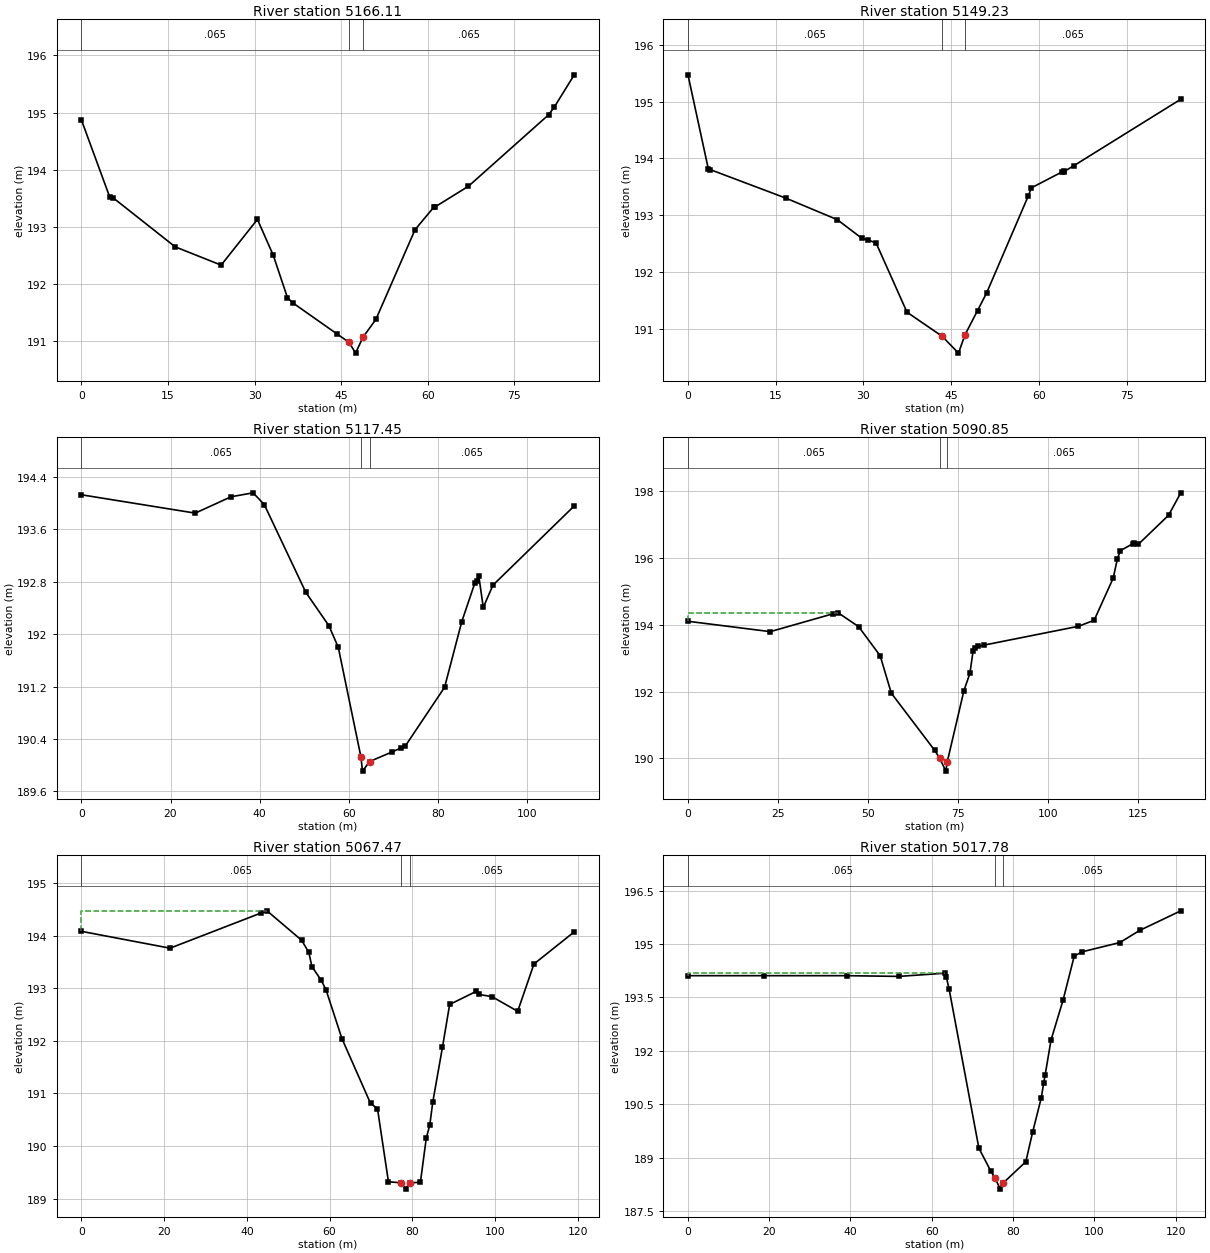
Type RM Length L Ch R = 1 ,5166.11 ,15.85,16.88,18.06
XS GIS Cut Line= 2
342277.9199218755421174.32928467342246.3927001955421094.99212646
#Sta/Elev= 21
       0  194.87    4.87  193.53    5.46  193.51   16.24  192.65    24.2  192.33
   30.49  193.13   33.24   192.5   35.69  191.76   36.61  191.67   44.35  191.12
   46.35  190.98   47.49  190.79   48.76 191.067   51.01  191.38   57.79  192.95
   61.01  193.34   61.28  193.35   67.04  193.71   80.92  194.96   81.94   195.1
   85.37  195.66
#Mann= 3 , 0 , 0
       0    .065       0   46.35     .04       0   48.76    .065       0
Bank Sta=46.35,48.76
XS Rating Curve= 0 ,0
Exp/Cntr=0.3,0.1

Type RM Length L Ch R = 1 ,5149.23 ,31.28,31.78,26.26
XS GIS Cut Line= 3
342284.6198730475421175.58990479342286.6940917975421159.00872803
 342266.990295415421094.41052246
#Sta/Elev= 21
       0  195.47    3.49  193.81    3.84   193.8   16.71   193.3   25.53  192.92
   29.75  192.59   30.83  192.56   32.16  192.51   37.45  191.29   43.45 190.867
   46.25  190.57   47.35  190.89   49.51  191.32   51.06  191.63   58.15  193.33
   58.71  193.48   63.94  193.76   64.25  193.76   64.35  193.77   65.97  193.87
   84.25  195.04
#Mann= 3 , 0 , 0
       0    .065       0   43.45     .04       0   47.35    .065       0
Bank Sta=43.45,47.35
XS Rating Curve= 0 ,0
Exp/Cntr=0.3,0.1

Type RM Length L Ch R = 1 ,5117.45 ,19.84,26.6,30.57
XS GIS Cut Line= 3
342310.9426879885421195.21392822342324.6160888675421164.53149414
342286.500915527  5421097.578125
#Sta/Elev= 22
       0  194.13   25.55  193.85   33.59   194.1   38.54  194.16   41.05  193.98
   50.37  192.64   55.56  192.13   57.66   191.8   62.74 190.128    63.1  189.91
   64.68 190.056   69.63   190.2   71.63  190.26   72.67  190.29   81.52  191.19
   85.37  192.19   88.35  192.79    88.8  192.82    89.2  192.89   90.21  192.41
   92.38  192.75  110.63  193.96
#Mann= 3 , 0 , 0
       0    .065       0   62.74     .04       0   64.68    .065       0
Bank Sta=62.74,64.68
XS Rating Curve= 0 ,0
Exp/Cntr=0.3,0.1

Type RM Length L Ch R = 1 ,5090.85 ,11.72,23.38,30.25
XS GIS Cut Line= 5
342312.2744750985421195.62567139342333.3610839845421161.42669678
342330.595703125 5421119.2824707 342333.706909185421078.17468262
342337.5092773445421065.39331055
#Sta/Elev= 27
       0   194.1   22.87  193.79   40.18  194.32   41.65  194.36   47.43  193.94
   53.42  193.07   56.52  191.95   68.58  190.24   69.99     190   71.67  189.62
   72.07   189.9   76.71  192.03   78.35  192.54   79.25  193.21   79.73  193.31
   80.68  193.35   82.41  193.39  108.53  193.95  112.89  194.13  118.19  195.39
  119.36  195.97  120.17  196.21  123.64  196.42  123.87  196.44  125.17   196.4
  133.58  197.27  136.97  197.94
#Mann= 3 , 0 , 0
       0    .065       0   69.99     .04       0   72.07    .065       0
#XS Ineff= 2 , 0
       0   41.65  194.36               0
Permanent Ineff=
       F       F
Bank Sta=69.99,72.07
XS Rating Curve= 0 ,0
Exp/Cntr=0.3,0.1

Type RM Length L Ch R = 1 ,5067.47 ,48.56,49.69,45.53
XS GIS Cut Line= 4
342313.2647094735421195.98748779342339.321716309 5421161.1796875
342343.9644775395421135.16009521342390.2396850595421118.28967285
#Sta/Elev= 28
       0  194.08   21.43  193.76   43.48  194.43   44.88  194.47   53.25  193.91
   54.99  193.68   55.73  193.41   57.98  193.15   59.14  192.97      63  192.04
   69.91  190.81   71.59  190.71   74.24  189.32   77.36   189.3   78.38  189.18
   79.36   189.3   81.97  189.31   83.39  190.15   84.24   190.4   84.95  190.83
   87.31  191.88   89.04  192.69   95.49  192.94   96.14  192.88   99.25  192.84
  105.49  192.56  109.43  193.46  119.17  194.07
#Mann= 3 , 0 , 0
       0    .065       0   77.36     .04       0   79.36    .065       0
#XS Ineff= 2 , 0
       0   44.88  194.47               0
Permanent Ineff=
       F       F
Bank Sta=77.36,79.36
XS Rating Curve= 0 ,0
Exp/Cntr=0.3,0.1

Type RM Length L Ch R = 1 ,5017.78 ,49.08,50.21,50
XS GIS Cut Line= 3
 342317.392517095421198.30810547342365.3787231455421178.71252441
342418.3422851565421133.77050781
#Sta/Elev= 24
       0  194.11   18.61  194.11   39.21  194.11   51.83  194.09   63.38  194.18
   63.57  194.08   64.28  193.73    71.6  189.27   74.56  188.62   75.65  188.42
   76.84  188.12   77.65   188.3   83.16  188.89   84.81  189.71   86.95  190.68
   87.54  191.09   87.92  191.33   89.35   192.3   92.31  193.42   95.07  194.66
   97.02  194.78   106.3  195.04  111.18  195.38  121.29  195.93
#Mann= 3 , 0 , 0
       0    .065       0   75.65     .04       0   77.65    .065       0
#XS Ineff= 2 , 0
       0   63.38  194.18               0
Permanent Ineff=
       F       F
Bank Sta=75.65,77.65
XS Rating Curve= 0 ,0
Exp/Cntr=0.3,0.1

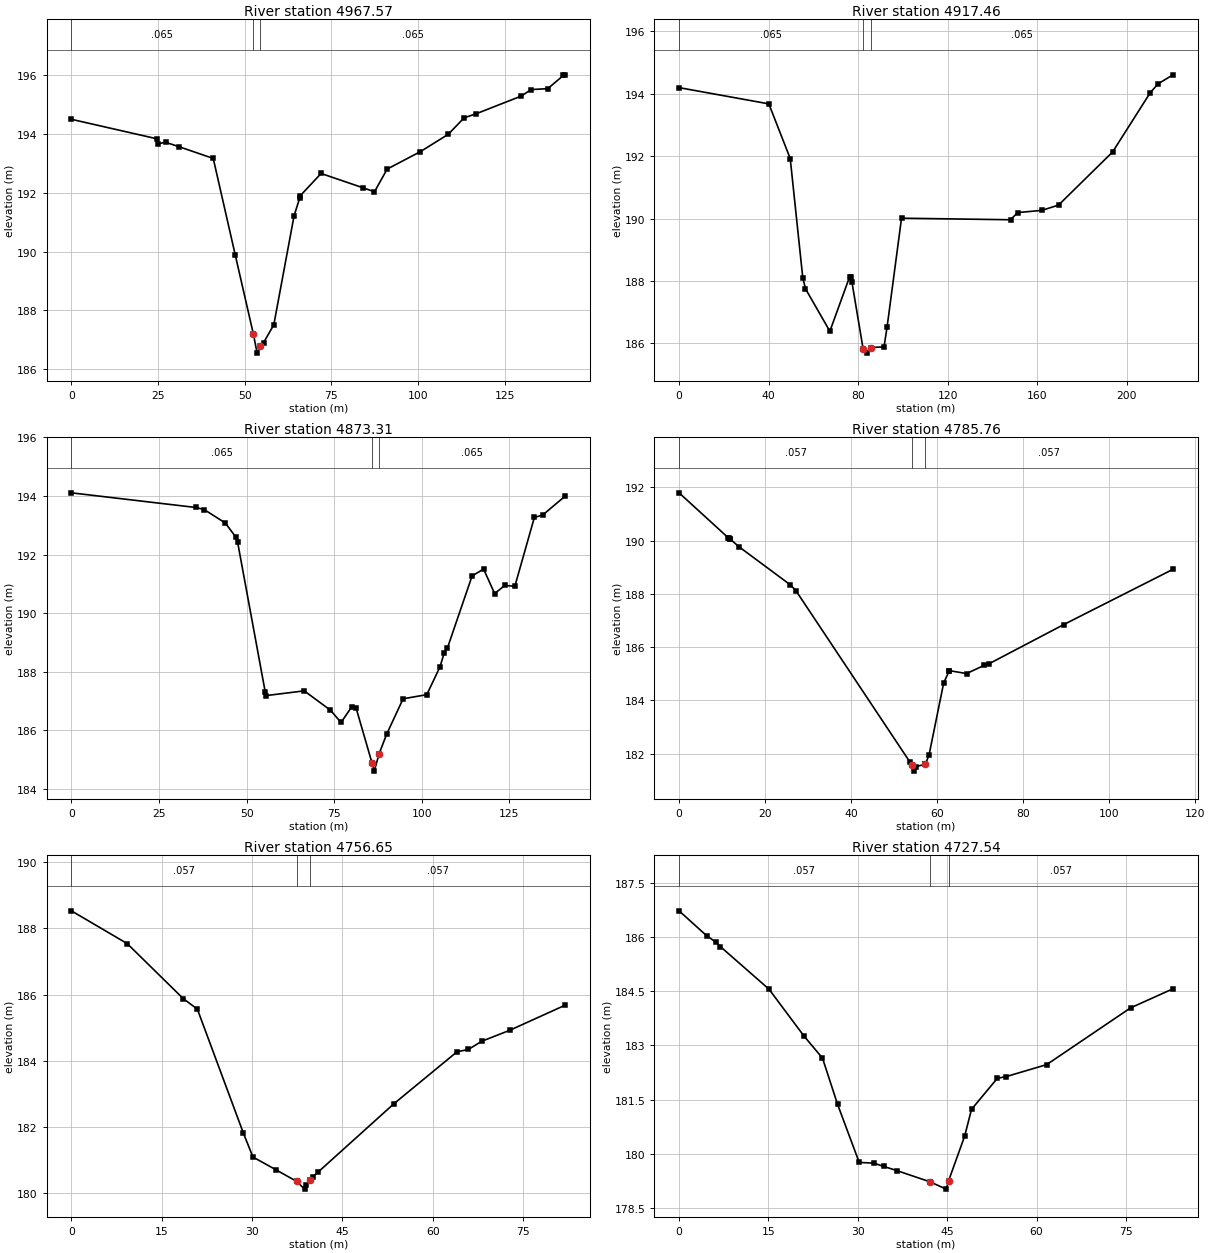
Type RM Length L Ch R = 1 ,4967.57 ,45.92,50.1,48.87
XS GIS Cut Line= 6
342356.3491210945421232.34228516342385.2438964845421220.99768066
342427.9514770515421189.73413086342426.5952758795421173.13287354
 342416.976684575421160.14831543342421.3626708985421134.88031006
#Sta/Elev= 28
       0  194.49   24.59  193.83    25.1  193.66   27.15  193.71   31.04  193.56
   40.92  193.16   47.29  189.87   52.49   187.2   53.57  186.55   54.49  186.78
   55.45  186.91   58.38  187.51   64.24  191.22   65.84  191.81   66.05   191.9
   72.02  192.65   83.97  192.17   87.42  192.03   91.08   192.8  100.63  193.39
  108.69  193.98  113.27  194.54  116.79  194.68  129.77  195.28   132.6   195.5
  137.39  195.53   141.9  195.98  142.43     196
#Mann= 3 , 0 , 0
       0    .065       0   52.49     .04       0   54.49    .065       0
Bank Sta=52.49,54.49
XS Rating Curve= 0 ,0
Exp/Cntr=0.3,0.1

Type RM Length L Ch R = 1 ,4917.46 ,19.17,44.16,54.69
XS GIS Cut Line= 6
342357.8818969735421262.62231445 342432.634704595421247.08508301
342461.317871094 5421216.9163208342469.8649291995421203.72247314
342491.2780761725421192.89349365342526.8798828135421141.00531006
#Sta/Elev= 23
       0  194.19   40.11  193.67   49.66  191.92   55.26  188.11   56.48  187.75
   67.37  186.39   76.23  188.14   76.67  188.12   77.24  187.96   82.26  185.81
   83.82  185.69   85.67  185.87   91.56  185.89   92.94  186.53   99.38  190.01
  148.09  189.96  151.23  190.19  162.06  190.26  169.52  190.43  193.67  192.13
  210.51  194.03  213.95  194.31  220.62   194.6
#Mann= 3 , 0 , 0
       0    .065       0   82.26     .04       0   85.67    .065       0
Bank Sta=82.26,85.67
XS Rating Curve= 0 ,0
Exp/Cntr=0.3,0.1

Type RM Length L Ch R = 1 ,4873.31 ,21.46,19.89,10.45
XS GIS Cut Line= 4
342358.6434936525421270.36907959342438.6124877935421267.15551758
342445.2736816415421278.15710449342491.5441284185421265.21850586
#Sta/Elev= 30
       0  194.11    35.5  193.61   37.89  193.54   43.94  193.08   46.92   192.6
   47.42  192.44   55.33  187.31   55.68  187.19   66.45  187.35   73.94  186.69
   76.96  186.27   80.03  186.81   81.22  186.78   85.82  184.88   86.44  184.61
   87.82   185.2   89.97  185.87   94.68  187.08  101.43  187.22   105.2  188.17
  106.36  188.63  107.34  188.82  114.35  191.27  117.64  191.51  120.79  190.67
   123.7  190.95  126.56  190.92  132.13  193.27  134.49  193.35  140.94     194
#Mann= 3 , 0 , 0
       0    .065       0   85.82     .04       0   87.82    .065       0
Bank Sta=85.82,87.82
XS Rating Curve= 0 ,0
Exp/Cntr=0.3,0.1

Type RM Length L Ch R = 1 ,4785.76 ,29.07,29.11,29.57
XS GIS Cut Line= 4
342381.8477172855421362.48071289342405.0465087895421351.04650879
 342451.236511235421353.20410156342487.4505004885421330.52331543
#Sta/Elev= 23
       0  191.79   11.47   190.1   11.65  190.08   11.78  190.07   11.92  190.05
   13.91  189.77   25.86  188.34   27.17  188.12    53.6  181.71    54.2 181.581
   54.58  181.35    55.1  181.52    57.1   181.6   57.25   181.6   58.13  181.96
   61.53  184.66   62.79   185.1   62.85  185.12   66.84  185.01   70.98  185.32
    72.1  185.38   89.47  186.85  114.83  188.92
#Mann= 3 , 0 , 0
       0    .057       0    54.2     .04       0    57.1    .057       0
Bank Sta=54.2,57.1
XS Rating Curve= 0 ,0
Exp/Cntr=0.3,0.1

Type RM Length L Ch R = 1 ,4756.65 ,30.95,29.11,26.42
XS GIS Cut Line= 3
342393.0432739265421378.32452393342446.4367065435421382.54150391
342470.5885009775421367.50811768
#Sta/Elev= 19
       0  188.53    9.27  187.54   18.62  185.87   20.92  185.56   28.55  181.82
   30.15  181.09   33.92  180.71   37.43 180.352   38.72  180.12      39  180.25
   39.68   180.4   40.13   180.5      41  180.64   53.56   182.7   64.04  184.27
   65.91  184.34   68.17  184.59    72.8  184.92   82.01  185.68
#Mann= 3 , 0 , 0
       0    .057       0   37.43     .04       0   39.68    .057       0
Bank Sta=37.43,39.68
XS Rating Curve= 0 ,0
Exp/Cntr=0.3,0.1

Type RM Length L Ch R = 1 ,4727.54 ,19.26,20,19.72
XS GIS Cut Line= 4
342396.6063232425421408.54730225342417.0162963875421413.36407471
342443.3679199225421407.66790771342470.1505126955421385.22271729
#Sta/Elev= 22
       0  186.73    4.63  186.04    6.12  185.87    6.93  185.74   15.09  184.56
   20.97  183.26   24.07  182.65    26.6  181.37   30.23  179.76   32.67  179.74
   34.33  179.65   36.61  179.53   42.07 179.225   44.84  179.02   45.24 179.254
   47.93  180.49   49.08  181.23   53.41  182.09   54.95  182.14    61.7  182.47
   75.76  184.04   82.88  184.57
#Mann= 3 , 0 , 0
       0    .057       0   42.07    .037       0   45.24    .057       0
Bank Sta=42.07,45.24
XS Rating Curve= 0 ,0
Exp/Cntr=0.3,0.1

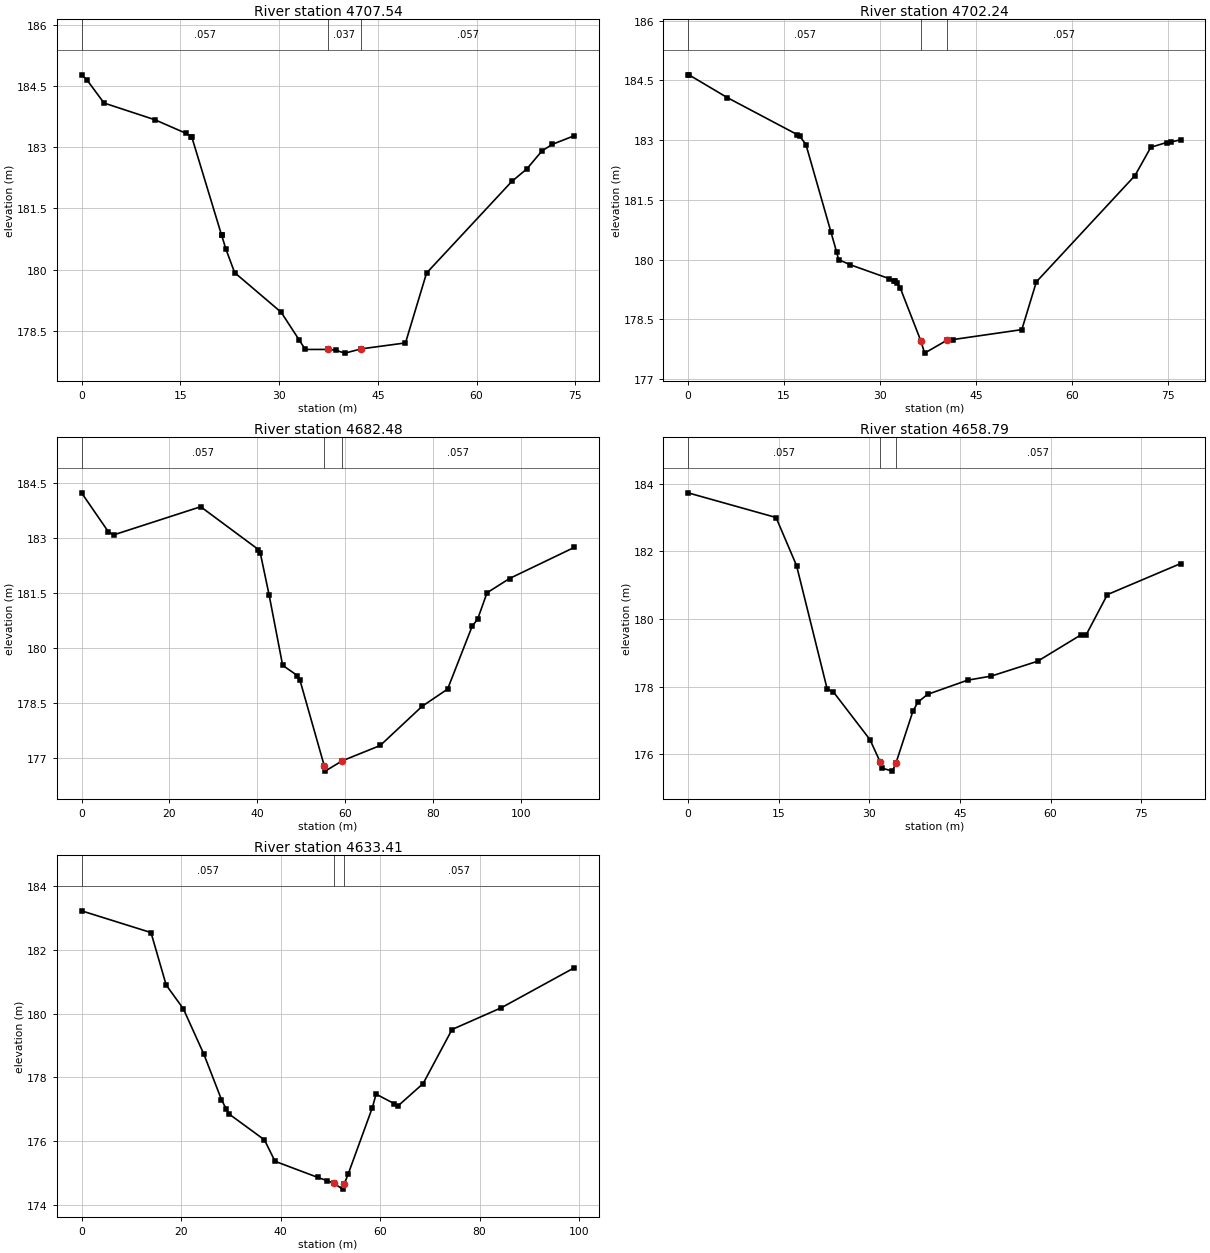
Type RM Length L Ch R = 1 ,4707.54 ,5.01,5.31,4.99
XS GIS Cut Line= 3
342405.9539184575421428.78527832342427.0795288095421431.20550537
342478.2404785165421415.30487061
#Sta/Elev= 25
       0  184.77      .8  184.65    3.41  184.08   11.15  183.67   15.84  183.34
   16.68  183.26   16.74  183.25   21.26  180.85   21.27  180.85   21.89  180.52
   23.25  179.93   30.32  178.96   33.06  178.28   33.98  178.05   37.37  178.05
    38.6  178.03      40  177.96   42.46 178.064    49.2  178.21    52.4  179.92
   65.34  182.16   67.64  182.47   69.94  182.91   71.52  183.07   74.84  183.28
#Mann= 3 , 0 , 0
       0    .057       0   37.37    .037       0   42.46    .057       0
Bank Sta=37.37,42.46
XS Rating Curve= 0 ,0
Exp/Cntr=0.3,0.1

Type RM Length L Ch R = 1 ,4702.24 ,16.74,19.76,23.42
XS GIS Cut Line= 3
342405.385681152 5421433.7454834342427.5565185555421436.28552246
342479.7224731455421420.07269287
#Sta/Elev= 26
       0  184.64     .14  184.64    6.11  184.07   17.04  183.14   17.44   183.1
   18.41  182.89   22.32  180.69    23.2  180.19   23.51     180   25.32  179.87
   31.43  179.52   32.12  179.47   32.25  179.47   32.66  179.41   33.13  179.29
   36.37  177.95   36.94  177.65   40.39  177.97   41.34  177.99   52.12  178.24
   54.39  179.44   69.79  182.11   72.26  182.82   74.72  182.94   75.35  182.95
   76.94  183.01
#Mann= 3 , 0 , 0
       0    .057       0   36.37    .037       0   40.39    .057       0
Bank Sta=36.37,40.39
XS Rating Curve= 0 ,0
Exp/Cntr=0.3,0.1

Type RM Length L Ch R = 1 ,4682.48 ,24.78,23.69,17.54
XS GIS Cut Line= 3
342384.6652832035421449.13708496342462.1015014655421451.67608643
342490.3955078135421431.71368408
#Sta/Elev= 21
       0  184.23    6.08  183.17    7.27  183.08    27.1  183.85   40.25  182.68
   40.66  182.59   42.69  181.43   45.75  179.52   49.09  179.24   49.65  179.13
   55.24 176.766   55.42  176.63   59.29  176.91   67.95  177.33   77.48   178.4
   83.28  178.87   88.85  180.58   90.14  180.79   92.25   181.5   97.37  181.89
  112.11  182.74
#Mann= 3 , 0 , 0
       0    .057       0   55.24    .037       0   59.29    .057       0
Bank Sta=55.24,59.29
XS Rating Curve= 0 ,0
Exp/Cntr=0.3,0.1

Type RM Length L Ch R = 1 ,4658.79 ,20.47,25.37,24.27
XS GIS Cut Line= 4
342413.6375122075421476.55328369342443.7119140635421474.82592773
 342454.427917485421468.95349121342486.5764770515421446.49951172
#Sta/Elev= 20
       0  183.73   14.57     183   17.96  181.58   23.03  177.93   24.07  177.84
   30.12  176.43   31.78  175.78   32.09  175.59   33.83   175.5    34.4  175.73
   37.22  177.27   38.05  177.54   39.65  177.77   46.28  178.19   50.19  178.31
   57.87  178.75   65.04  179.53    65.9  179.53   69.41  180.72   81.56  181.64
#Mann= 3 , 0 , 0
       0    .057       0   31.78    .037       0    34.4    .057       0
Bank Sta=31.78,34.4
XS Rating Curve= 0 ,0
Exp/Cntr=0.3,0.1

Type RM Length L Ch R = 1 ,4633.41 ,27.81,23.8,18.32
XS GIS Cut Line= 4
342416.7960815435421491.53570557342437.1434936525421493.58789063
342478.5769042975421484.43591309342504.669311523 5421459.3939209
#Sta/Elev= 24
       0  183.21   13.96  182.53   17.01  180.89   20.45  180.15   24.58  178.73
   28.12  177.31   29.03  177.03   29.55  176.87   36.76  176.05   38.89  175.38
   47.43  174.88   49.43  174.77   50.68 174.697   52.47  174.51   52.79  174.66
   53.59  174.98   58.46  177.06    59.2  177.48   62.88  177.18   63.67  177.12
   68.66  177.81   74.47   179.5   84.38  180.18   99.05  181.43
#Mann= 3 , 0 , 0
       0    .057       0   50.68    .037       0   52.79    .057       0
Bank Sta=50.68,52.79
XS Rating Curve= 0 ,0
Exp/Cntr=0.3,0.1