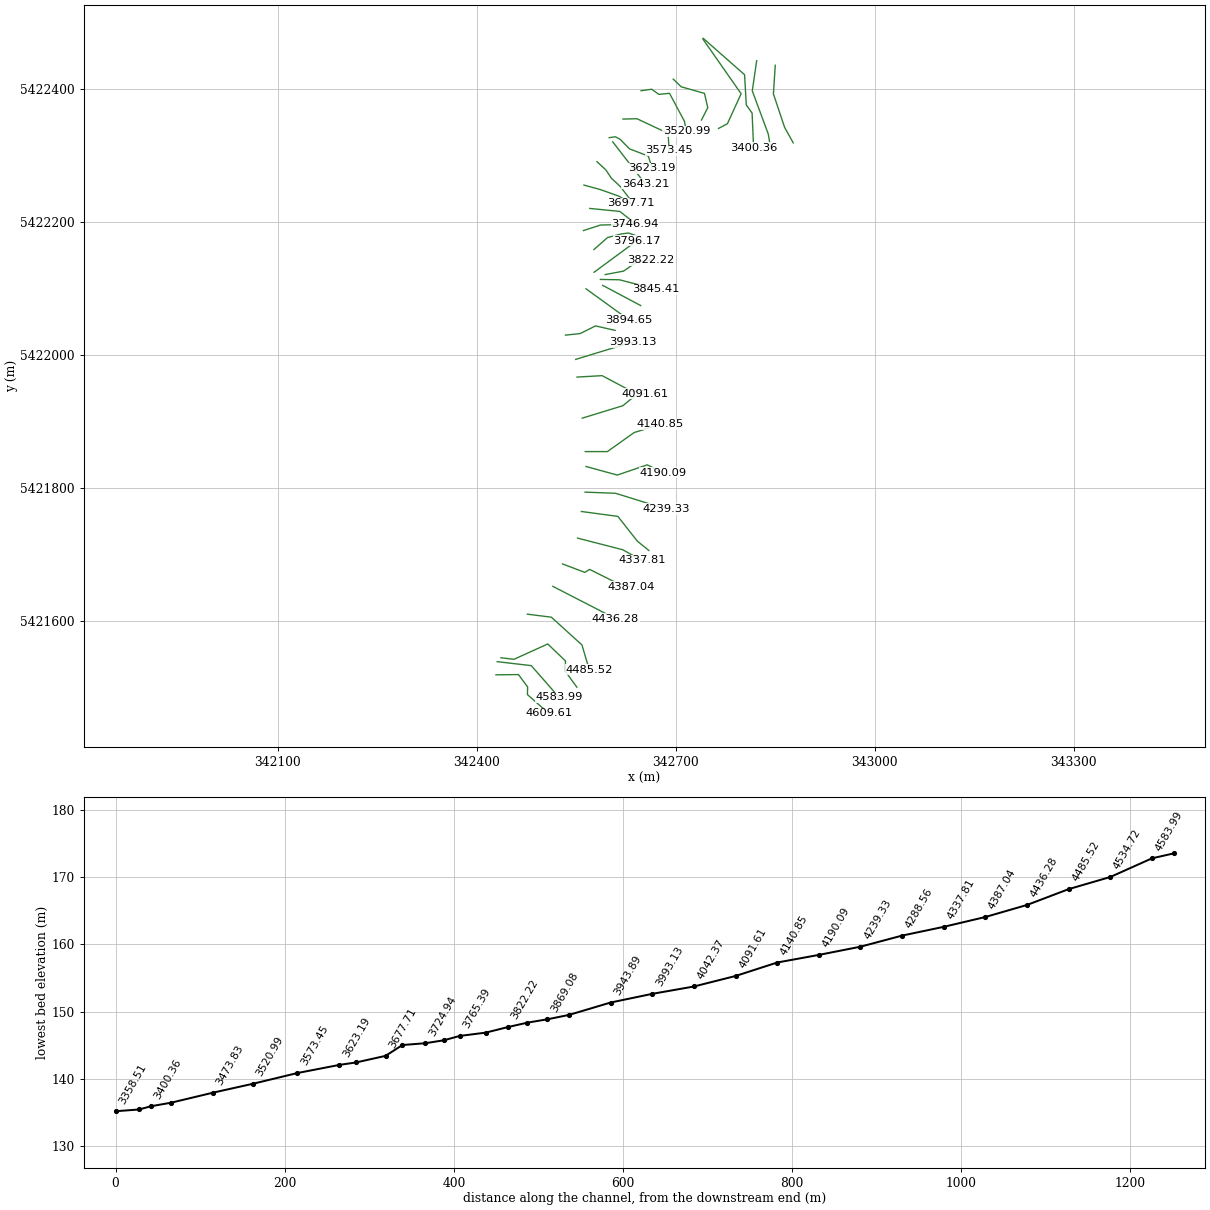
HEC-RAS study Corner_Brook2.prj: Corner_Brook2

--- Corner_Brook2.g03 (geometry) --- (continued)

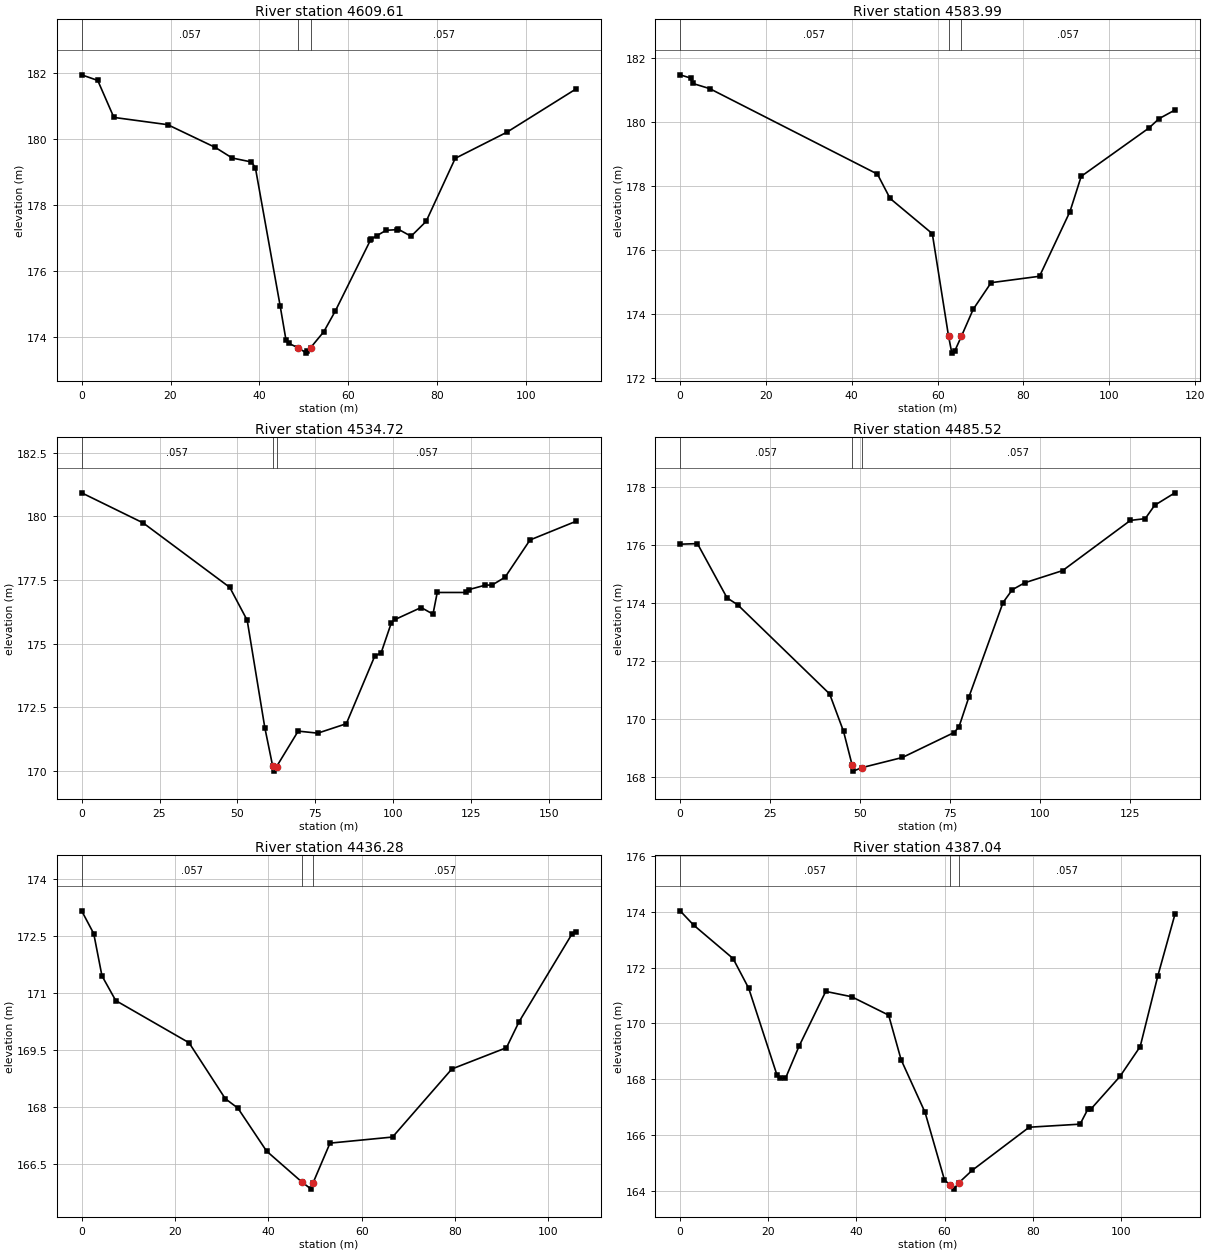
Type RM Length L Ch R = 1 ,4609.61 ,24.92,25.62,25.97
XS GIS Cut Line= 5
342429.1931152345421518.69750977342463.0698852545421519.04290771
342476.8972778325421500.38891602342476.5516967775421488.98931885
342508.7000732425421460.66271973
#Sta/Elev= 28
       0  181.93    3.62  181.76    7.25  180.64   19.36  180.42   30.09  179.73
   33.88  179.41   38.21  179.29   39.09  179.12   44.66  174.94   45.98   173.9
   46.55   173.8   48.75  173.66   50.58   173.5   50.82  173.55   51.53 173.666
    54.5  174.15    57.1  174.78   64.98  176.92   65.12  176.95   66.47  177.06
    68.5  177.22   70.92  177.24    71.3  177.25   74.13  177.04   77.52  177.49
   84.07   179.4   95.67  180.19  111.35  181.51
#Mann= 3 , 0 , 0
       0    .057       0   48.75    .037       0   51.53    .057       0
Bank Sta=48.75,51.53
XS Rating Curve= 0 ,0
Exp/Cntr=0.3,0.1

Type RM Length L Ch R = 1 ,4583.99 ,44.18,49.27,61.24
XS GIS Cut Line= 3
342431.0048828135421538.47949219342482.4049072275421532.46948242
342524.3275146485421484.73327637
#Sta/Elev= 19
       0  181.46    2.43  181.36    2.96  181.19    6.88  181.03   45.97  178.36
   48.92   177.6   58.76   176.5   62.54   173.3   63.31  172.77      64  172.84
   65.52  173.29   68.29  174.14   72.46  174.97   83.74  175.17   90.83  177.19
   93.45  178.29  109.24   179.8  111.57  180.09  115.28  180.36
#Mann= 3 , 0 , 0
       0    .057       0   62.54    .037       0   65.52    .057       0
Bank Sta=62.54,65.52
XS Rating Curve= 0 ,0
Exp/Cntr=0.3,0.1

Type RM Length L Ch R = 1 ,4534.72 ,52.34,49.2,34.25
XS GIS Cut Line= 6
342436.604125977 5421544.3560791  342456.17968755421542.00231934
342507.2526855475421565.09869385342533.8956909185421539.60070801
342533.8956909185421523.66491699342551.0834960945421500.07147217
#Sta/Elev= 25
       0  180.92   19.72  179.74   47.53  177.21   53.12  175.92   58.77  171.71
   61.31  170.19   61.87     170   62.56  170.18   69.48  171.57   75.77  171.49
   84.93  171.86   94.04  174.51    96.1  174.64   99.35  175.81  100.58  175.95
  108.94  176.42  112.74  176.16  114.11  177.01  123.21  177.01  124.19  177.12
  129.59   177.3   131.7   177.3  135.88  177.61  143.88  179.07  158.78  179.81
#Mann= 3 , 0 , 0
       0    .057       0   61.31    .037       0   62.56    .057       0
Bank Sta=61.31,62.56
XS Rating Curve= 0 ,0
Exp/Cntr=0.3,0.1

Type RM Length L Ch R = 1 ,4485.52 ,46.5,49.24,52.08
XS GIS Cut Line= 4
342476.4520874025421609.90167236342512.644287109 5421605.4152832
342558.8079223635421563.58587646 342569.720886235421526.56231689
#Sta/Elev= 21
       0  176.02    4.81  176.04   13.03  174.17      16  173.93   41.51  170.86
   45.37  169.57   47.78 168.396   48.08   168.2   50.46  168.32    61.7  168.67
   76.06  169.53   77.43  169.73   80.16  170.75   89.65  174.01   92.21  174.45
   95.66  174.69  106.19  175.11  125.01  176.84  129.12   176.9  131.74  177.36
  137.36  177.79
#Mann= 3 , 0 , 0
       0    .057       0   47.78    .037       0   50.46    .057       0
Bank Sta=47.78,50.46
XS Rating Curve= 0 ,0
Exp/Cntr=0.3,0.1

Type RM Length L Ch R = 1 ,4436.28 ,49.6,49.24,49.91
XS GIS Cut Line= 2
342514.9763183595421651.73468018342609.2982788095421603.30792236
#Sta/Elev= 18
       0  173.17    2.59  172.57    4.35  171.46     7.3  170.81   23.01   169.7
   30.77  168.23   33.48  167.98   39.63  166.85   47.26  166.03   49.18  165.85
   49.54 166.001   53.22  167.06   66.62  167.22   79.33  169.01   91.03  169.57
   93.72  170.25  105.12  172.57  106.03  172.61
#Mann= 3 , 0 , 0
       0    .057       0   47.26    .037       0   49.54    .057       0
Bank Sta=47.26,49.54
XS Rating Curve= 0 ,0
Exp/Cntr=0.3,0.1

Type RM Length L Ch R = 1 ,4387.04 ,46.3,49.24,50.07
XS GIS Cut Line= 5
342529.6284790045421685.46728516342563.0474853525421672.84527588
342570.367919922 5421677.3192749342608.3071289065421658.34008789
342632.8118896485421651.14147949
#Sta/Elev= 26
       0  174.04    3.06  173.53   12.01  172.33   15.57  171.26      22  168.14
   22.75  168.03    23.9  168.03   26.97  169.18   33.04  171.15    38.9  170.96
   47.31   170.3   50.14   168.7   55.58  166.81   59.96   164.4   61.19  164.21
   62.09  164.06   63.19  164.28   66.23  164.73    79.2  166.28   90.75  166.39
   92.49  166.92    93.2  166.93   99.79   168.1  104.38  169.17  108.41  171.72
  112.26  173.91
#Mann= 3 , 0 , 0
       0    .057       0   61.19    .037       0   63.19    .057       0
Bank Sta=61.19,63.19
XS Rating Curve= 0 ,0
Exp/Cntr=0.3,0.1

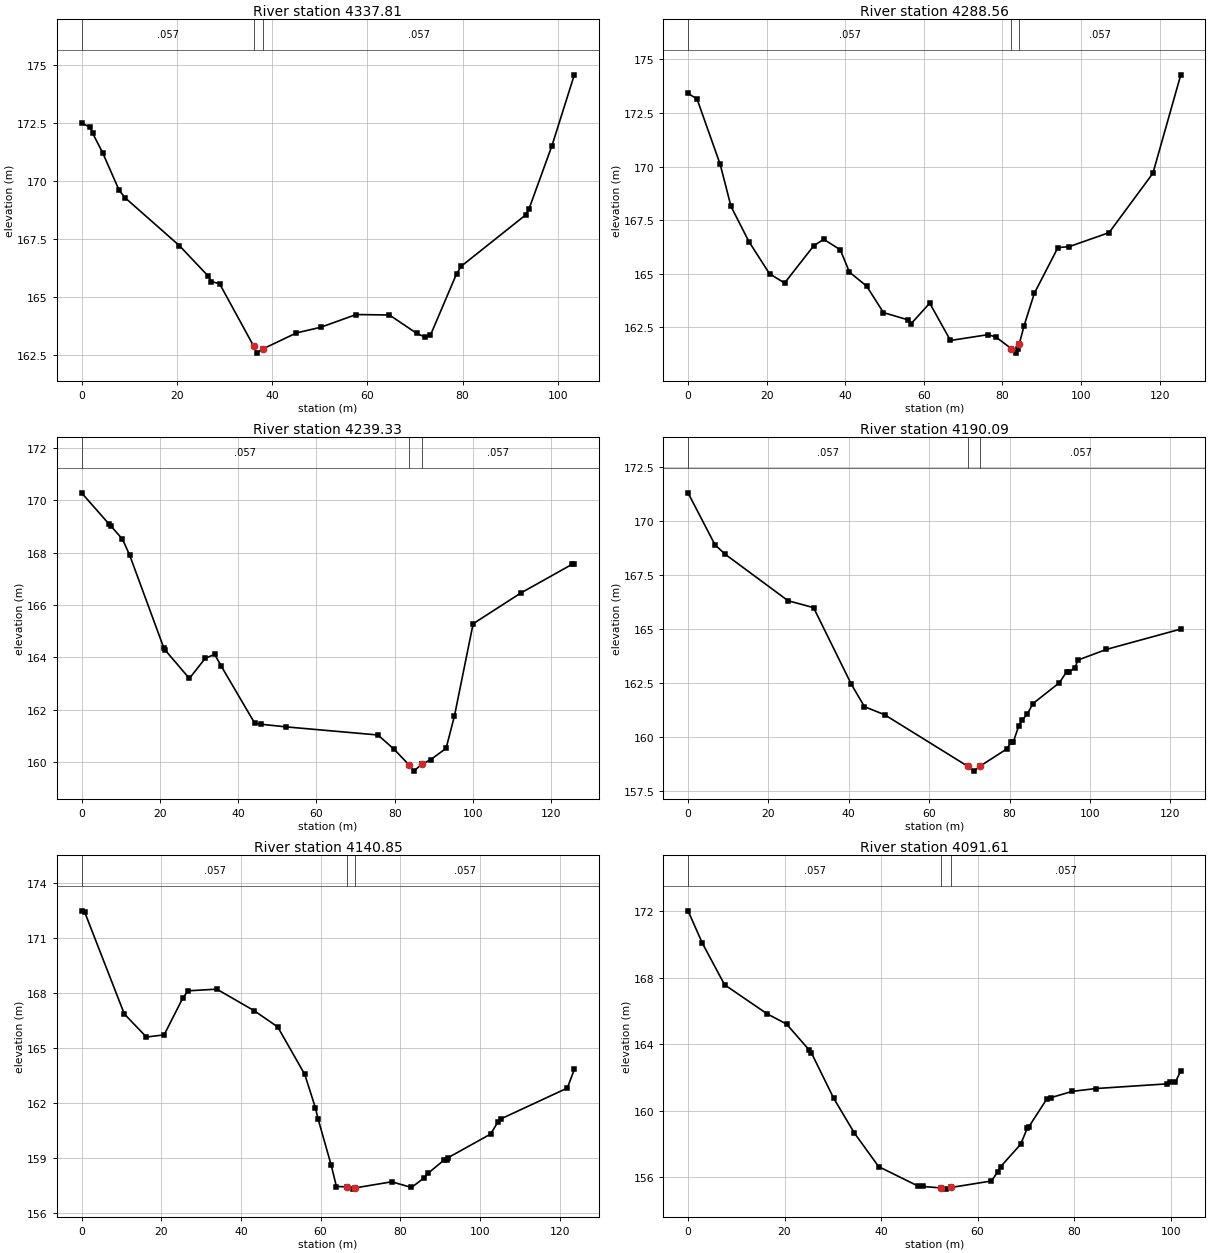
Type RM Length L Ch R = 1 ,4337.81 ,50.62,49.24,33.92
XS GIS Cut Line= 3
342552.150695801 5421724.3861084342620.3140869145421706.85028076
342649.2227172855421690.75970459
#Sta/Elev= 26
       0  172.48    1.81  172.33     2.3  172.07    4.45  171.21     7.9   169.6
    9.21  169.27   20.56  167.22   26.56  165.92   27.28  165.68      29  165.58
   36.17  162.89   36.78   162.6   38.17  162.79   45.13  163.47   50.19  163.71
   57.67  164.26   64.65  164.24   70.38  163.45   72.09  163.29   73.24  163.36
   78.76  166.02   79.74  166.34   93.36  168.56   93.97  168.81   98.79  171.53
  103.47  174.57
#Mann= 3 , 0 , 0
       0    .057       0   36.17    .037       0   38.17    .057       0
Bank Sta=36.17,38.17
XS Rating Curve= 0 ,0
Exp/Cntr=0.3,0.1

Type RM Length L Ch R = 1 ,4288.56 ,36.74,49.24,50.5
XS GIS Cut Line= 4
342557.9196777345421764.43530273342612.8831176765421757.08770752
342642.3812866215421719.70507813342659.7506713875421705.71130371
#Sta/Elev= 30
       0  173.41    2.28  173.16    8.19   170.1   10.94  168.14    15.5   166.5
   20.75     165   24.57  164.57   31.96   166.3   34.52  166.61   38.74  166.12
   41.07  165.08   45.47  164.42   49.73  163.19   56.02  162.85   56.71  162.66
    61.5  163.63   66.78  161.89   76.29  162.16   78.27  162.06   82.26  161.51
   83.35   161.3   83.93  161.48   84.26  161.71   85.48  162.56   88.12  164.09
   94.11  166.22   97.04  166.27  107.14  166.92  118.29  169.69  125.38  174.28
#Mann= 3 , 0 , 0
       0    .057       0   82.26    .037       0   84.26    .057       0
Bank Sta=82.26,84.26
XS Rating Curve= 0 ,0
Exp/Cntr=0.3,0.1

Type RM Length L Ch R = 1 ,4239.33 ,35.63,49.24,52.62
XS GIS Cut Line= 3
 342563.541076665421793.56671143342609.3999023445421791.84429932
342685.8198852545421768.18011475
#Sta/Elev= 27
       0  170.28    7.06  169.08    7.45  169.02   10.46  168.51   12.29   167.9
      21  164.36   21.37  164.27   27.55  163.19    31.6  163.96      34  164.11
   35.73  163.65   44.24  161.48   45.89  161.44   52.26  161.34   75.74  161.03
   79.88  160.48   83.64 159.892   84.87  159.65   86.89  159.91   86.94  159.91
    89.2  160.09   93.13  160.52   95.27  161.76  100.04  165.28  112.19  166.45
  125.33  167.55  125.89  167.58
#Mann= 3 , 0 , 0
       0    .057       0   83.64    .037       0   86.89    .057       0
Bank Sta=83.64,86.89
XS Rating Curve= 0 ,0
Exp/Cntr=0.3,0.1

Type RM Length L Ch R = 1 ,4190.09 ,49.91,49.24,55.65
XS GIS Cut Line= 4
342564.906494141 5421832.1138916342612.0805053715421819.24353027
342657.2094726565421834.66107178342680.4273071295421822.94030762
#Sta/Elev= 25
       0   171.3     6.7   168.9    9.17  168.47   24.89  166.31   31.24  165.99
   40.65  162.44    43.9  161.41    48.9  161.04   69.55  158.66   71.11  158.43
   72.75  158.67   79.42  159.47   80.37   159.8   80.91  159.76   82.23   160.5
   83.06  160.78   84.46  161.08    85.8  161.55   92.41  162.52   94.21  163.03
   94.72  163.02   96.35  163.22   96.94  163.56  104.11  164.06   122.6     165
#Mann= 3 , 0 , 0
       0    .057       0   69.55    .037       0   72.75    .057       0
Bank Sta=69.55,72.75
XS Rating Curve= 0 ,0
Exp/Cntr=0.3,0.1

Type RM Length L Ch R = 1 ,4140.85 ,50.08,49.24,44.09
XS GIS Cut Line= 4
342563.7938842775421854.57348633342597.0925292975421854.53430176
342637.4605102545421883.19732666342676.4578857425421895.42871094
#Sta/Elev= 30
       0  172.47     .75  172.42   10.73  166.85   16.28  165.59   20.73  165.71
   25.47  167.74   26.77  168.11   33.95   168.2   43.37  167.02   49.24  166.14
   56.03  163.55   58.71  161.72   59.35  161.14   62.68  158.59   63.97  157.44
   66.75  157.43   68.11   157.3   68.75  157.37   77.87   157.7   82.81  157.39
   85.91   157.9   87.02  158.17   90.89  158.87   91.77  158.89   92.05  159.02
  102.66   160.3  104.51  160.96  105.37  161.14  121.93  162.81  123.68  163.83
#Mann= 3 , 0 , 0
       0    .057       0   66.75    .037       0   68.75    .057       0
Bank Sta=66.75,68.75
XS Rating Curve= 0 ,0
Exp/Cntr=0.3,0.1

Type RM Length L Ch R = 1 ,4091.61 ,53.58,49.24,44.06
XS GIS Cut Line= 4
342559.2192993165421904.87329102342620.5538940435421923.62390137
342636.3096923835421936.57489014342653.1049194345421941.70928955
#Sta/Elev= 29
       0  172.01    2.98  170.06    7.58  167.57   16.36  165.83   20.41  165.21
   25.02  163.68   25.53   163.5   30.19  160.75   34.46  158.67    39.5  156.65
   47.62  155.49   48.62  155.46    52.5  155.37   53.43   155.3    54.5   155.4
   62.87  155.79   64.14  156.33   64.74  156.64   68.91  157.99   70.32  158.98
    70.6  159.04   74.29  160.69   75.26   160.8   79.61  161.17   84.53  161.34
    99.2  161.62    99.8  161.73  100.99  161.73  102.09  162.41
#Mann= 3 , 0 , 0
       0    .057       0    52.5    .037       0    54.5    .057       0
Bank Sta=52.5,54.5
XS Rating Curve= 0 ,0
Exp/Cntr=0.3,0.1

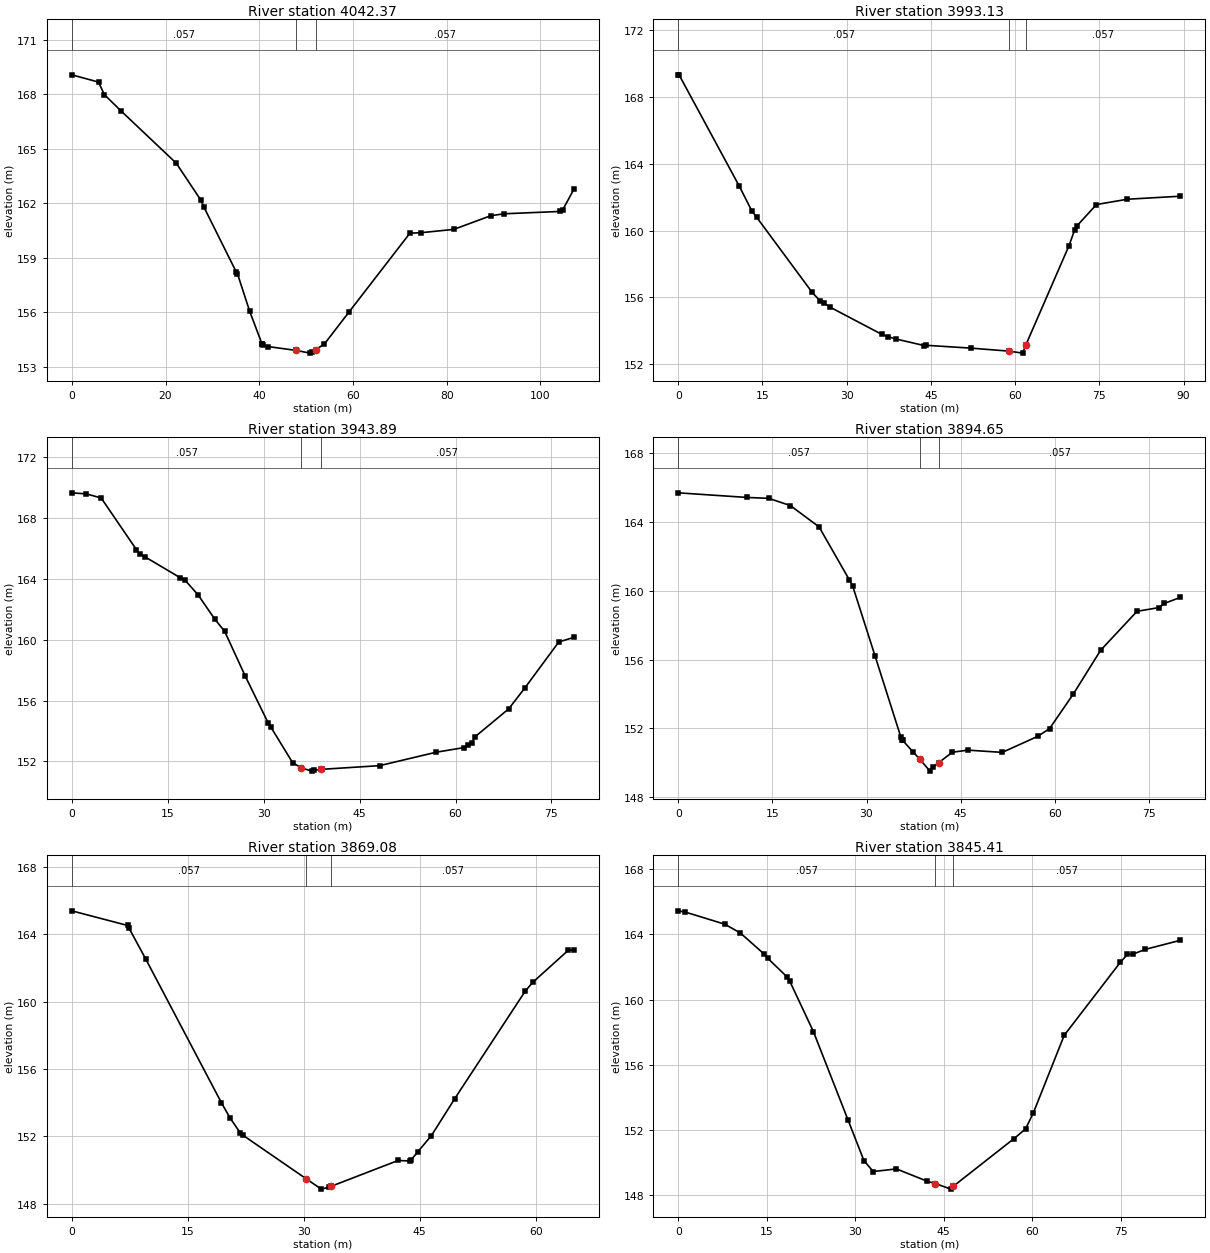
Type RM Length L Ch R = 1 ,4042.37 ,41.02,49.24,52.89
XS GIS Cut Line= 4
342551.3035278325421966.67669678342589.190124512 5421968.8046875
342634.6436767585421944.78930664342652.2474975595421947.19470215
#Sta/Elev= 28
       0  169.08    5.71  168.68    6.95  167.99   10.47   167.1   22.29  164.21
   27.55  162.17   28.19  161.79   35.12   158.2   35.35  158.12   37.95  156.05
   40.57  154.26   40.58  154.25   40.87  154.21   41.92   154.1   47.85  153.89
   50.85  153.74   51.24   153.8   52.05 153.935   53.89  154.24   59.22  156.03
   72.14  160.35   74.58  160.38    81.5  160.56   89.35  161.31    92.2  161.42
  104.19  161.55  104.71  161.62  107.12  162.77
#Mann= 3 , 0 , 0
       0    .057       0   47.85    .037       0   52.05    .057       0
Bank Sta=47.85,52.05
XS Rating Curve= 0 ,0
Exp/Cntr=0.3,0.1

Type RM Length L Ch R = 1 ,3993.13 ,39.57,49.24,44.53
XS GIS Cut Line= 2
342549.3613281255421993.30548096342634.8760986335422019.35968018
#Sta/Elev= 24
       0  169.34     .21   169.3   10.86  162.67    13.1  161.18   13.96   160.8
   23.83   156.3   25.24  155.79   25.98  155.64   26.97  155.42   36.27  153.77
   37.41  153.63   38.86  153.49   43.84   153.1   44.13  153.12    52.1  152.95
   58.87  152.77   61.33  152.65   61.87  153.12   69.59   159.1   70.57  160.03
   71.05   160.3   74.46  161.56   79.99  161.88    89.4  162.06
#Mann= 3 , 0 , 0
       0    .057       0   58.87    .037       0   61.87    .057       0
Bank Sta=58.87,61.87
XS Rating Curve= 0 ,0
Exp/Cntr=0.3,0.1

Type RM Length L Ch R = 1 ,3943.89 ,52.3,49.24,36.01
XS GIS Cut Line= 4
342533.9439086915422029.79992676342556.2128906255422032.16729736
342579.2341308595422043.68389893342608.8457031255422036.94390869
#Sta/Elev= 30
       0  169.65    2.28  169.58     4.6  169.31   10.12  165.91   10.59  165.62
    11.5  165.43   16.96  164.07   17.68  163.92   19.72  162.96   22.39  161.33
    23.9  160.55   27.13   157.6   30.74   154.5   31.09  154.28   34.52  151.92
    35.9  151.57   37.55  151.36   37.94  151.42    38.9  151.47   39.11  151.48
   48.14  151.72   56.94   152.6   61.37  152.91   62.01  153.07   62.57  153.22
   63.03  153.61   68.31  155.45   70.83  156.82   76.15  159.85    78.5  160.15
#Mann= 3 , 0 , 0
       0    .057       0    35.9    .037       0    38.9    .057       0
Bank Sta=35.9,38.9
XS Rating Curve= 0 ,0
Exp/Cntr=0.3,0.1

Type RM Length L Ch R = 1 ,3894.65 ,23.67,25.58,25.02
XS GIS Cut Line= 2
342564.8654785165422099.50732422342629.7084960945422052.65228271
#Sta/Elev= 27
       0   165.7   11.01  165.43   14.41  165.38   17.86  164.96   22.44  163.72
   27.28  160.63   27.77  160.31   31.34  156.24   35.47   151.5   35.72  151.33
   35.76  151.31   37.35  150.66    38.5  150.21   40.11  149.52   40.52  149.74
    41.5  150.01   43.68  150.62   46.17  150.74   51.63  150.61   57.27  151.54
   59.16  151.99   62.95     154   67.31  156.55    73.1  158.81   76.62  159.03
   77.45  159.27      80  159.62
#Mann= 3 , 0 , 0
       0    .057       0    38.5    .037       0    41.5    .057       0
Bank Sta=38.5,41.5
XS Rating Curve= 0 ,0
Exp/Cntr=0.3,0.1

Type RM Length L Ch R = 1 ,3869.08 ,21.81,23.66,24.62
XS GIS Cut Line= 2
342589.9974975595422104.68969727 342647.380676275422074.29052734
#Sta/Elev= 22
       0  165.38    7.23  164.51    7.37  164.38    9.58  162.51   19.35     154
   20.49  153.08   21.79  152.21    22.1  152.08   30.33  149.48   32.28  148.87
   33.22  148.98   33.57  149.04   42.21  150.57    43.7  150.54   43.83  150.57
   44.73  151.07   46.51  152.04   49.54  154.24   58.66  160.62   59.61  161.13
   64.22  163.04   64.94  163.06
#Mann= 3 , 0 , 0
       0    .057       0   30.33    .037       0   33.57    .057       0
Bank Sta=30.33,33.57
XS Rating Curve= 0 ,0
Exp/Cntr=0.3,0.1

Type RM Length L Ch R = 1 ,3845.41 ,15.32,23.19,28.59
XS GIS Cut Line= 3
342586.6223144535422113.60931396342615.4235229495422113.07470703
342669.9196777345422098.91967773
#Sta/Elev= 26
       0  165.45    1.22  165.37    7.89  164.63   10.53  164.09   14.46  162.83
   15.19  162.53   18.52  161.37   18.91  161.13   22.91  158.04   28.81  152.59
   31.48  150.12   33.05  149.45   36.99  149.61   42.23  148.85   43.61  148.71
    46.2  148.37   46.61  148.54   56.88  151.46   58.87  152.06   60.21  153.06
   65.43  157.81   74.94  162.29   76.15  162.78   77.09  162.79   79.13  163.08
   85.11  163.64
#Mann= 3 , 0 , 0
       0    .057       0   43.61     .04       0   46.61    .057       0
Bank Sta=43.61,46.61
XS Rating Curve= 0 ,0
Exp/Cntr=0.3,0.1

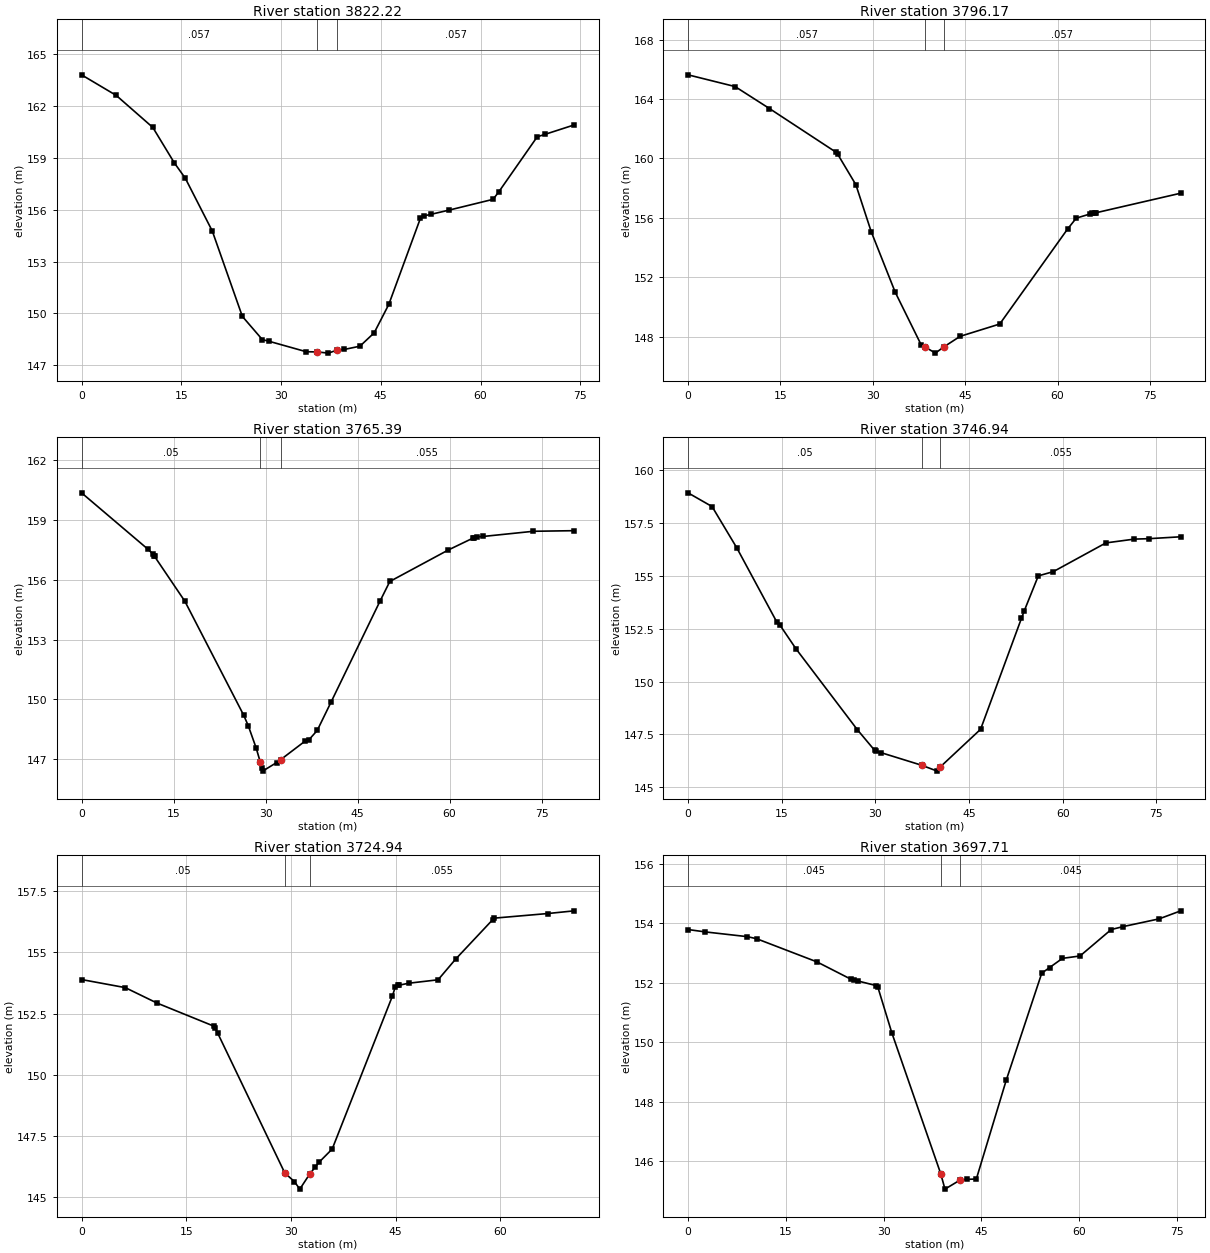
Type RM Length L Ch R = 1 ,3822.22 ,25.21,26.04,26.17
XS GIS Cut Line= 4
342593.7999267585422120.92547607342621.454528809 5422126.1072998
342641.5040893555422139.92492676342662.9362792975422142.68847656
#Sta/Elev= 26
       0  163.78    5.22  162.59   10.72  160.74   13.96  158.69    15.6  157.81
   19.66  154.76   24.18  149.83   27.19  148.49   28.14   148.4    33.8  147.79
   35.43  147.78   37.13  147.71   38.44  147.89   39.48  147.92   41.86  148.11
      44  148.88    46.2  150.52   50.95  155.49   51.43  155.63   52.49  155.72
   55.29  155.97   61.88  156.59   62.72  157.01   68.52   160.2   69.75  160.35
    74.1  160.89
#Mann= 3 , 0 , 0
       0    .057       0   35.43     .04       0   38.44    .057       0
Bank Sta=35.43,38.44
XS Rating Curve= 0 ,0
Exp/Cntr=0.3,0.1

Type RM Length L Ch R = 1 ,3796.17 ,31.62,30.78,27.51
XS GIS Cut Line= 2
342577.0494995125422124.41027832342641.5092773445422171.79107666
#Sta/Elev= 21
       0  165.63    7.64  164.84   13.22  163.36   24.02  160.42   24.32  160.27
   27.25  158.23   29.74  155.07   33.64  150.99   37.85  147.45    38.5   147.3
   40.16  146.89    41.5   147.3   44.17  148.02   50.61  148.85   61.61  155.24
   63.03  155.98   65.27  156.26   65.61   156.3   66.11  156.34   66.21  156.34
      80  157.66
#Mann= 3 , 0 , 0
       0    .057       0    38.5     .04       0    41.5    .057       0
Bank Sta=38.5,41.5
XS Rating Curve= 0 ,0
Exp/Cntr=0.3,0.1

Type RM Length L Ch R = 1 ,3765.39 ,20.27,18.45,17.11
XS GIS Cut Line= 5
 342576.861511235422158.57891846342597.2567138675422176.54211426
342617.997680664 5422182.0690918342629.0595092775422183.45092773
342648.4177246095422176.54211426
#Sta/Elev= 27
       0  160.37   10.78  157.55   11.61  157.31   11.83  157.21    11.9  157.18
   16.84  154.93   26.43  149.21   27.18  148.68   28.47  147.56   29.15 146.844
   29.41  146.57   29.52   146.4   31.81  146.83   32.44  146.97    36.5  147.92
   37.06  147.97   38.42  148.44   40.67  149.86   48.64  154.92   50.26  155.92
   59.79   157.5   63.84   158.1   63.91   158.1   64.41  158.16   65.49  158.18
   73.68  158.44   80.34  158.47
#Mann= 3 , 0 , 0
       0     .05       0   29.15     .04       0   32.44    .055       0
Bank Sta=29.15,32.44
XS Rating Curve= 0 ,0
Exp/Cntr=0.3,0.1

Type RM Length L Ch R = 1 ,3746.94 ,22.98,22,21.23
XS GIS Cut Line= 3
342561.0084838875422187.10968018342586.7915039065422195.47210693
342638.5668945315422196.66247559
#Sta/Elev= 22
       0  158.93    3.85  158.28    7.82  156.32   14.17  152.84   14.72  152.67
   17.28  151.55   27.11  147.72   29.86  146.75   30.07  146.71   30.84  146.64
   37.39  146.04    39.9  145.76   40.39  145.96   46.84  147.74   53.38  152.99
   53.81  153.33   56.08     155   58.48   155.2    66.9  156.56   71.46  156.74
   73.79  156.76   78.89  156.85
#Mann= 3 , 0 , 0
       0     .05       0   37.39     .04       0   40.39    .055       0
Bank Sta=37.39,40.39
XS Rating Curve= 0 ,0
Exp/Cntr=0.3,0.1

Type RM Length L Ch R = 1 ,3724.94 ,27.76,27.24,26.33
XS GIS Cut Line= 3
342570.6392822275422220.41351318342615.9235229495422215.92272949
342635.6275024415422200.37768555
#Sta/Elev= 24
       0  153.89    6.26  153.56    10.8  152.93   18.99  151.98    19.1  151.92
   19.52  151.69   29.12  145.98   30.49  145.63   31.27  145.32   32.68 145.932
    33.5  146.23   34.03  146.42   35.91  146.96   44.52   153.2   44.95  153.59
    45.3  153.65   45.51  153.66   46.88  153.74   51.08  153.88   53.58  154.72
   58.88  156.33    59.1   156.4   66.82  156.59    70.6   156.7
#Mann= 3 , 0 , 0
       0     .05       0   29.12     .04       0   32.68    .055       0
Bank Sta=29.12,32.68
XS Rating Curve= 0 ,0
Exp/Cntr=0.3,0.1

Type RM Length L Ch R = 1 ,3697.71 ,22.04,20,17.15
Node Photo=..\..\..\..\Corner Brook\Windshield Survey\CB photos\P1000751.JPG
XS GIS Cut Line= 4
342561.8685302735422255.54052734342586.4251098635422248.84692383
342614.6818847665422238.80328369342631.7954711915422228.23028564
#Sta/Elev= 25
       0  153.79    2.65  153.71    9.11  153.55   10.53  153.48   19.78   152.7
   25.05  152.11   25.45  152.09   26.02  152.06    28.9   151.9   29.11  151.85
   31.24  150.32   38.75  145.57    39.4  145.05   41.75  145.36   42.76  145.38
   44.21  145.39    48.8  148.72   54.24  152.32   55.44  152.51   57.42  152.82
   60.11   152.9   64.89  153.79   66.74  153.89   72.25  154.15   75.56  154.42
#Mann= 3 , 0 , 0
       0    .045       0   38.75     .04       0   41.75    .045       0
Bank Sta=38.75,41.75
XS Rating Curve= 0 ,0
Exp/Cntr=0.3,0.1

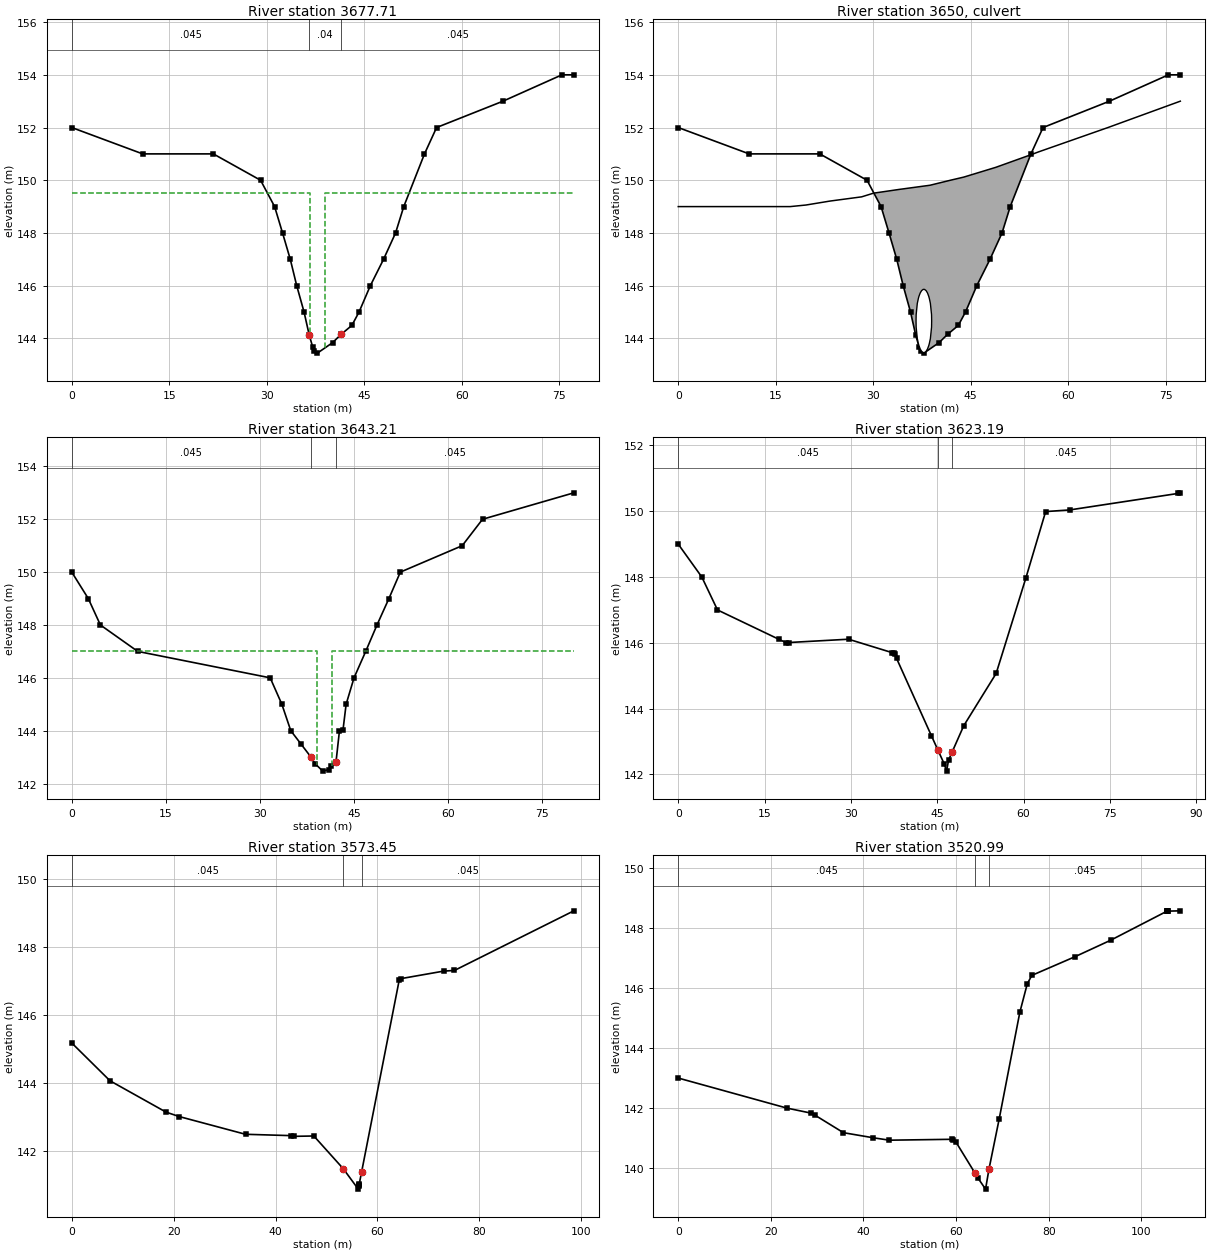
Type RM Length L Ch R = 1 ,3677.71 ,34.81,34.51,34.92
Node Photo=..\..\..\..\Corner Brook\Windshield Survey\CB photos\P1000749.JPG
XS GIS Cut Line= 5
      342581.381     5422290.777       342594.88     5422278.356
      342603.139     5422265.964      342616.658     5422253.301
      342632.211     5422233.107
#Sta/Elev= 26
       0     152   10.91     151   21.78     151   29.05     150   31.21     149
   32.43     148   33.62     147   34.61     146   35.74     145   36.54  144.12
   37.06  143.68   37.33  143.53   37.79  143.44   40.14  143.84   41.43  144.15
   43.09  144.49    44.2     145   45.94     146   47.97     147   49.82     148
   51.08     149   54.27     151   56.13     152   66.35     153   75.42     154
   77.25     154
#Mann= 3 , 0 , 0
       0    .045       0   36.54     .04       0   41.43    .045       0
#XS Ineff= 2 , 0
       0   36.59   149.5   38.99       0   149.5
Permanent Ineff=
       F       F
Bank Sta=36.54,41.43
XS Rating Curve= 0 ,0
Exp/Cntr=0.5,0.3

Type RM Length L Ch R = 2 ,3650    ,,,
Node Photo=..\..\..\..\Corner Brook\Windshield Survey\CB photos\P1000746.JPG
BEGIN DESCRIPTION:
Carberry's Road (Structure #2127)
END DESCRIPTION:
Bridge Culvert--1,0,-1,-1, 0
Deck Dist Width WeirC Skew NumUp NumDn MinLoCord MaxHiCord MaxSubmerge Is_Ogee
12.2,10.2,1.67,0, 15, 14, 149.44, , 0.98, 0, 0.62,0.76,,
       0   17.22   19.66   23.35   28.22   30.05   33.94   38.73   41.87   43.94
   48.86   54.62   55.37   66.12   77.25
     149     149  149.06  149.21  149.37  149.51  149.65  149.81     150  150.12
  150.49     151  151.07     152     153
                                                                                
                                        
       0   24.65   24.76   28.41   32.51   37.42      42   46.32   46.94   50.66
   56.34   60.32   71.97   80.01
     149     149     149  149.21  149.37  149.52   149.7  149.99     150   150.3
  150.67     151     152     153
                                                                                
                                
BR Coef=-1 , 0 , 0 ,, 0 ,,,0.8,-1,,0,
WSPro=,,,, 1 ,,,, 0 ,,,, 0 ,,,,-1 ,-1 ,-1 , 0 , 0 , 0 , 0 , 0
Culvert=1,2.4,,30.7,0.03,0.9,1,1,1,143.46,37.79,142.68,40.22,Culvert #1  , 0 ,2.1
Culvert Bottom n=0.03
BC Design=,, 0 ,, 0 ,,,,,,
BC Use User HTab Curves=0
BC User HTab FreeFlow(D)= 0

Type RM Length L Ch R = 1 ,3643.21 ,17.56,20,22.18
Node Photo=..\..\..\..\Corner Brook\Windshield Survey\CB photos\P1000748.JPG
XS GIS Cut Line= 2
 342605.160278325422320.60687256342654.2156982425422257.41229248
#Sta/Elev= 25
       0     150    2.63     149    4.56     148   10.51     147   31.62     146
   33.48     145    34.9     144   36.58  143.48   38.12     143   38.78  142.75
      40  142.47   40.99  142.53   41.34  142.65   42.11  142.82   42.66     144
   43.23  144.04   43.72     145   44.98     146   46.84     147   48.64     148
   50.54     149   52.36     150   62.22     151   65.46     152   80.01     153
#Mann= 3 , 0 , 0
       0    .045       0   38.12    .037       0   42.11    .045       0
#XS Ineff= 2 , 0
       0   39.02     147   41.42       0     147
Permanent Ineff=
       F       F
Bank Sta=38.12,42.11
XS Rating Curve= 0 ,0
Exp/Cntr=0.5,0.3

Type RM Length L Ch R = 1 ,3623.19 ,45.75,49.75,47.66
XS GIS Cut Line= 6
      342599.877     5422326.922      342609.182      5422328.25
      342616.302     5422324.453      342630.463     5422310.096
      342658.831     5422299.194      342664.661     5422280.874
#Sta/Elev= 24
       0     149     4.1     148    6.82     147   17.46  146.11   18.67  146.01
   19.27  146.01   29.59  146.11    37.2   145.7   37.57  145.69   37.63  145.67
   37.93  145.53   43.98  143.18   45.14 142.733   46.24  142.31   46.62   142.1
   46.98  142.44   47.61 142.689   49.61  143.48   55.24  145.07   60.42  147.98
   63.84  149.99   68.02  150.04    86.8  150.54   87.24  150.56
#Mann= 3 , 0 , 0
       0    .045       0   45.14    .037       0   47.61    .045       0
Bank Sta=45.14,47.61
XS Rating Curve= 0 ,0
Exp/Cntr=0.3,0.1

Type RM Length L Ch R = 1 ,3573.45 ,56.75,52.46,47.62
XS GIS Cut Line= 4
 342620.548889165422354.88171387342641.6436767585422355.42492676
342688.629272461 5422333.4296875342690.1923217775422307.91412354
#Sta/Elev= 19
       0  145.18    7.51  144.07   18.51  143.15    21.1  143.02    34.1   142.5
   43.12  142.46   43.71  142.44   47.51  142.45   53.28  141.49   56.23  140.89
   56.31  140.98   56.36     141   56.42  141.04   56.87 141.383   64.27  147.03
   64.62  147.07   72.98  147.29   75.11  147.31   98.54  149.06
#Mann= 3 , 0 , 0
       0    .045       0   53.28    .037       0   56.87    .045       0
Bank Sta=53.28,56.87
XS Rating Curve= 0 ,0
Exp/Cntr=0.3,0.1

Type RM Length L Ch R = 1 ,3520.99 ,56.39,47.15,45.97
XS GIS Cut Line= 6
      342647.911     5422397.571      342664.004     5422399.782
       342674.72     5422392.047      342690.795     5422393.634
      342713.301     5422351.502      342716.094     5422336.707
#Sta/Elev= 26
       0     143   23.44     142   28.74  141.83   29.46  141.77   35.68  141.18
   42.13  141.01   45.61  140.93   59.09  140.96   59.36  140.94   59.93  140.88
    64.1  139.83   64.72  139.67   66.37   139.3    67.1  139.96   69.33  141.65
   73.77  145.19   75.38  146.14   76.37  146.42   85.66  147.04   93.38  147.59
  105.57  148.56  105.61  148.56  105.62  148.56  105.67  148.56  105.81  148.56
  108.43  148.57
#Mann= 3 , 0 , 0
       0    .045       0    64.1    .037       0    67.1    .045       0
Bank Sta=64.1,67.1
XS Rating Curve= 0 ,0
Exp/Cntr=0.3,0.1

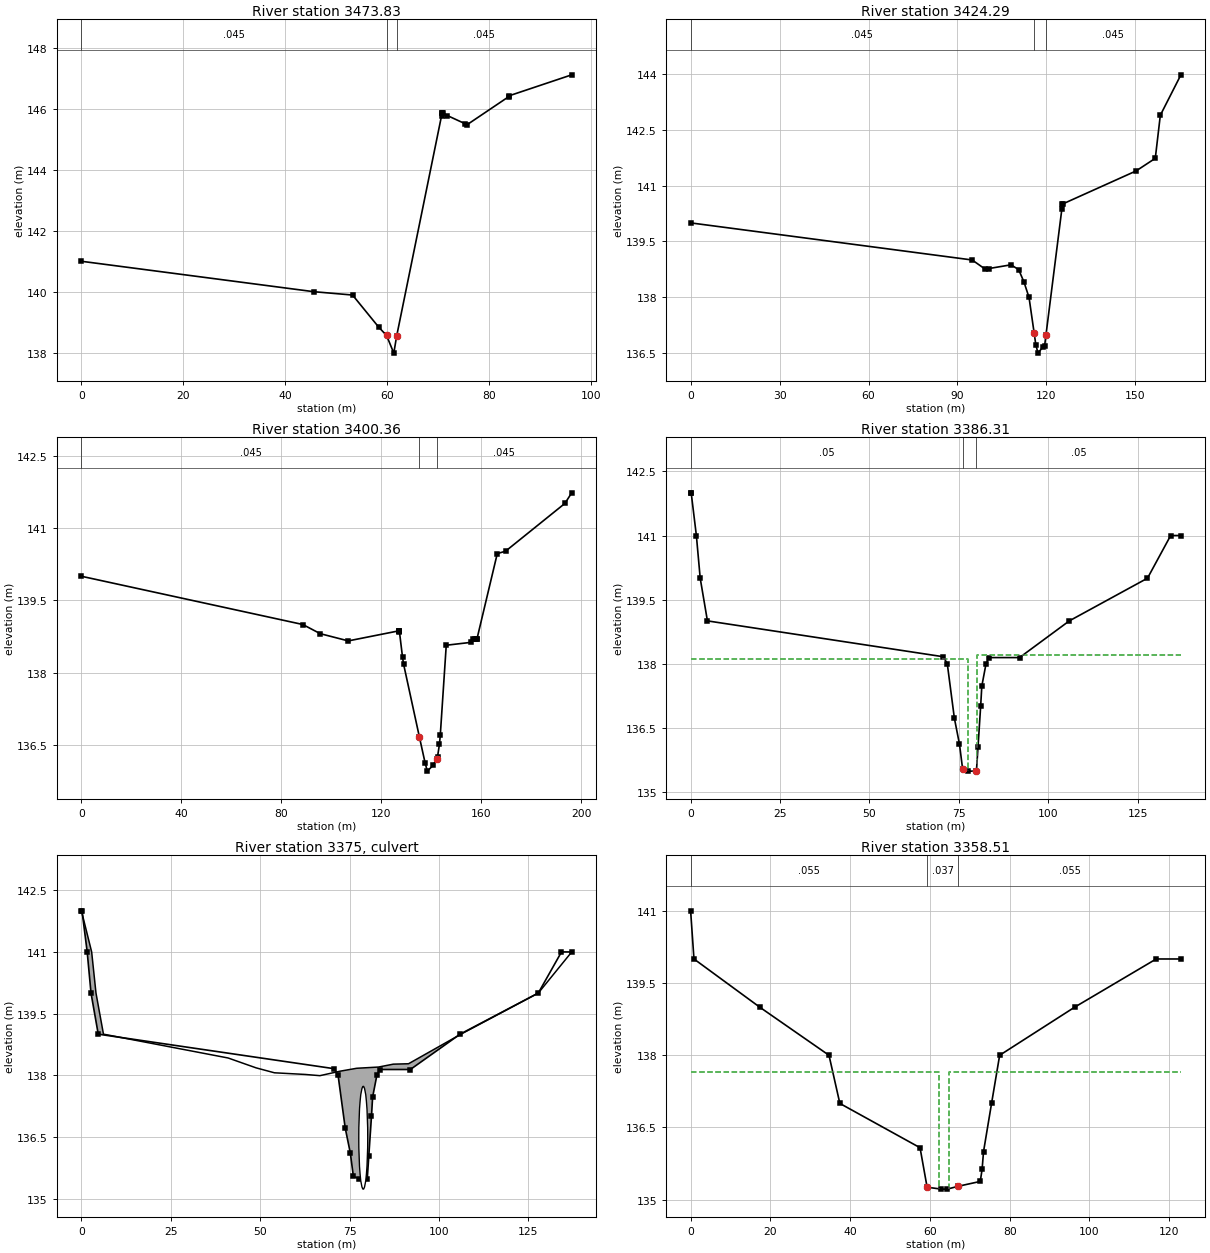
Type RM Length L Ch R = 1 ,3473.83 ,66.63,49.54,47.55
XS GIS Cut Line= 5
      342696.362     5422415.018      342708.325     5422403.506
      342743.513     5422393.535      342748.478     5422372.008
      342738.942     5422353.433
#Sta/Elev= 17
       0     141   45.55     140   53.17  139.89   58.27  138.84   59.84  138.56
   61.26  137.98   61.81 138.534   70.63  145.79   70.72  145.87   70.74  145.87
   70.86  145.88   71.77  145.79   75.27  145.52   75.63  145.49   83.78  146.41
   83.86  146.44   96.15  147.13
#Mann= 3 , 0 , 0
       0    .045       0   59.84    .037       0   61.81    .045       0
Bank Sta=59.84,61.81
XS Rating Curve= 0 ,0
Exp/Cntr=0.3,0.1

Type RM Length L Ch R = 1 ,3424.29 ,8.23,23.93,32.98
XS GIS Cut Line= 4
342741.0263061525422475.42547607342798.7764892585422393.02508545
342778.0883178715422347.92071533342764.7338867195422340.83691406
#Sta/Elev= 21
       0     140   94.97     139   99.23  138.76  100.62  138.77  108.07  138.87
  110.64  138.74  112.42  138.41  114.14  137.99  115.87  137.03  116.42  136.72
  117.15  136.49  118.87  136.66  119.38  136.68  119.85 136.978  125.22  140.38
  125.42  140.51   125.5  140.51  150.25   141.4  156.72  141.74  158.42   142.9
  165.36  143.99
#Mann= 3 , 0 , 0
       0    .045       0  115.87    .037       0  119.85    .045       0
Bank Sta=115.87,119.85
XS Rating Curve= 0 ,0
Exp/Cntr=0.3,0.1

Type RM Length L Ch R = 1 ,3400.36 ,30.11,14.07,14.53
Node Photo=..\..\..\..\Corner Brook\Windshield Survey\CB photos\P1000743.JPG
XS GIS Cut Line= 5
342741.6364746095422476.37109375 342803.951110845422421.63049316
342806.5554809575422376.14929199342815.2952880865422363.81768799
342817.5844726565422311.28552246
#Sta/Elev= 28
       0     140   88.58     139   95.56  138.81  106.78  138.66  127.17  138.87
  127.19  138.87  127.21  138.86  127.26  138.85   128.5  138.32  128.91  138.18
  135.28  136.66  137.53  136.13  138.42  135.96  140.73  136.08  142.16  136.22
  142.51  136.26  143.28  136.52  143.61  136.71  145.99  138.57  155.92  138.63
  156.89   138.7  157.45   138.7  158.21   138.7  158.28   138.7  166.41  140.47
  169.73  140.52  193.46  141.51   196.2  141.73
#Mann= 3 , 0 , 0
       0    .045       0  135.28    .037       0  142.16    .045       0
Bank Sta=135.28,142.16
XS Rating Curve= 0 ,0
Exp/Cntr=0.3,0.1

Type RM Length L Ch R = 1 ,3386.31 ,29.51,27.8,27.54
Node Photo=..\..\..\..\Corner Brook\Windshield Survey\CB photos\P1000744.JPG
XS GIS Cut Line= 4
 342822.208923345422442.65411377 342815.560729985422397.39172363
342839.7583007815422332.14831543342843.3023071295422310.68652344
#Sta/Elev= 22
       0     142     .16     142    1.61     141    2.68     140     4.7     139
   70.64  138.16   71.76     138   73.75  136.72   75.18  136.11   76.04  135.54
   77.68  135.48   79.92  135.48   80.35 136.034    81.1     137   81.42  137.47
   82.61     138   83.45  138.14   91.97  138.14  105.89     139  127.75     140
  134.23     141  137.09     141
#Mann= 3 , 0 , 0
       0     .05       0   76.04    .037       0   79.92     .05       0
#XS Ineff= 2 , 0
       0   77.55   138.1   80.05       0   138.2
Permanent Ineff=
       F       F
Bank Sta=76.04,79.92
XS Rating Curve= 0 ,0
Exp/Cntr=0.5,0.3

Type RM Length L Ch R = 2 ,3375    ,,,
Node Photo=..\..\..\..\Corner Brook\Windshield Survey\CB photos\P1000739.JPG
BEGIN DESCRIPTION:
Reids Road (Structure #2126)
END DESCRIPTION:
Bridge Culvert--1,0,-1,-1, 0
Deck Dist Width WeirC Skew NumUp NumDn MinLoCord MaxHiCord MaxSubmerge Is_Ogee
8.57,9.2,1.67,0, 17, 15, 138.02, , 0.98, 0, 0,0,,
       0    2.86    4.07    6.16   41.02   48.84   53.97   62.53   66.68   72.38
   76.97   83.09   87.19   91.46  106.13  127.75  137.09
     142     141     140     139  138.42  138.18  138.06  138.02  137.99   138.1
  138.17   138.2  138.27  138.28     139     140     141
                                                                                
                                                        
       0    3.53   30.69   36.27   41.89   50.14   54.71   59.64   65.76    71.3
   75.32   79.43   96.32  116.75  122.94
     140     139  138.42  138.18  138.06  138.04  137.95  138.05  138.12   138.2
  138.27  138.28     139     140     140
                                                                                
                                        
BR Coef=-1 , 0 , 0 ,, 0 ,,,0.8,-1,,0,
WSPro=,,,, 1 ,,,, 0 ,,,, 0 ,,,,-1 ,-1 ,-1 , 0 , 0 , 0 , 0 , 0
Culvert=1,2.5,,25.2,0.03,0.5,1,1,1,135.23,78.8,134.96,63.58,Culvert #1  , 0 ,1.3
Culvert Bottom n=0.035
Culvert Bottom Depth=0.25
Culvert Depth Blocked=0.25
BC Design=,, 0 ,, 0 ,,,,,,
BC Use User HTab Curves=0
BC User HTab FreeFlow(D)= 0

Type RM Length L Ch R = 1 ,3358.51 ,36.84,29.41,25.17
Node Photo=..\..\..\..\Corner Brook\Windshield Survey\CB photos\P1000740.JPG
XS GIS Cut Line= 4
 342850.251892095422435.83587646342847.4329223635422392.70129395
342864.3112792975422342.42590332342877.2770996095422319.11187744
#Sta/Elev= 18
       0     141     .84     140   17.32     139    34.7     138   37.42     137
   57.53  136.08    59.3  135.26   62.84  135.22   64.33  135.22   67.14  135.28
   72.63  135.38   73.09  135.63   73.45     136   75.46     137   77.49     138
   96.32     139  116.75     140  122.94     140
#Mann= 3 , 0 , 0
       0    .055       0    59.3    .037       0   67.14    .055       0
#XS Ineff= 2 , 0
       0   62.33  137.65   64.83       0  137.65
Permanent Ineff=
       F       F
Bank Sta=59.3,67.14
XS Rating Curve= 0 ,0
Exp/Cntr=0.5,0.3