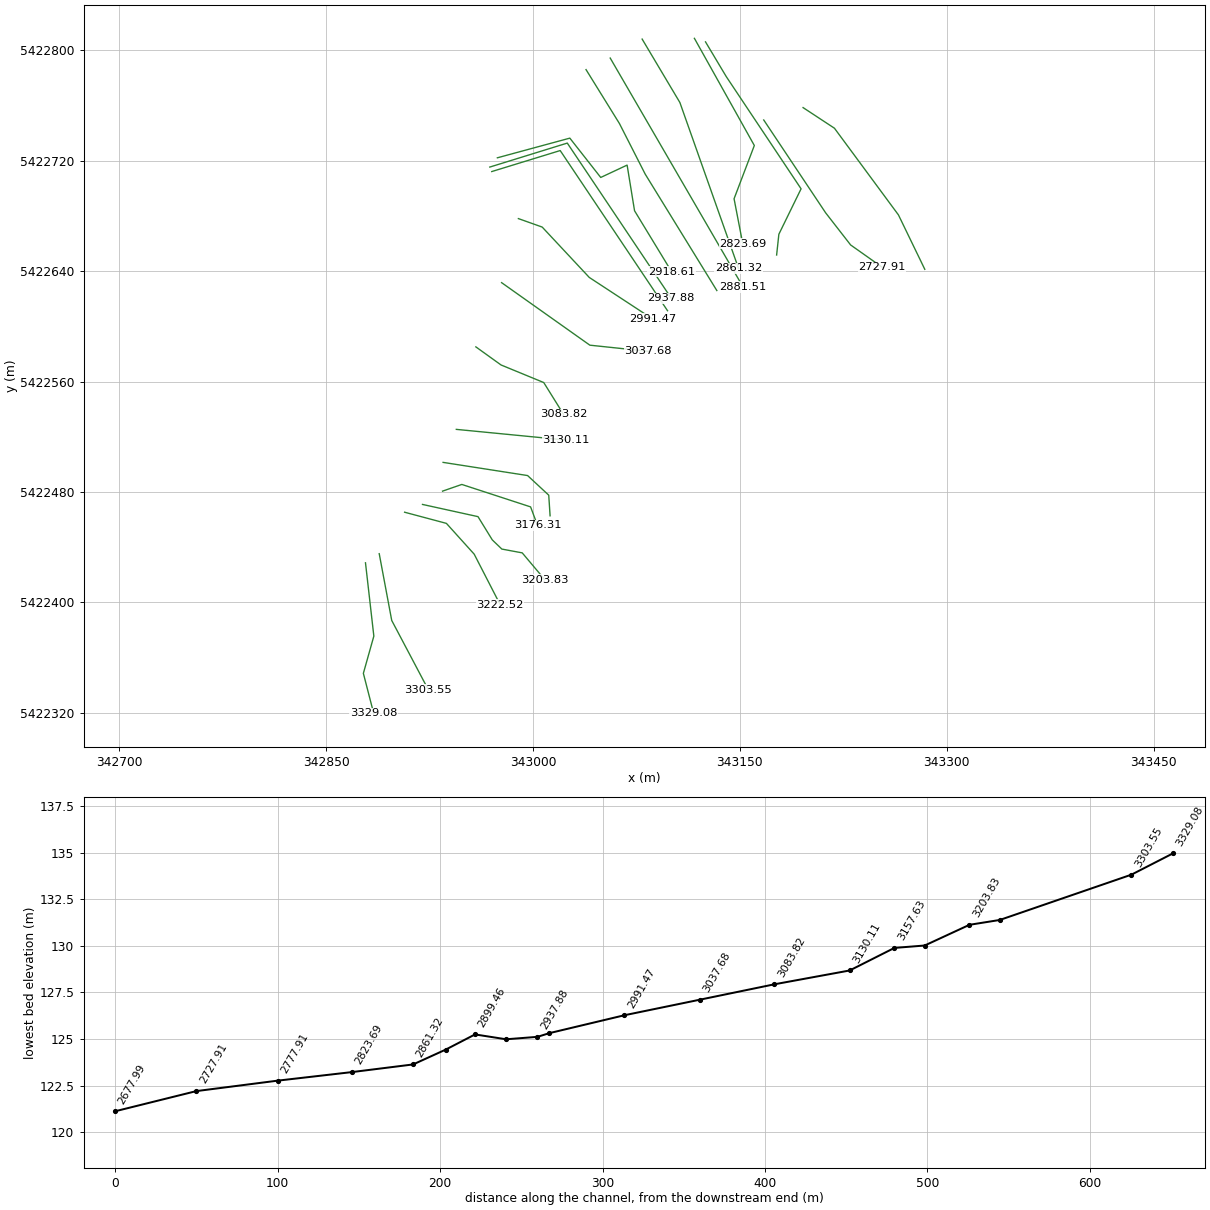
HEC-RAS study Corner_Brook2.prj: Corner_Brook2

--- Corner_Brook2.g03 (geometry) --- (continued)

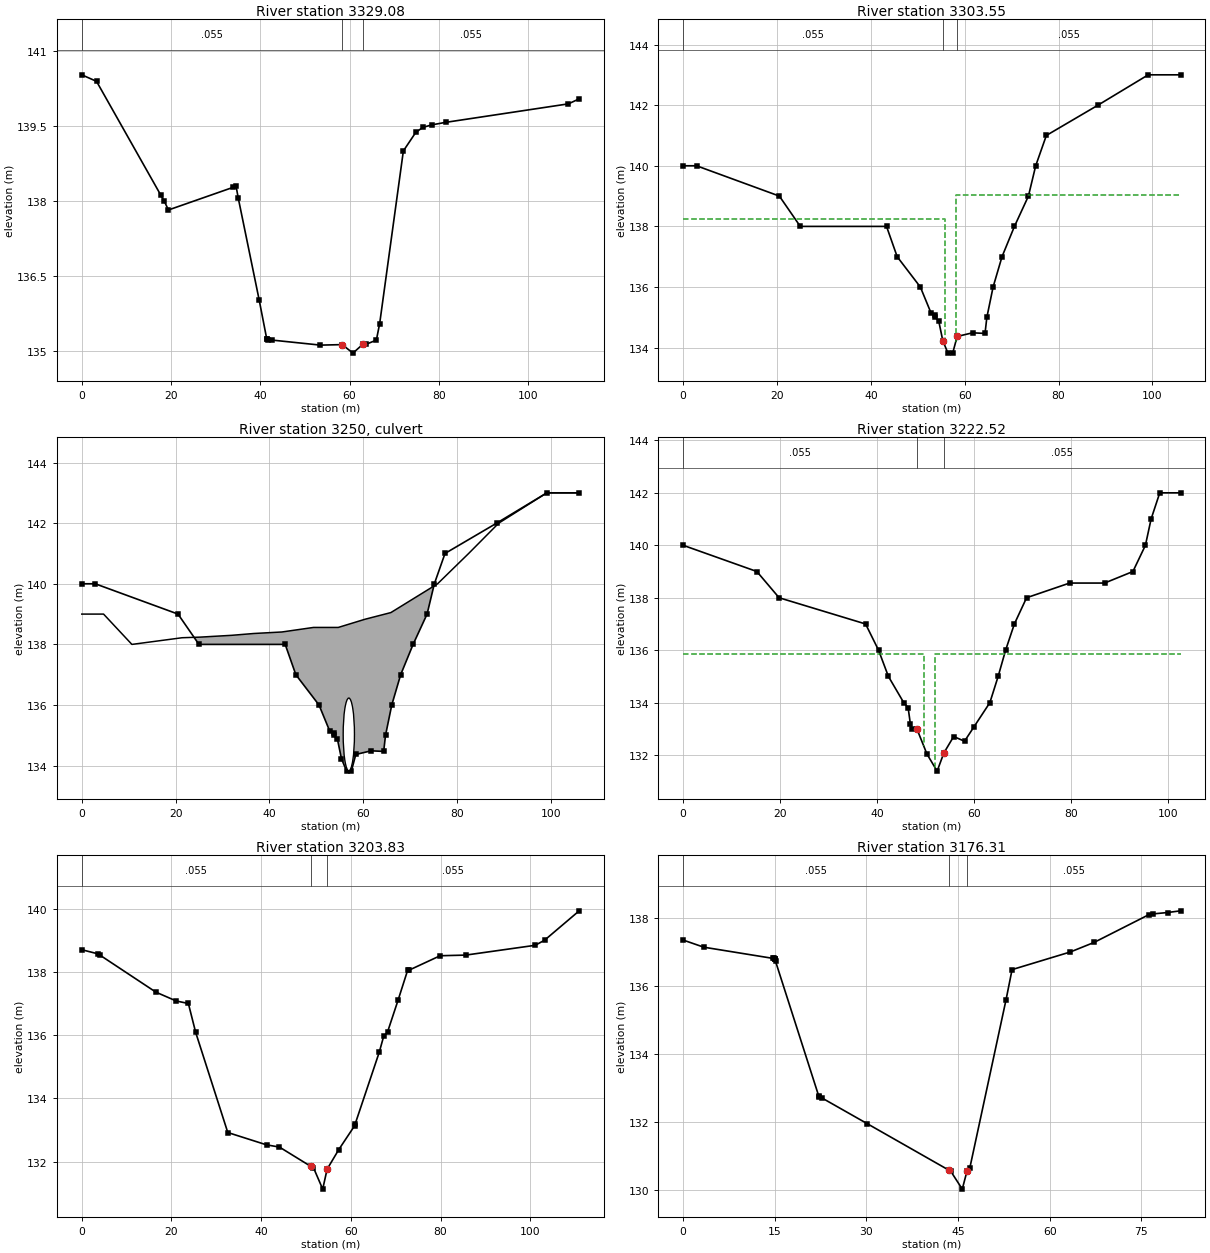
Type RM Length L Ch R = 1 ,3329.08 ,15.08,25.53,28.83
Node Photo=..\..\..\..\Corner Brook\Windshield Survey\CB photos\P1000738.JPG
XS GIS Cut Line= 4
342878.4979248055422428.72991943342884.5581054695422375.60827637
342876.9606933595422348.64331055342884.4547119145422319.64312744
#Sta/Elev= 27
       0  140.52     3.3  140.39   17.74  138.11   18.51  137.99   19.41  137.82
   33.83  138.27   34.57  138.29   35.07  138.05   39.72  136.03   41.42  135.25
   41.49  135.24   41.61  135.23   42.68  135.22   53.47  135.12   58.35  135.13
   60.74  134.96      63  135.14   63.78  135.14   65.99  135.22   66.73  135.55
   72.04     139   74.82  139.37    76.4  139.47    78.4  139.52   81.48  139.57
  109.01  139.94  111.43  140.04
#Mann= 3 , 0 , 0
       0    .055       0   58.35    .037       0      63    .055       0
Bank Sta=58.35,63
XS Rating Curve= 0 ,0
Exp/Cntr=0.3,0.1

Type RM Length L Ch R = 1 ,3303.55 ,77.91,81.04,82.42
Node Photo=..\..\..\..\Corner Brook\Windshield Survey\CB photos\P1000737.JPG
XS GIS Cut Line= 3
342888.4572753915422435.33532715342897.522888184  5422386.980896
342924.0737304695422336.75268555
#Sta/Elev= 27
       0     140    2.86     140   20.51     139   24.97     138   43.35     138
   45.62     137   50.56     136   52.87  135.13   53.65  135.07   53.66     135
   54.46  134.89   55.34  134.23   56.44  133.82   57.45  133.82    58.4  134.37
   61.68  134.49   64.34  134.47   64.73     135   66.06     136   67.96     137
   70.61     138   73.59     139   75.14     140   77.41     141   88.42     142
   99.12     143  106.01     143
#Mann= 3 , 0 , 0
       0    .055       0   55.34    .037       0    58.4    .055       0
#XS Ineff= 2 , 0
       0   55.71  138.24   58.11       0  139.05
Permanent Ineff=
       F       F
Bank Sta=55.34,58.4
XS Rating Curve= 0 ,0
Exp/Cntr=0.5,0.3

Type RM Length L Ch R = 2 ,3250    ,,,
Node Photo=..\..\..\..\Corner Brook\Windshield Survey\CB photos\P1000734.JPG
BEGIN DESCRIPTION:
Country Road @ O'Connell Drive (Structure #2124)
END DESCRIPTION:
Bridge Culvert--1,0,-1,-1, 0
Deck Dist Width WeirC Skew NumUp NumDn MinLoCord MaxHiCord MaxSubmerge Is_Ogee
23.9,33.7,1.67,0, 17, 16, 138, , 0.98, 0, 0.25,0.19,,
       0    4.64   10.68   21.38    25.2   31.95   36.67   42.65   49.38   54.66
   60.36   65.87   75.83   82.45   88.86   99.12  106.01
     139     139     138  138.22  138.24   138.3  138.36  138.41  138.56  138.56
  138.83  139.05     140     141     142     143     143
                                                                                
                                                        
       0    3.94    8.14   31.38   37.38   45.37   48.09   53.01   60.78   65.68
   71.92    77.6   83.32   93.42  100.05  102.67
     139     139     138  137.16  137.19  137.41  137.29  137.47  137.88  137.91
  138.56  138.83  139.05     140     141     141
                                                                                
                                                
BR Coef=-1 , 0 , 0 ,, 0 ,,,0.8,-1,,0,
WSPro=,,,, 1 ,,,, 0 ,,,, 0 ,,,,-1 ,-1 ,-1 , 0 , 0 , 0 , 0 , 0
Culvert=1,2.4,,73.9,0.03,0.5,1,1,1,133.83,56.91,132.04,50.87,Culvert #1  , 0 ,4.5
Culvert Bottom n=0.03
BC Design=,, 0 ,, 0 ,,,,,,
BC Use User HTab Curves=0
BC User HTab FreeFlow(D)= 0

Type RM Length L Ch R = 1 ,3222.52 ,20.45,18.68,16.9
Node Photo=..\..\..\..\Corner Brook\Windshield Survey\CB photos\P1000735.JPG
XS GIS Cut Line= 4
 342906.869323735422465.38110352342937.1802978525422457.29949951
 342957.333923345422434.97229004342976.2042846685422398.31750488
#Sta/Elev= 29
       0     140   15.22     139   19.81     138   37.66     137   40.34     136
   42.37     135   45.54     134   46.44  133.81   46.92  133.17   47.23     133
   48.27  132.99   50.33  132.04   52.43  131.39   53.81  132.08   55.84  132.71
   58.08  132.53   60.04 133.081   63.31     134   65.02     135   66.56     136
   68.37     137   70.89     138   79.77  138.56   86.99  138.56   92.84     139
   95.42     140   96.59     141   98.38     142  102.67     142
#Mann= 3 , 0 , 0
       0    .055       0   48.27    .037       0   53.81    .055       0
#XS Ineff= 2 , 0
       0   49.67  135.86   52.07       0  135.86
Permanent Ineff=
       F       F
Bank Sta=48.27,53.81
XS Rating Curve= 0 ,0
Exp/Cntr=0.5,0.3

Type RM Length L Ch R = 1 ,3203.83 ,18.78,27.53,31.97
XS GIS Cut Line= 6
342919.8419189455422471.01928711342960.0792846685422462.17608643
342970.4498901375422445.31829834342977.3635253915422438.68572998
342992.1586914065422435.92230225343008.4749145515422416.57727051
#Sta/Elev= 29
       0   138.7     3.6  138.57    4.04  138.53   16.51  137.36   21.05  137.08
   23.77     137   25.39  136.09   32.56  132.92    41.2  132.53   44.08  132.46
   51.07  131.85   51.42  131.82   51.66  131.81   53.73  131.13   54.71  131.76
   57.31  132.38   60.87  133.14   60.99   133.2   66.34  135.46   67.32  135.96
   68.19   136.1   70.57  137.12   72.69  138.06   73.08  138.06   79.92  138.51
   85.62  138.53  101.11  138.84   103.2     139  110.93  139.93
#Mann= 3 , 0 , 0
       0    .055       0   51.07    .037       0   54.71    .055       0
Bank Sta=51.07,54.71
XS Rating Curve= 0 ,0
Exp/Cntr=0.3,0.1

Type RM Length L Ch R = 1 ,3176.31 ,16.72,18.68,19.25
XS GIS Cut Line= 4
 342934.375122075422480.65289307342948.3464965825422485.50390625
342998.2213134775422469.24047852343003.1815185555422455.98931885
#Sta/Elev= 25
       0  137.35    3.38  137.14   14.72  136.81   14.79  136.81   14.97   136.8
   14.98   136.8   14.99   136.8   15.13  136.72   22.19  132.76   22.28  132.72
   22.74   132.7   30.09  131.95   43.47  130.58   43.78  130.55   45.68  130.02
   46.47  130.56    46.9  130.63   52.84  135.59   53.83  136.48   63.38     137
   67.25  137.28   76.25   138.1   76.94  138.12   79.27  138.16    81.4  138.21
#Mann= 3 , 0 , 0
       0    .055       0   43.47    .037       0   46.47    .055       0
Bank Sta=43.47,46.47
XS Rating Curve= 0 ,0
Exp/Cntr=0.3,0.1

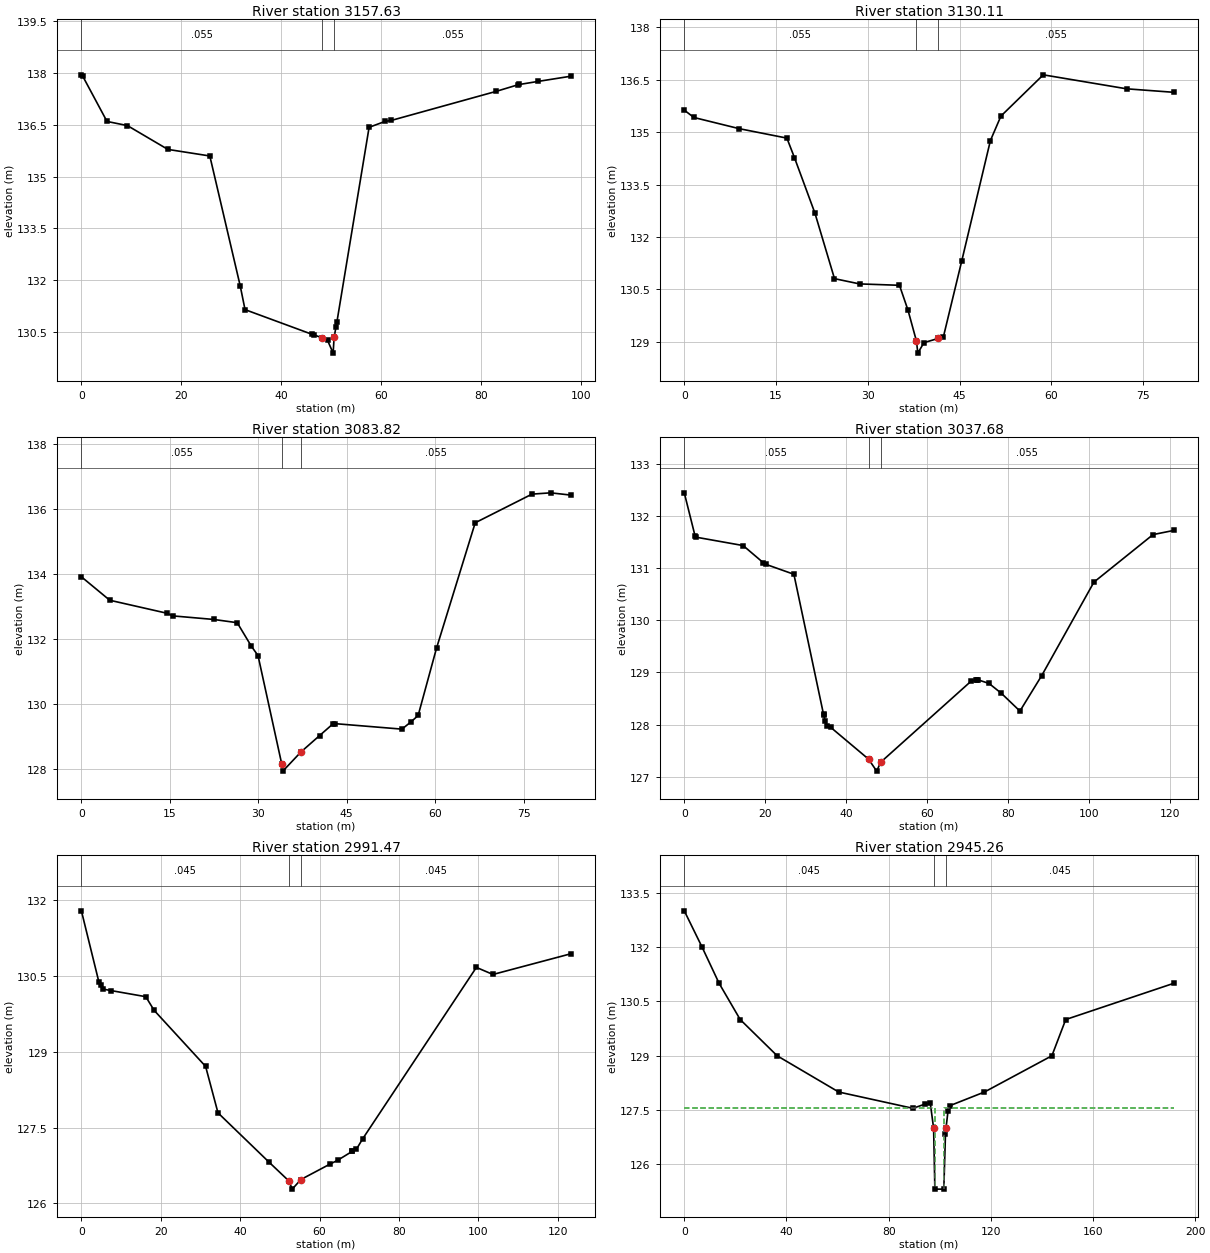
Type RM Length L Ch R = 1 ,3157.63 ,26.95,27.53,27.7
XS GIS Cut Line= 4
342934.7797241215422501.48413086342996.0344848635422491.94989014
343011.382873535 5422477.7175293343012.3507080085422462.79431152
#Sta/Elev= 24
       0  137.95     .27  137.91    5.12   136.6     9.2  136.48   17.29  135.79
   25.68   135.6   31.77  131.83   32.72  131.15   46.21  130.43   46.52  130.42
   48.14  130.33   49.22  130.26   50.34  129.89   50.53 130.343   50.91  130.65
   51.09  130.79   57.53  136.43    60.7   136.6   61.99  136.63   82.92  137.47
   87.26  137.66   87.57  137.67   91.35  137.76   97.88  137.91
#Mann= 3 , 0 , 0
       0    .055       0   48.14    .037       0   50.53    .055       0
Bank Sta=48.14,50.53
XS Rating Curve= 0 ,0
Exp/Cntr=0.3,0.1

Type RM Length L Ch R = 1 ,3130.11 ,47.22,46.27,43.59
XS GIS Cut Line= 2
342944.3775024415422525.39831543343024.0010986335422517.64727783
#Sta/Elev= 21
       0  135.63    1.57  135.42    8.98   135.1   16.77  134.83   18.01  134.27
   21.36  132.68   24.55  130.81   28.64  130.66   35.17  130.62   36.56  129.91
   37.94 129.027   38.17  128.68   39.17  128.98    41.5   129.1   42.34  129.14
   45.35  131.32   50.03  134.76   51.75  135.46   58.67  136.64   72.29  136.24
      80  136.14
#Mann= 3 , 0 , 0
       0    .055       0   37.94    .037       0    41.5    .055       0
Bank Sta=37.94,41.5
XS Rating Curve= 0 ,0
Exp/Cntr=0.3,0.1

Type RM Length L Ch R = 1 ,3083.82 ,47.22,46.14,46.83
XS GIS Cut Line= 4
 342958.537292485422585.16668701342976.7575073245422572.07971191
343007.7532958985422559.33209229343022.0814819345422536.35168457
#Sta/Elev= 22
       0  133.91    4.81  133.19   14.53  132.79   15.47  132.71   22.43   132.6
   26.43   132.5   28.82  131.78   29.96  131.49   33.98  128.16   34.17  127.94
   37.25  128.53   40.39  129.03   42.66  129.39   42.94   129.4   54.37  129.23
   55.95  129.46   57.12  129.65   60.24  131.72    66.8  135.57   76.43  136.45
    79.6  136.49   83.03  136.42
#Mann= 3 , 0 , 0
       0    .055       0   33.98    .037       0   37.25    .055       0
Bank Sta=33.98,37.25
XS Rating Curve= 0 ,0
Exp/Cntr=0.3,0.1

Type RM Length L Ch R = 1 ,3037.68 ,49.3,46.21,45.52
XS GIS Cut Line= 3
342977.193115234 5422631.7020874 343041.185485845422586.40209961
343083.5668945315422581.93988037
#Sta/Elev= 26
       0  132.44    2.68  131.61    2.95  131.59   14.55  131.43   19.56   131.1
   20.19  131.07    27.1  130.88   34.42   128.2   34.51  128.18   34.81  128.07
   35.25  127.98   36.18  127.95   45.55  127.34   47.57  127.11   48.55  127.28
   70.87  128.83   72.03  128.86   72.45  128.86   72.54  128.86   75.33  128.79
    78.4   128.6   82.98  128.26   88.37  128.94  101.28  130.73  115.89  131.64
  121.02  131.72
#Mann= 3 , 0 , 0
       0    .055       0   45.55    .037       0   48.55    .055       0
Bank Sta=45.55,48.55
XS Rating Curve= 0 ,0
Exp/Cntr=0.3,0.1

Type RM Length L Ch R = 1 ,2991.47 ,58.07,46.21,37.18
Node Photo=..\..\..\..\Corner Brook\Windshield Survey\CB photos\P1000733.JPG
XS GIS Cut Line= 4
342989.3674926765422678.10650635343006.6290893555422671.96868896
343040.7589111335422635.49371338343086.8018798835422605.33392334
#Sta/Elev= 22
       0  131.79    4.41  130.38    4.84  130.32    5.47  130.24    7.54  130.21
   16.22  130.09   18.32  129.82   31.29  128.71   34.41  127.79   47.19  126.82
   52.29  126.44   53.11  126.28   55.29  126.47   62.73  126.78   64.53  126.85
   68.27  127.03   68.28  127.03   69.28  127.07   70.89  127.28    99.5  130.67
  103.68  130.53  123.31  130.94
#Mann= 3 , 0 , 0
       0    .045       0   52.29    .037       0   55.29    .045       0
Bank Sta=52.29,55.29
XS Rating Curve= 0 ,0
Exp/Cntr=0.3,0.1

Type RM Length L Ch R = 1 ,2945.26 ,7.49,7.38,7.56
Node Photo=..\..\..\..\Corner Brook\Windshield Survey\CB photos\P1000730.JPG
XS GIS Cut Line= 3
       342970.06     5422712.187      343019.685     5422727.405
      343097.517     5422611.367
#Sta/Elev= 20
       0     133    6.96     132   13.63     131   21.89     130   36.36     129
   60.45     128   89.52  127.55   94.37  127.67   96.31  127.69   97.61     127
    98.1  125.32   101.6  125.32  102.25  126.84  102.45     127  103.24  127.47
  103.87  127.62  117.51     128  143.91     129  149.33     130  191.63     131
#Mann= 3 , 0 , 0
       0    .045       0   97.61    .037       0  102.45    .045       0
#XS Ineff= 2 , 0
       0    98.1  127.55   101.6       0  127.57
Permanent Ineff=
       F       F
Bank Sta=97.61,102.45
XS Rating Curve= 0 ,0
Exp/Cntr=0.5,0.3

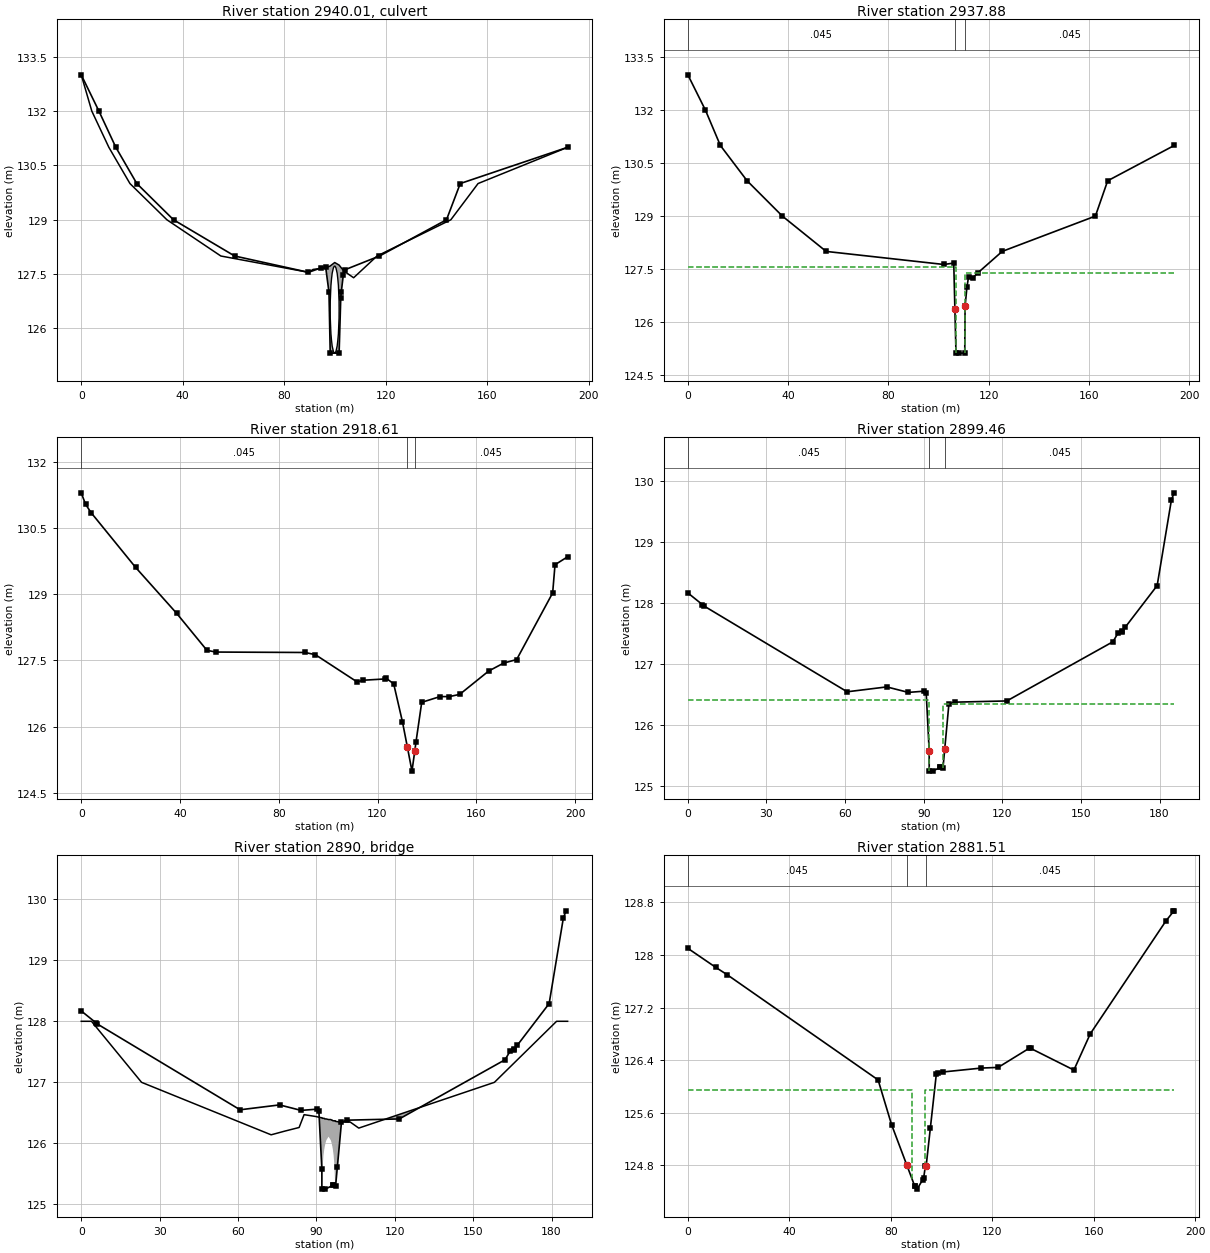
Type RM Length L Ch R = 2 ,2940.01 ,,,
Node Photo=..\..\..\..\Corner Brook\Windshield Survey\CB photos\P1000732.JPG
BEGIN DESCRIPTION:
Driveway (Structure #2123)
END DESCRIPTION:
Bridge Culvert--1,0,-1,-1, 0
Deck Dist Width WeirC Skew NumUp NumDn MinLoCord MaxHiCord MaxSubmerge Is_Ogee
1,5.5,1.67,0, 19, 18, 127.55, , 0.98, 0, 0,0,,
       0    4.16   10.88   19.19   33.75   55.01   89.55   91.35   95.95   97.99
   99.87   101.6  102.49   103.8  107.32  116.54  145.62  156.35  191.63
     133     132     131     130     129     128  127.55  127.63  127.67  127.72
  127.82  127.75  127.67  127.57   127.4     128     129     130     131
                                                                                
                                                                        
       0    7.01   12.97   23.64   37.71   55.19   98.45  102.12  106.29  106.87
  109.55  110.71  112.69  115.87  125.43  162.62  167.52  194.08
     133     132     131     130     129     128  127.55  127.63  127.72  127.71
  127.78  127.69  127.57   127.4     128     129     130     131
                                                                                
                                                                
BR Coef=-1 , 0 , 0 ,, 0 ,,,0.8,-1,,0,
WSPro=,,,, 1 ,,,, 0 ,,,, 0 ,,,,-1 ,-1 ,-1 , 0 , 0 , 0 , 0 , 0
Culvert=5,2.4,3.5,5.5,0.03,0.5,1,41,1,125.32,99.85,125.12,108.74,Culvert #1  , 0 ,1
Culvert Bottom n=0.03
BC Design=,, 0 ,, 0 ,,,,,,
BC Use User HTab Curves=0
BC User HTab FreeFlow(D)= 0

Type RM Length L Ch R = 1 ,2937.88 ,4.94,19.28,13.14
Node Photo=..\..\..\..\Corner Brook\Windshield Survey\CB photos\P1000731.JPG
XS GIS Cut Line= 3
342968.6340942385422715.44329834343024.8264770515422732.81750488
 343100.17590332  5422620.480896
#Sta/Elev= 21
       0     133    7.01     132   12.97     131   23.64     130   37.71     129
   55.19     128  102.16  127.63   106.1  127.67  106.55 126.381  106.99  125.12
  108.34  125.12  110.49  125.12  110.62  126.45  111.38     127  112.01  127.28
  113.63  127.25  115.83   127.4  125.43     128  162.62     129  167.52     130
  194.08     131
#Mann= 3 , 0 , 0
       0    .045       0  106.55    .037       0  110.62    .045       0
#XS Ineff= 2 , 0
       0  106.99  127.55  110.49       0   127.4
Permanent Ineff=
       F       F
Bank Sta=106.55,110.62
XS Rating Curve= 0 ,0
Exp/Cntr=0.5,0.3

Type RM Length L Ch R = 1 ,2918.61 ,34.67,19.14,22.57
XS GIS Cut Line= 6
342974.1320800785422722.15911865343026.6691284185422736.40472412
343049.0684814455422707.91351318343068.2098999025422716.86791992
343073.5969238285422683.78411865343100.4652709965422639.64147949
#Sta/Elev= 29
       0   131.3    1.75  131.04       4  130.85   22.01  129.61   38.61  128.57
    50.9  127.73   54.43  127.69   90.68  127.68   94.84  127.63  111.81  127.01
  113.97  127.05  123.01  127.08  123.39   127.1  126.55  126.97   130.1  126.11
  132.08  125.54  133.96  124.99  135.08  125.44  135.61  125.66  137.91  126.55
  145.33  126.68   149.1  126.68  153.29  126.73  165.04  127.26  171.11  127.44
  176.36  127.52  190.94  129.03   191.9  129.67     197  129.85
#Mann= 3 , 0 , 0
       0    .045       0  132.08    .037       0  135.08    .045       0
Bank Sta=132.08,135.08
XS Rating Curve= 0 ,0
Exp/Cntr=0.3,0.1

Type RM Length L Ch R = 1 ,2899.46 ,18.33,17.95,18.23
Node Photo=..\..\..\..\Corner Brook\Windshield Survey\CB photos\P1000728.JPG
XS GIS Cut Line= 4
      343038.424     5422786.044      343062.654     5422746.953
      343081.347     5422710.283      343133.261     5422625.989
#Sta/Elev= 26
       0  128.17     5.5  127.98       6  127.96   60.79  126.55    75.9  126.63
   84.12  126.54   90.21  126.56   90.95  126.53   92.09  125.58    92.1  125.25
   93.37  125.25   96.25  125.31    96.4  125.31   97.35   125.3   98.03 125.616
   99.61  126.35  101.81  126.38  121.72   126.4  162.21  127.37  164.27  127.52
  165.59  127.53  165.75  127.54  166.94  127.61  179.08  128.29  184.55   129.7
   185.6  129.81
#Mann= 3 , 0 , 0
       0    .045       0   92.09    .035       0   98.03    .045       0
#XS Ineff= 2 , 0
       0    92.1  126.42   97.19       0  126.35
Permanent Ineff=
       F       F
Bank Sta=92.09,98.03
XS Rating Curve= 0 ,0
Exp/Cntr=0.5,0.3

Type RM Length L Ch R = 3 ,2890    ,,,
Node Photo=..\..\..\..\Corner Brook\Windshield Survey\CB photos\P1000726.JPG
BEGIN DESCRIPTION:
Boones Road (Structure #2122)
END DESCRIPTION:
Bridge Culvert--1,0,-1,-1, 0
Deck Dist Width WeirC Skew NumUp NumDn MinLoCord MaxHiCord MaxSubmerge Is_Ogee
3.3,6.8,1.67,0, 39, 37, 126.14, , 0.98, 0, 0,0,,
       0    3.92   23.08   72.68   77.87   83.39   85.29   89.77   91.88   91.89
   91.93   92.01   92.13   92.29   92.53   92.71   93.01   93.22   93.47   93.79
   94.66   95.53   95.85    96.1   96.31   96.61   96.79   97.03   97.19   97.31
   97.38   97.43   97.44   98.76  102.92  106.22  158.14  181.93  186.15
     128     128     127  126.14   126.2  126.26  126.47  126.44  126.42  126.42
  126.42  126.42  126.42  126.41  126.41  126.41  126.41   126.4   126.4   126.4
  126.39  126.39  126.38  126.38  126.37  126.37  126.37  126.37  126.37  126.36
  126.36  126.36  126.36  126.35  126.35  126.25     127     128     128
                                                                  124.56   124.7
   124.9   125.1   125.3   125.5   125.7   125.8   125.9  125.95     126  126.05
  126.11  126.05     126  125.95   125.9   125.8   125.7   125.5   125.3   125.1
   124.9   124.7  124.56
       0    2.16   21.06   69.01   74.17   79.66   86.02   88.24   88.28   88.33
   88.39   88.52   88.69   88.96   89.16   89.54   89.78   90.08   90.55   91.02
    91.5   91.96   92.26    92.5   92.85   93.09   93.35   93.53   93.65   93.71
   93.76    93.8   97.25  101.94  155.03  179.79  191.76
     128     128     127  126.14   126.2  126.26  126.27  126.27  126.27  126.27
  126.27  126.27  126.27  126.27  126.27  126.27  126.27  126.27  126.27  126.27
  126.26  126.26  126.26  126.26  126.26  126.26  126.26  126.26  126.26  126.26
  126.26  126.26  126.26  126.22     127     128     129
                                                          124.12   124.4  124.56
   124.7   124.9   125.1   125.3   125.4   125.5  125.55   125.6  125.65  125.67
  125.65   125.6  125.55   125.5   125.4   125.3   125.1   124.9   124.7  124.56
   124.4  124.12
BR Coef=-1 , 0 , 0 ,, 0 ,,,0.8,-1,,0,
WSPro=,,,, 1 ,,,, 0 ,,,, 0 ,,,,-1 ,-1 ,-1 , 0 , 0 , 0 , 0 , 0
BC Design=,, 0 ,, 0 ,,,,,,
BC Use User HTab Curves=0
BC User HTab FreeFlow(D)= 0

Type RM Length L Ch R = 1 ,2881.51 ,26.39,20.19,15.85
Node Photo=..\..\..\..\Corner Brook\Windshield Survey\CB photos\P1000727.JPG
XS GIS Cut Line= 2
 343055.954895025422794.41247559343152.2583007815422628.60229492
#Sta/Elev= 26
       0   128.1   11.02  127.81   15.46   127.7      75   126.1   80.31  125.42
   86.32 124.805    89.4  124.49    89.5  124.49   90.37  124.44   92.54  124.58
   92.96  124.61   93.64  124.79   93.94  124.79    95.6 125.368   97.96  126.19
   98.64  126.21  100.43  126.22  115.65  126.28  122.32  126.29  134.53  126.58
  135.12  126.58  152.19  126.25  158.64   126.8  188.54  128.52  191.45  128.66
  191.75  128.67
#Mann= 3 , 0 , 0
       0    .045       0   86.32    .035       0   93.94    .045       0
#XS Ineff= 2 , 0
       0   88.35  125.95    93.6       0  125.95
Permanent Ineff=
       F       F
Bank Sta=86.32,93.94
XS Rating Curve= 0 ,0
Exp/Cntr=0.5,0.3

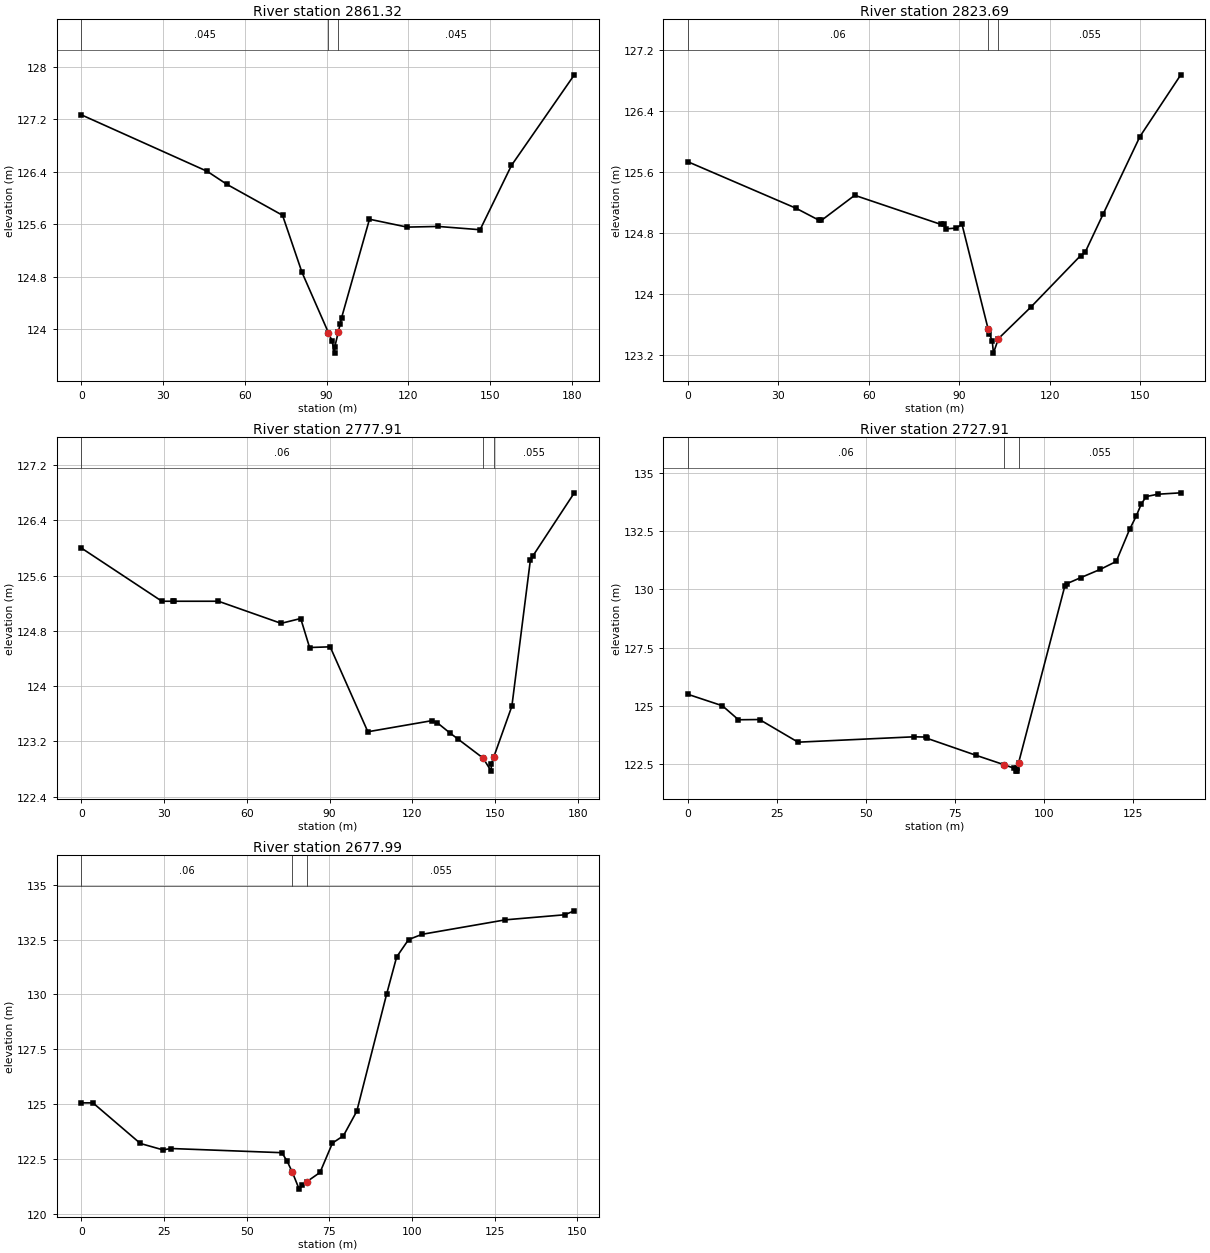
Type RM Length L Ch R = 1 ,2861.32 ,36.84,37.63,19.88
XS GIS Cut Line= 3
343079.1082763675422808.15112305343106.4719238285422762.20788574
343149.0048828135422642.02648926
#Sta/Elev= 18
       0  127.27   46.17  126.41   53.47  126.21   73.84  125.74   80.98  124.87
   90.66 123.954   91.97  123.83   92.95  123.64   93.05  123.74   94.28 123.958
   94.97  124.08   95.52  124.18  105.76  125.68  119.57  125.56     131  125.57
  146.37  125.52  157.89   126.5  180.96  127.88
#Mann= 3 , 0 , 0
       0    .045       0   90.66    .035       0   94.28    .045       0
Bank Sta=90.66,94.28
XS Rating Curve= 0 ,0
Exp/Cntr=0.3,0.1

Type RM Length L Ch R = 1 ,2823.69 ,30.98,45.79,43.12
XS GIS Cut Line= 4
343116.9957275395422808.70892334 343160.449096685422731.05889893
343145.7584838875422692.48370361343152.0548706055422659.88208008
#Sta/Elev= 21
       0  125.74   35.87  125.13   43.62  124.97   44.25  124.97   55.32   125.3
   83.78  124.92   85.09  124.93   85.64  124.86   88.98  124.87    90.9  124.92
   99.61  123.54  100.02  123.48  100.94  123.39  101.33  123.23  102.98  123.42
  113.65  123.83  130.26  124.51  131.71  124.55  137.67  125.05  149.91  126.07
  163.46  126.88
#Mann= 3 , 0 , 0
       0     .06       0   99.61     .04       0  102.98    .055       0
Bank Sta=99.61,102.98
XS Rating Curve= 0 ,0
Exp/Cntr=0.3,0.1

Type RM Length L Ch R = 1 ,2777.91 ,18.27,50,52.04
XS GIS Cut Line= 5
      343125.059     5422806.133      343140.039     5422781.071
      343194.347      5422699.69      343178.237     5422666.772
      343176.616     5422651.727
#Sta/Elev= 22
       0     126   29.19  125.23   33.26  125.23    33.7  125.23    49.7  125.23
   72.44  124.91   79.55  124.98   82.77  124.56   90.24  124.57  103.91  123.34
  127.03   123.5  129.11  123.47  133.76  123.32  136.76  123.23  145.71 122.959
  148.66  122.77  148.71 122.876  149.57 122.972  156.16  123.71  162.88  125.83
  163.68  125.88  178.81   126.8
#Mann= 3 , 0 , 0
       0     .06       0  145.71     .04       0  149.57    .055       0
Bank Sta=145.71,149.57
XS Rating Curve= 0 ,0
Exp/Cntr=0.3,0.1

Type RM Length L Ch R = 1 ,2727.91 ,50.49,49.91,45.74
XS GIS Cut Line= 4
343167.2744750985422749.55352783343212.1629028325422682.28771973
343230.2714843755422659.01647949343253.1824951175422642.84570313
#Sta/Elev= 26
       0   125.5    9.68  125.01    14.2  124.41   20.11  124.42   30.93  123.45
   63.44  123.68   66.79  123.67   67.06  123.62   80.87  122.89   88.66  122.49
    91.7  122.33   92.15  122.21   92.37  122.21    92.5  122.34   92.85  122.56
  105.88  130.16  106.43  130.24  110.35   130.5  115.77  130.85  120.27  131.19
  124.02  132.56  125.88  133.13  127.31  133.65  128.69  133.97  131.93  134.07
   138.4  134.13
#Mann= 3 , 0 , 0
       0     .06       0   88.66     .04       0   92.85    .055       0
Bank Sta=88.66,92.85
XS Rating Curve= 0 ,0
Exp/Cntr=0.3,0.1

Type RM Length L Ch R = 1 ,2677.99 ,30.93,49.91,53.27
XS GIS Cut Line= 4
343195.7907104495422758.52947998343218.5405273445422743.58673096
343264.958312988 5422680.7545166343284.0593261725422641.36248779
#Sta/Elev= 22
       0  125.06    3.48  125.06   17.83  123.21   24.63  122.92   27.22  122.98
   60.66  122.79   62.28  122.39   63.84  121.89   65.87  121.13   66.84  121.33
   68.24 121.474   72.18  121.89   75.95  123.23   79.26  123.56   83.31  124.68
   92.31     130   95.37  131.71   98.98   132.5  103.06  132.74  128.29   133.4
   146.2  133.63  149.12  133.81
#Mann= 3 , 0 , 0
       0     .06       0   63.84     .04       0   68.24    .055       0
Bank Sta=63.84,68.24
XS Rating Curve= 0 ,0
Exp/Cntr=0.3,0.1