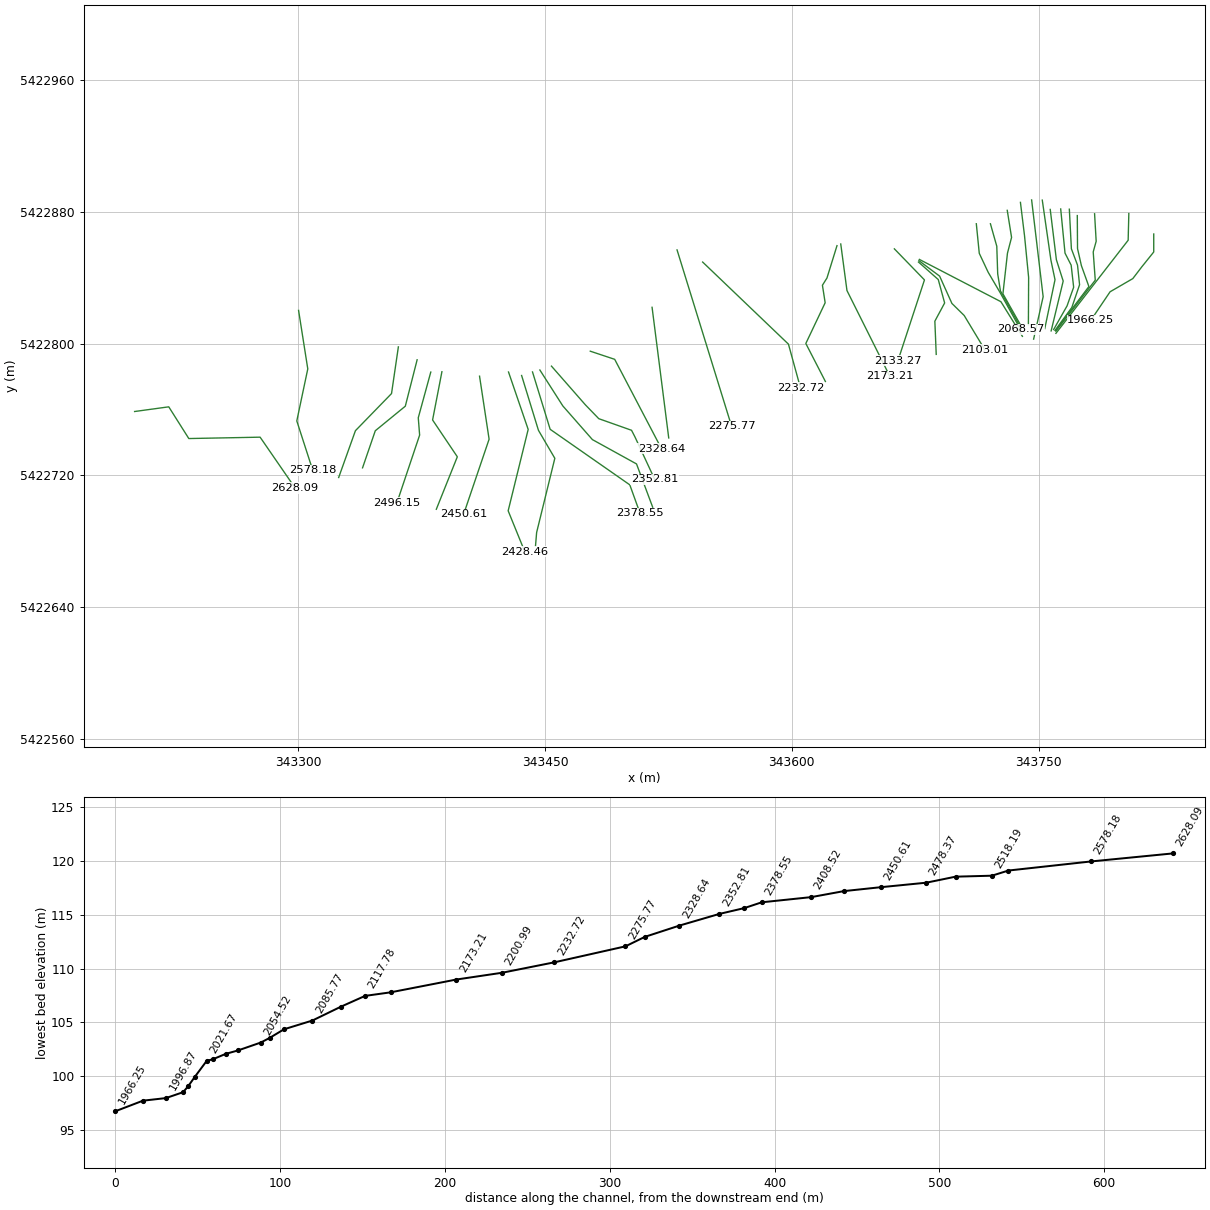
HEC-RAS study Corner_Brook2.prj: Corner_Brook2

--- Corner_Brook2.g03 (geometry) --- (continued)

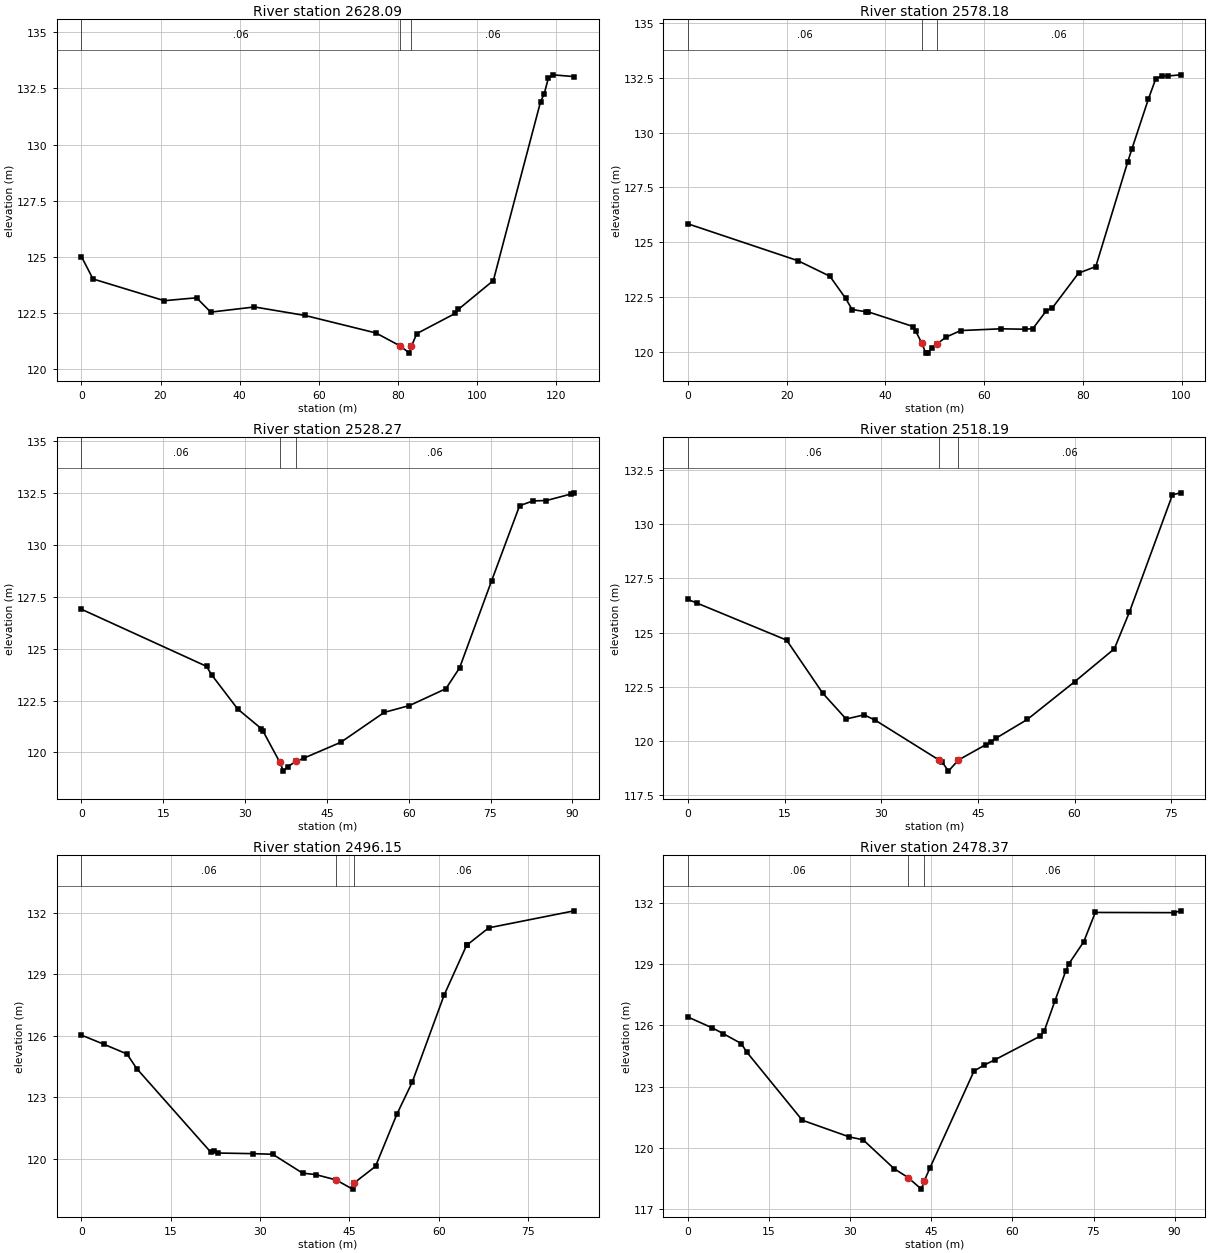
Type RM Length L Ch R = 1 ,2628.09 ,74.09,49.91,27.82
XS GIS Cut Line= 5
      343200.431     5422758.864      343221.187     5422761.703
      343233.375      5422742.44       343276.73     5422743.274
      343298.006     5422712.411
#Sta/Elev= 20
       0     125    2.92     124   20.95  123.03    29.1  123.16   32.69  122.52
   43.75  122.75   56.56  122.37   74.45  121.59   80.58  121.01   82.93  120.69
   83.43 120.998   84.78  121.56   94.47  122.46   95.27  122.64  104.14  123.93
  116.06   131.9  116.99  132.26  118.03  132.95  119.18  133.11  124.59  133.03
#Mann= 3 , 0 , 0
       0     .06       0   80.58     .04       0   83.43     .06       0
Bank Sta=80.58,83.43
XS Rating Curve= 0 ,0
Exp/Cntr=0.3,0.1

Type RM Length L Ch R = 1 ,2578.18 ,51.62,49.91,42.47
XS GIS Cut Line= 4
343300.1138916025422820.29492188343305.7077026375422784.74267578
343299.030090332 5422753.1427002343308.7435302735422723.11151123
#Sta/Elev= 30
       0  125.84   22.26  124.16   28.75  123.45   31.94  122.44   33.26  121.93
   35.99  121.83   36.42  121.83   45.68  121.15   46.13  120.95   47.37   120.4
   48.18  119.94   48.56  119.94   49.39  120.18   50.47 120.363   52.28  120.67
   55.26  120.97   63.36  121.05   68.29  121.03   69.88  121.06    72.6  121.87
   73.85  122.01   79.14  123.59   82.63  123.89   89.09  128.66   89.95  129.26
   93.31  131.55    94.8  132.47   96.06  132.59   97.34  132.59   99.85  132.64
#Mann= 3 , 0 , 0
       0     .06       0   47.37     .04       0   50.47     .06       0
Bank Sta=47.37,50.47
XS Rating Curve= 0 ,0
Exp/Cntr=0.3,0.1

Type RM Length L Ch R = 1 ,2528.27 ,10.94,10.08,9.19
XS GIS Cut Line= 4
343360.7821044925422798.12591553 343356.624877935422769.76672363
343334.6744995125422747.21173096343324.4912719735422718.76751709
#Sta/Elev= 22
       0   126.9   22.93  124.15   23.87  123.74   28.66  122.09   33.01  121.14
   33.27  121.04   36.36 119.532   37.04   119.1   37.82  119.32   39.38  119.57
   40.82  119.73   47.55  120.49   55.51  121.93   60.14  122.26   66.81  123.07
   69.32  124.07   75.21  128.28   80.33  131.89   82.78  132.12   85.26  132.14
   89.71  132.45   90.35  132.51
#Mann= 3 , 0 , 0
       0     .06       0   36.36     .04       0   39.38     .06       0
Bank Sta=36.36,39.38
XS Rating Curve= 0 ,0
Exp/Cntr=0.3,0.1

Type RM Length L Ch R = 1 ,2518.19 ,13.16,22.04,26.43
XS GIS Cut Line= 4
343372.1911010745422790.27990723343365.000915527 5422762.0916748
343346.7489013675422747.16851807343339.0054931645422724.64550781
#Sta/Elev= 20
       0  126.52    1.44  126.35   15.31  124.65   20.91  122.21   24.54  121.02
   27.35  121.21   29.09  120.96   38.97  119.13   39.43  119.05   40.42  118.62
   41.97  119.13   46.18  119.83   47.03  119.97   47.77  120.13   52.67     121
   60.03  122.74   66.17  124.25   68.51  125.94   75.19  131.34   76.48  131.43
#Mann= 3 , 0 , 0
       0     .06       0   38.97     .04       0   41.97     .06       0
Bank Sta=38.97,41.97
XS Rating Curve= 0 ,0
Exp/Cntr=0.3,0.1

Type RM Length L Ch R = 1 ,2496.15 ,11.19,17.78,21.52
XS GIS Cut Line= 4
343380.4874877935422782.81829834343372.8823242195422755.04449463
343373.7120971685422744.54309082 343359.884704595422703.36608887
#Sta/Elev= 22
       0  126.04    3.72   125.6    7.65  125.12    9.28  124.41   21.73  120.33
   22.28  120.37   22.96  120.29    28.8  120.26   32.13  120.23   37.14  119.31
   39.33  119.24   42.76  118.98   45.54  118.53    45.8  118.83   49.39  119.64
   52.99  122.19   55.55  123.74    60.9  127.98   64.72  130.44   64.83  130.45
    68.4  131.27   82.77   132.1
#Mann= 3 , 0 , 0
       0     .06       0   42.76     .04       0    45.8     .06       0
Bank Sta=42.76,45.8
XS Rating Curve= 0 ,0
Exp/Cntr=0.3,0.1

Type RM Length L Ch R = 1 ,2478.37 ,31.88,27.75,24.25
XS GIS Cut Line= 4
343387.2590942385422783.03112793343381.5856933595422753.71472168
343396.6262817385422731.35772705343383.856323242 5422699.4822998
#Sta/Elev= 25
       0  126.41    4.49  125.88    6.57  125.59    9.85  125.11   10.88  124.69
   21.14  121.35   29.86  120.53   32.39  120.39    38.1  118.98   40.69  118.54
   43.16  117.97   43.69  118.37   44.72  118.99    52.9  123.76   54.68  124.04
   56.81  124.32   65.19  125.48   65.91  125.74   67.85  127.19    69.9  128.69
   70.44  129.02   73.19   130.1   75.33  131.54   89.83  131.53   91.14  131.62
#Mann= 3 , 0 , 0
       0     .06       0   40.69     .04       0   43.69     .06       0
Bank Sta=40.69,43.69
XS Rating Curve= 0 ,0
Exp/Cntr=0.3,0.1

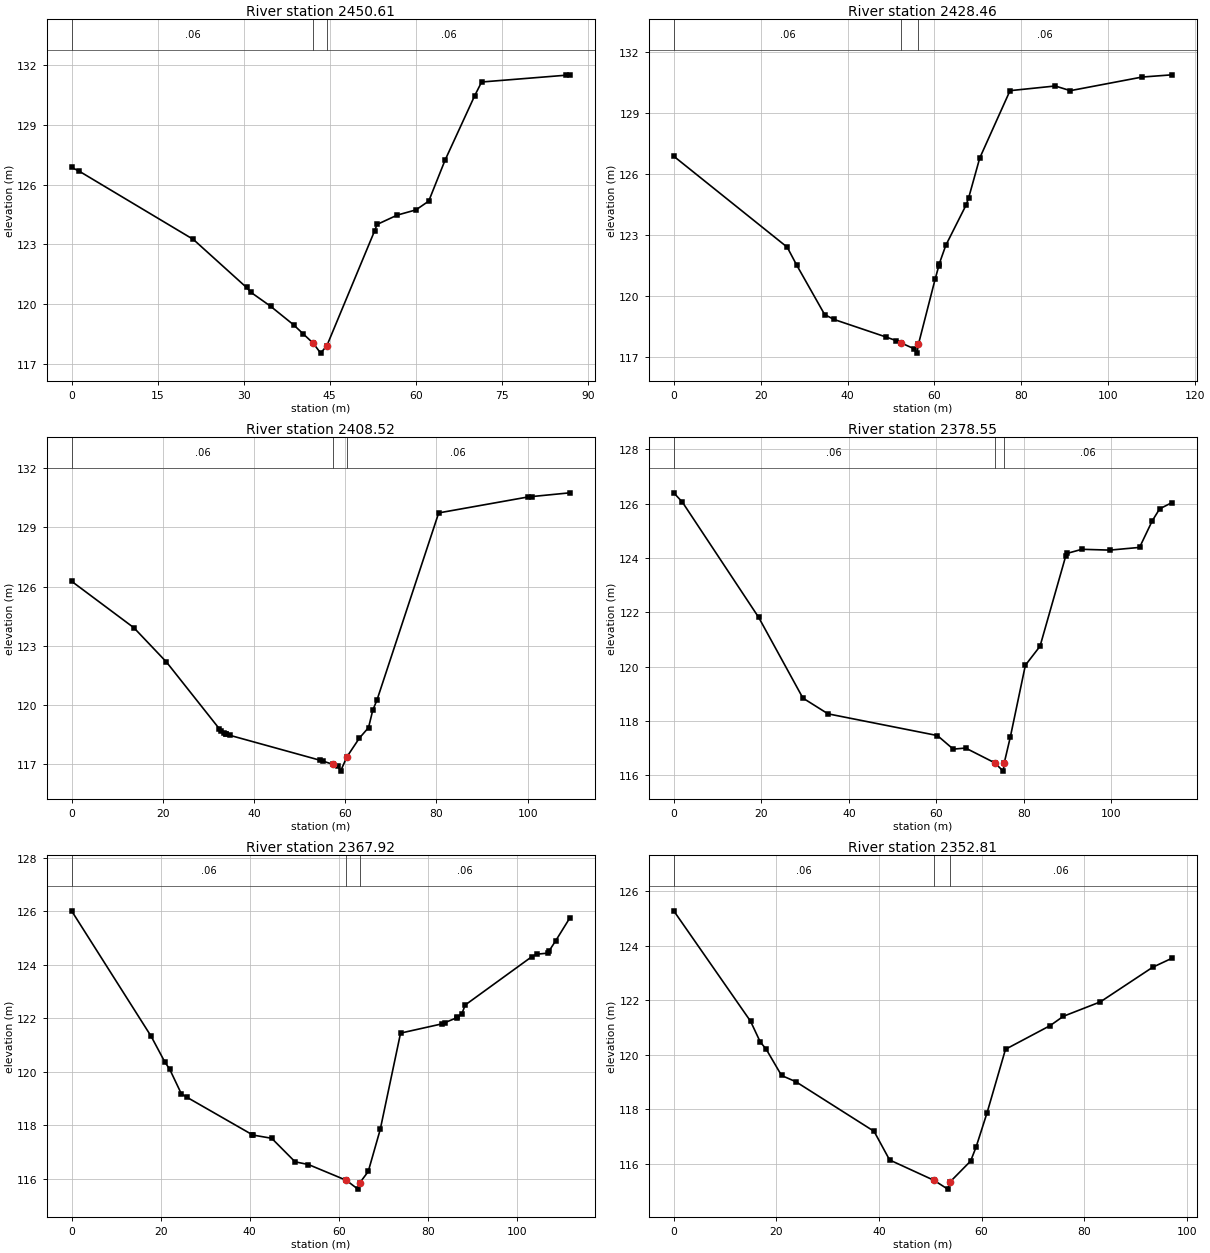
Type RM Length L Ch R = 1 ,2450.61 ,24.03,22.16,22.39
XS GIS Cut Line= 3
343410.1376953135422780.31707764343415.9451293955422742.04187012
343400.4584960945422696.44329834
#Sta/Elev= 21
       0  126.86    1.27  126.68   21.23  123.25   30.51  120.84   31.31  120.59
    34.7   119.9   38.71  118.97   40.41  118.51   42.15 118.043   43.43  117.55
   44.53  117.93   52.83  123.67   53.27     124    56.8  124.47   60.05  124.73
   62.28  125.17   65.14  127.23   70.29  130.45    71.5  131.14   86.19  131.48
   86.87   131.5
#Mann= 3 , 0 , 0
       0     .06       0   42.15     .04       0   44.53     .06       0
Bank Sta=42.15,44.53
XS Rating Curve= 0 ,0
Exp/Cntr=0.3,0.1

Type RM Length L Ch R = 1 ,2428.46 ,12.39,19.94,19.98
XS GIS Cut Line= 4
343427.7509155275422782.86132813 343439.704895025422747.98748779
343427.5335083015422698.53912354343437.6638793955422673.66210938
#Sta/Elev= 23
       0  126.89   26.11  122.41   28.31  121.52   34.73  119.09   36.87  118.85
   48.78  117.99   51.12  117.81   52.36  117.69   55.36   117.4   55.97  117.19
   56.31 117.624   60.14  120.82   60.99  121.48   61.11  121.59   62.61   122.5
   67.29  124.49   67.87  124.84   70.42   126.8   77.39  130.12   87.79  130.35
   91.27  130.12  107.77  130.79  114.65   130.9
#Mann= 3 , 0 , 0
       0     .06       0   52.36     .04       0   56.31     .06       0
Bank Sta=52.36,56.31
XS Rating Curve= 0 ,0
Exp/Cntr=0.3,0.1

Type RM Length L Ch R = 1 ,2408.52 ,14.15,29.97,35.14
XS GIS Cut Line= 5
343435.7180786135422780.73168945343445.950317383 5422747.4309082
343455.9058837895422730.43487549343444.8441162115422685.38909912
343444.1527099615422677.09832764
#Sta/Elev= 23
       0  126.27   13.66  123.91    20.8  122.17    32.4  118.78   32.73  118.66
   33.38  118.57   33.77  118.51   33.86  118.51   34.84  118.44   54.53  117.18
   55.11  117.14   57.35  116.97   58.36   116.9   58.99  116.63   60.36  117.35
   63.12  118.31   65.12  118.84   66.03  119.71      67  120.26    80.5  129.74
   100.1  130.55  100.92  130.57  109.24  130.76
#Mann= 3 , 0 , 0
       0     .06       0   57.35     .04       0   60.36     .06       0
Bank Sta=57.35,60.36
XS Rating Curve= 0 ,0
Exp/Cntr=0.3,0.1

Type RM Length L Ch R = 1 ,2378.55 ,12.02,10.64,11.18
XS GIS Cut Line= 4
343442.339294434 5422782.8861084343453.0733032235422748.05151367
343501.4827270515422714.32147217343507.7213134775422697.05688477
#Sta/Elev= 22
       0   126.4    1.96  126.06   19.41  121.81   29.51  118.84   35.24  118.26
   60.24  117.46   63.85  116.96   66.68     117   73.28  116.46   75.28  116.15
   75.52 116.464    76.9  117.41   80.33  120.05   83.68  120.75   89.53  124.06
   89.88  124.17   93.24  124.32   99.65  124.29  106.42  124.39  109.32  125.37
  111.01  125.81  113.81  126.04
#Mann= 3 , 0 , 0
       0     .06       0   73.28     .04       0   75.52     .06       0
Bank Sta=73.28,75.52
XS Rating Curve= 0 ,0
Exp/Cntr=0.3,0.1

Type RM Length L Ch R = 1 ,2367.92 ,11.31,15.11,15.78
XS GIS Cut Line= 5
343446.8123168955422784.07751465343460.777709961 5422762.2454834
343478.7532958985422741.79528809   343505.578125 5422727.0100708
343515.3955078135422700.75628662
#Sta/Elev= 29
       0  126.01   17.86  121.32   20.93  120.36   22.02  120.09   24.64  119.17
   25.92  119.04   40.59  117.64   40.72  117.63   44.91  117.51   50.16  116.63
   53.14  116.53   61.66  115.94   64.25  115.61   64.66  115.84   66.58  116.27
   69.27  117.84   73.83  121.44   83.24  121.79   83.77  121.83    86.5  122.02
   86.55  122.03   87.58  122.16   88.33  122.49  103.32   124.3  104.43  124.39
  106.94  124.43   107.2  124.52  108.68   124.9   111.8  125.74
#Mann= 3 , 0 , 0
       0     .06       0   61.66     .04       0   64.66     .06       0
Bank Sta=61.66,64.66
XS Rating Curve= 0 ,0
Exp/Cntr=0.3,0.1

Type RM Length L Ch R = 1 ,2352.81 ,31.17,24.17,17.57
XS GIS Cut Line= 6
343453.8640747075422786.42651367343474.466674805 5422762.9362793
 343482.624877935422754.50750732343502.5360717775422747.46051025
343504.6102905275422743.45330811343516.6400756845422717.61407471
#Sta/Elev= 20
       0  125.28   14.97  121.23   16.86  120.47   18.03   120.2   21.01  119.24
   23.81  119.01   39.05  117.19   42.08  116.14   50.76  115.39   53.41  115.07
   53.79  115.32   57.87   116.1   58.93  116.61   61.09  117.88   64.67   120.2
   73.38  121.07   75.94  121.41   83.16  121.94   93.36  123.21   97.11  123.54
#Mann= 3 , 0 , 0
       0     .06       0   50.76     .04       0   53.79     .06       0
Bank Sta=50.76,53.79
XS Rating Curve= 0 ,0
Exp/Cntr=0.3,0.1

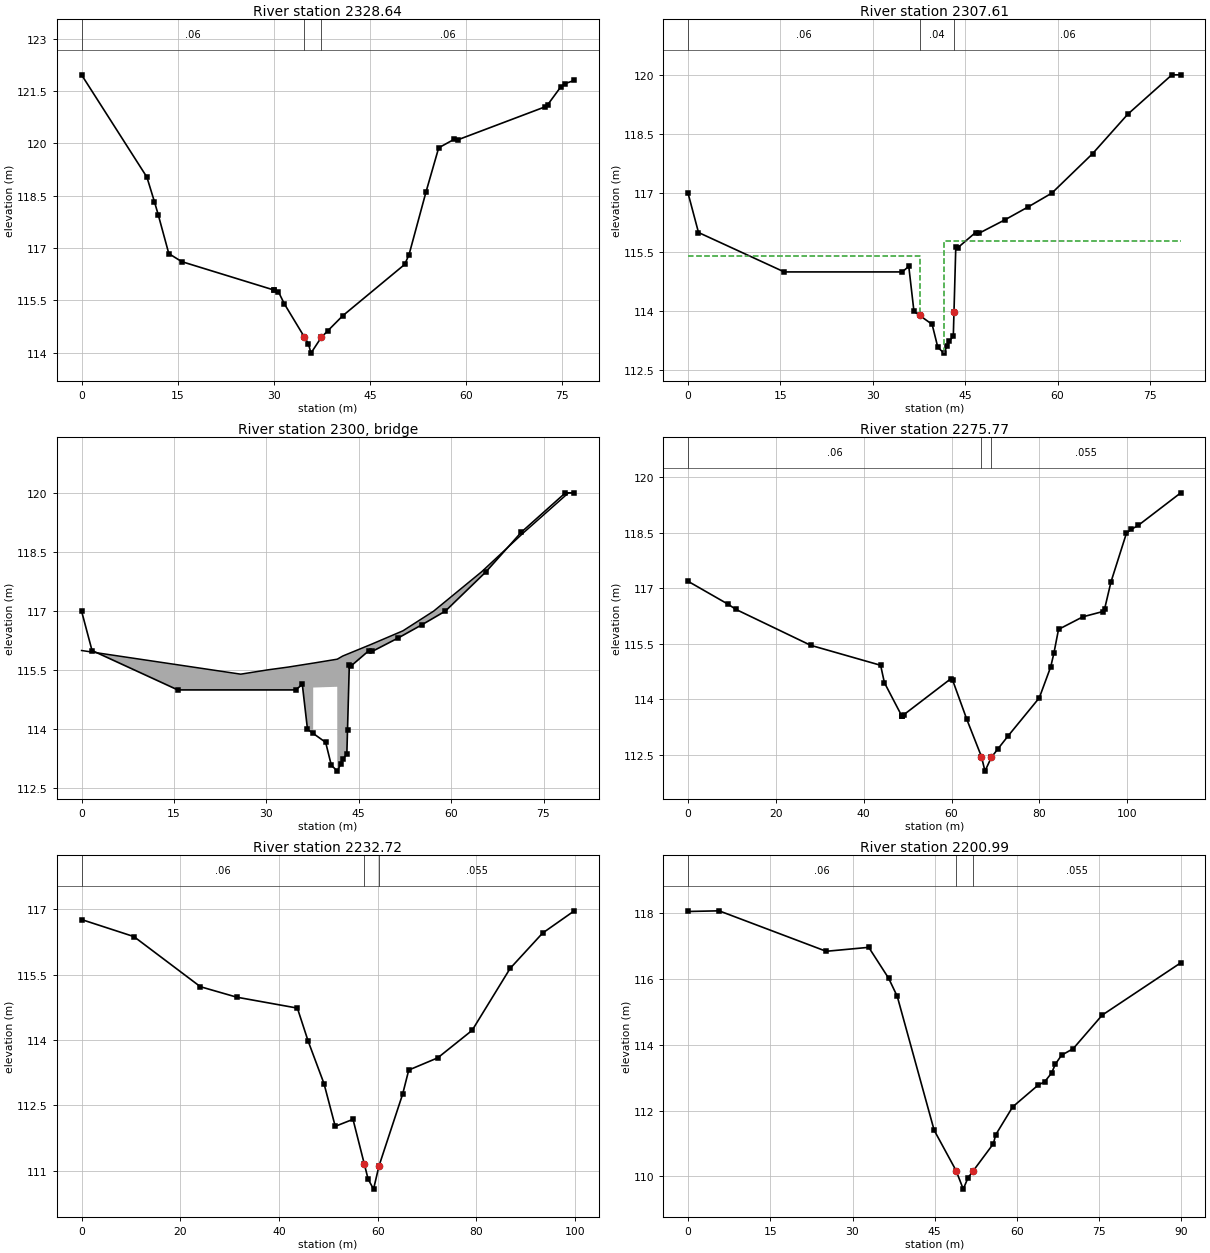
Type RM Length L Ch R = 1 ,2328.64 ,27.02,21.04,20.02
Node Photo=..\..\..\..\Corner Brook\Windshield Survey\CB photos\P1000725.JPG
XS GIS Cut Line= 3
343477.4550781255422795.50372314343492.2993164065422790.56732178
343520.741088867 5422736.2902832
#Sta/Elev= 27
       0  121.96    10.2  119.03   11.37  118.33   11.96  117.96   13.62  116.84
   15.64  116.61   29.98   115.8   30.07  115.79   30.72  115.75   31.66   115.4
   34.77 114.455   35.41  114.26   35.81  113.99   37.42  114.44   38.44  114.63
   40.77  115.06   50.44  116.53   51.12  116.81   53.76   118.6   55.75  119.87
   58.13  120.11   58.75   120.1   72.31  121.04   72.79  121.11   74.83  121.62
    75.5  121.71   76.92   121.8
#Mann= 3 , 0 , 0
       0     .06       0   34.77     .04       0   37.42     .06       0
Bank Sta=34.77,37.42
XS Rating Curve= 0 ,0
Exp/Cntr=0.3,0.1

Type RM Length L Ch R = 1 ,2307.61 ,11.95,11.77,11.75
XS GIS Cut Line= 2
343515.0319213875422822.16131592343525.157897949 5422742.8046875
#Sta/Elev= 25
       0     117     1.7     116   15.62     115   34.77     115   35.84  115.14
   36.68     114    37.6 113.897   39.63  113.67   40.55  113.09   41.53  112.94
   42.07  113.12   42.44  113.25   43.07  113.37   43.18 113.989   43.47  115.62
   43.77  115.61   46.68     116   47.23  115.98   51.43  116.32   55.23  116.65
   59.07     117   65.68     118   71.39     119   78.56     120      80     120
#Mann= 3 , 0 , 0
       0     .06       0    37.6     .04       0   43.18     .06       0
#XS Ineff= 2 , 0
       0    37.6   115.4   41.52       0  115.78
Permanent Ineff=
       F       F
Bank Sta=37.6,43.18
XS Rating Curve= 0 ,0
Exp/Cntr=0.5,0.3

Type RM Length L Ch R = 3 ,2300    ,,,
Node Photo=..\..\..\..\Corner Brook\Windshield Survey\CB photos\P1000720.JPG
BEGIN DESCRIPTION:
Walbournes Road (Structure #2121B)
END DESCRIPTION:
Bridge Culvert--1,0,-1,-1, 0
Deck Dist Width WeirC Skew NumUp NumDn MinLoCord MaxHiCord MaxSubmerge Is_Ogee
3.7,6.5,1.67,0, 16, 15, 115.4, , 0.98, 0, 0,0,,
       0   25.84   30.27   33.56    37.6   37.61   41.51   41.52    42.4   47.08
   52.18   57.17   64.97   71.84   79.06      80
     116   115.4  115.51  115.58  115.68  115.68  115.78  115.78  115.86  116.16
   116.5     117     118     119     120     120
                                     111  115.06  115.08     111
                                                
       0    26.2    30.6   37.53   38.31   38.32   42.42   42.43    42.5   46.64
   50.32   57.84   65.47   72.92      80
     116  115.34  115.42  115.63  115.64  115.64  115.79  115.79   115.8  115.98
  116.23     117     118     119     120
                                     111  114.97  114.93     111
                                        
BR Coef=-1 , 0 , 0 ,, 0 ,,,0.8,-1,,0,
WSPro=,,,, 1 ,,,, 0 ,,,, 0 ,,,,-1 ,-1 ,-1 , 0 , 0 , 0 , 0 , 0
BC Design=,, 0 ,, 0 ,,,,,,
BC Use User HTab Curves=0
BC User HTab FreeFlow(D)= 0

Type RM Length L Ch R = 1 ,2275.77 ,39.4,43.04,52.78
XS GIS Cut Line= 2
343530.2150878915422857.03369141343563.4030761725422749.83911133
#Sta/Elev= 30
       0  117.19    9.12  116.57   10.91  116.43   27.93  115.46   43.86  114.92
   44.72  114.45   48.68  113.55   48.69  113.55    48.7  113.55   49.09  113.58
   59.78  114.55   60.28  114.51   63.48  113.46   66.83 112.449   67.62  112.06
   69.08 112.433   70.63  112.67   72.95  113.02   79.99  114.04    82.6  114.88
   83.32  115.25   84.37  115.89   89.92  116.23   94.39  116.37   94.84  116.43
   96.31  117.17   99.84  118.49   100.9  118.59  102.52   118.7  112.21  119.58
#Mann= 3 , 0 , 0
       0     .06       0   66.83     .04       0   69.08    .055       0
Bank Sta=66.83,69.08
XS Rating Curve= 0 ,0
Exp/Cntr=0.3,0.1

Type RM Length L Ch R = 1 ,2232.72 ,38.44,31.74,21.2
XS GIS Cut Line= 3
343545.7821044925422849.65148926343597.9434814455422799.78308105
343605.2807006845422773.11547852
#Sta/Elev= 20
       0  116.76   10.59  116.37   24.08  115.22   31.45  114.98   43.72  114.73
   45.91  113.97   49.11     113   51.39  112.02   54.99  112.18    57.3 111.146
   58.05  110.81   59.15  110.58   60.25  111.11   65.05  112.76   66.28  113.31
   72.16  113.59   79.12  114.22   86.82  115.64    93.4  116.45   99.82  116.96
#Mann= 3 , 0 , 0
       0     .06       0    57.3     .04       0   60.25    .055       0
Bank Sta=57.3,60.25
XS Rating Curve= 0 ,0
Exp/Cntr=0.3,0.1

Type RM Length L Ch R = 1 ,2200.99 ,22.72,27.78,32.31
XS GIS Cut Line= 6
343627.4519042975422859.60089111343621.3679199225422839.97967529
343618.6024780275422835.55810547 343620.261718755422824.91827393
343608.5084838875422800.18450928343620.3999023445422777.10888672
#Sta/Elev= 22
       0  118.05    5.67  118.07    25.2  116.84   32.96  116.96   36.59  116.02
   38.16  115.47   44.89   111.4   48.88 110.176    50.2  109.61   51.05  109.95
   51.98 110.158   55.69  110.99   56.11  111.26   59.21  112.11   63.91  112.78
   65.03  112.87   66.31  113.14      67  113.41   68.12  113.68   70.25  113.88
   75.54   114.9   89.87  116.49
#Mann= 3 , 0 , 0
       0     .06       0   48.88     .04       0   51.98    .055       0
Bank Sta=48.88,51.98
XS Rating Curve= 0 ,0
Exp/Cntr=0.3,0.1

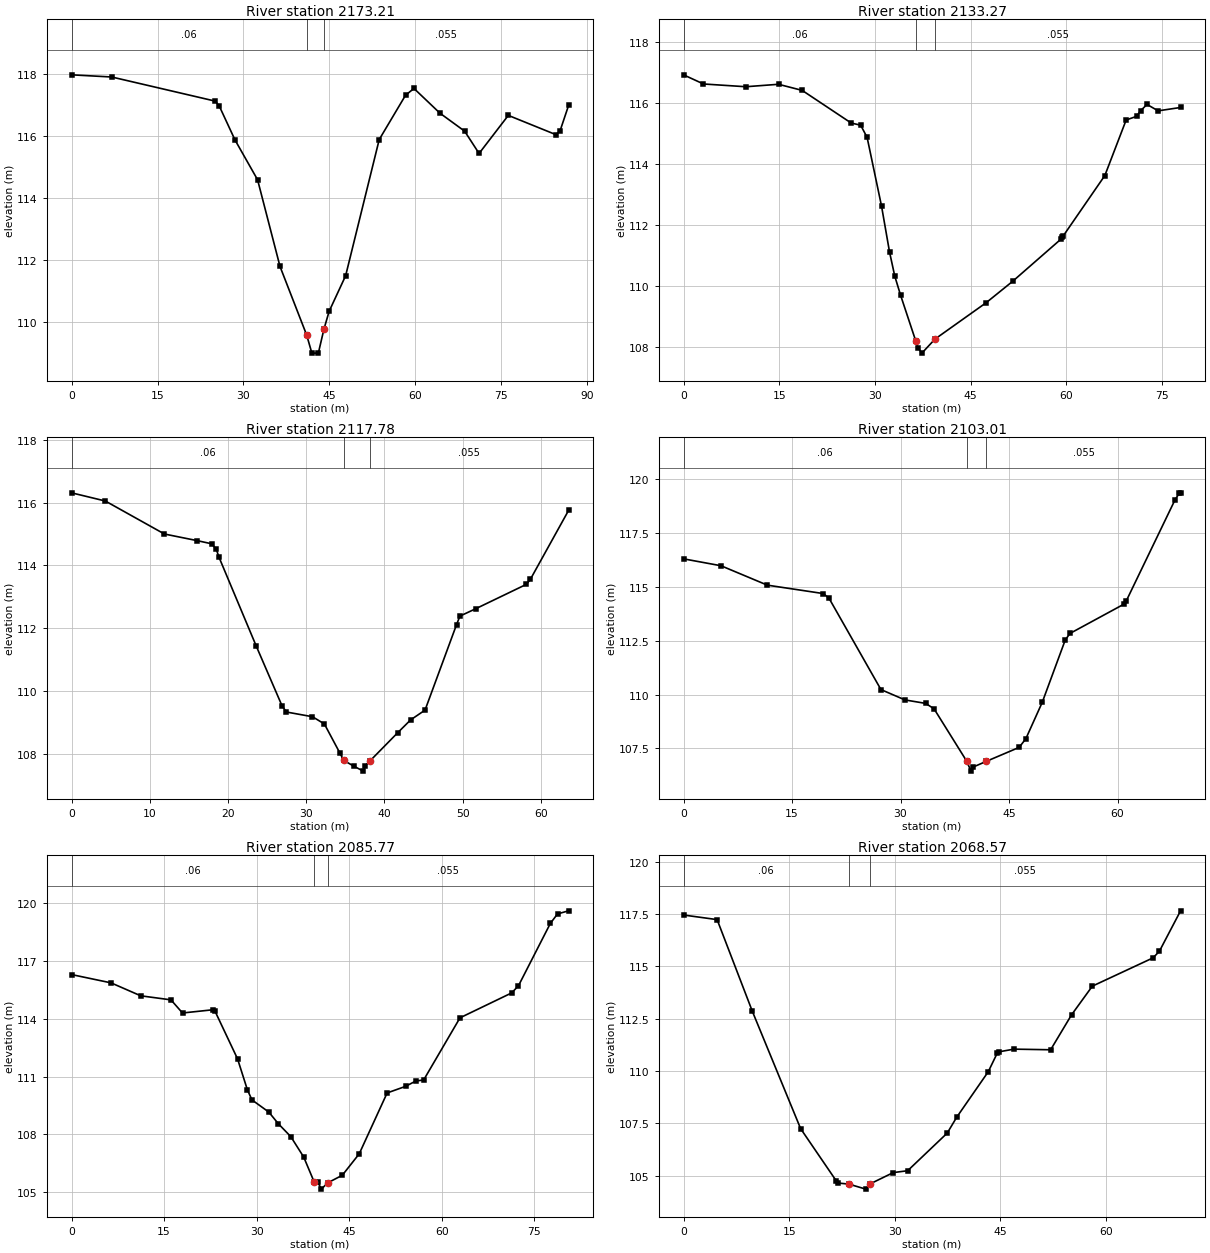
Type RM Length L Ch R = 1 ,2173.21 ,42.81,39.94,36.09
XS GIS Cut Line= 3
343629.7476806645422860.61590576343633.5178833015422832.35351563
343659.5560913095422780.30328369
#Sta/Elev= 23
       0  117.97    7.01   117.9   25.08  117.12   25.78  116.96   28.51  115.87
   32.46  114.58   36.37  111.78   41.03  109.56   41.93  108.98   43.06  108.98
   44.03  109.75   44.94  110.33   47.82  111.48   53.68  115.88   58.27  117.31
   59.74  117.53   64.28  116.73   68.58  116.15    71.1  115.43    76.2  116.66
   84.47  116.04   85.21  116.15   86.71  116.98
#Mann= 3 , 0 , 0
       0     .06       0   41.03     .04       0   44.03    .055       0
Bank Sta=41.03,44.03
XS Rating Curve= 0 ,0
Exp/Cntr=0.3,0.1

Type RM Length L Ch R = 1 ,2133.27 ,16.07,15.48,14.82
XS GIS Cut Line= 3
343662.3342895515422857.67529297343680.6378784185422838.80108643
343664.5114746095422789.75189209
#Sta/Elev= 28
       0  116.91    3.13  116.61    9.77  116.52   14.89   116.6    18.6   116.4
   26.29  115.33   27.77  115.26   28.78  114.86   31.04  112.61    32.3   111.1
   33.12  110.31   34.04  109.68   36.42  108.18   36.77  107.96   37.37  107.79
   39.42  108.25   47.43  109.44   51.58  110.14   59.14  111.52   59.32   111.6
   59.49  111.62   66.05  113.61   69.39  115.43   71.03  115.55   71.64  115.73
   72.66  115.94    74.4  115.73   77.92  115.84
#Mann= 3 , 0 , 0
       0     .06       0   36.42     .04       0   39.42    .055       0
Bank Sta=36.42,39.42
XS Rating Curve= 0 ,0
Exp/Cntr=0.3,0.1

Type RM Length L Ch R = 1 ,2117.78 ,8.25,14.77,20.57
XS GIS Cut Line= 5
343676.9987182625422849.66088867343689.0283203135422839.02111816
343692.9000854495422824.78887939343686.9542846685422813.73468018
343687.7838745125422793.56072998
#Sta/Elev= 27
       0  116.31    4.32  116.05   11.88     115   16.06  114.79   17.91  114.69
    18.5  114.52   18.86  114.26   23.63  111.43   26.91  109.54   27.47  109.34
   30.81  109.19   32.33  108.96   34.28  108.05   34.81   107.8   36.08  107.62
    37.3  107.46   37.55  107.63   38.17 107.787    41.7  108.68   43.36  109.09
    45.2   109.4   49.23  112.12   49.66  112.39   51.73  112.63   58.16   113.4
   58.67  113.56   63.55  115.75
#Mann= 3 , 0 , 0
       0     .06       0   34.81     .04       0   38.17    .055       0
Bank Sta=34.81,38.17
XS Rating Curve= 0 ,0
Exp/Cntr=0.3,0.1

Type RM Length L Ch R = 1 ,2103.01 ,16.08,17.24,19.84
XS GIS Cut Line= 5
343677.275085449 5422850.4899292343689.8580932625422841.09387207
343697.3247070315422824.51251221343704.7915039065422817.18908691
343717.3743286135422796.32427979
#Sta/Elev= 23
       0  116.29    5.18  115.97   11.59  115.07   19.33  114.68   20.12  114.46
   27.29  110.23   30.62  109.75   33.47  109.59   34.63  109.34   39.13  106.92
   39.74  106.45   40.04  106.64   41.87 106.905   46.39  107.55   47.32  107.95
   49.59  109.64   52.76  112.52   53.41  112.83   60.83  114.18   61.19  114.33
   67.95  119.03   68.55  119.34   68.71  119.35
#Mann= 3 , 0 , 0
       0     .06       0   39.13     .04       0   41.87    .055       0
Bank Sta=39.13,41.87
XS Rating Curve= 0 ,0
Exp/Cntr=0.3,0.1

Type RM Length L Ch R = 1 ,2085.77 ,20.31,17.19,10.69
XS GIS Cut Line= 3
343677.549072266 5422851.2479248 343727.107482915422825.57110596
343740.1682739265422804.53967285
#Sta/Elev= 30
       0  116.28    6.41  115.85   11.22  115.18   16.12  114.97   17.99  114.29
      23  114.46   23.25  114.39   26.92  111.91   28.51  110.31   29.25  109.79
   31.98  109.16   33.54  108.55   35.54  107.89   37.64  106.83   39.31  105.56
    39.9  105.55    40.5  105.17    41.5  105.49    43.9  105.89   46.64     107
   51.16  110.15   54.14  110.49   55.82  110.77   57.08  110.82   62.97  114.04
   71.35  115.33   72.45   115.7   77.62  118.93   78.78  119.42   80.57  119.58
#Mann= 3 , 0 , 0
       0     .06       0   39.31     .04       0    41.5    .055       0
Bank Sta=39.31,41.5
XS Rating Curve= 0 ,0
Exp/Cntr=0.3,0.1

Type RM Length L Ch R = 1 ,2068.57 ,10.71,8.69,4.44
XS GIS Cut Line= 5
343712.1630859385422872.91271973343713.9606933595422854.94952393
343719.353271484  5422843.480896343726.8198852545422830.76849365
343738.9880981455422808.79827881
#Sta/Elev= 23
       0  117.46    4.77  117.24    9.77  112.86   16.63  107.25   21.72  104.74
   21.98  104.65   23.48   104.6   25.89  104.36   26.49  104.61   29.78  105.15
   31.83  105.24   37.45  107.04    38.8   107.8   43.27  109.97   44.55  110.86
   44.76  110.92   46.92  111.05   52.13  111.02    55.1  112.69   58.05  114.06
   66.66  115.41   67.56  115.72   70.58  117.66
#Mann= 3 , 0 , 0
       0     .06       0   23.48     .04       0   26.49    .055       0
Bank Sta=23.48,26.49
XS Rating Curve= 0 ,0
Exp/Cntr=0.3,0.1

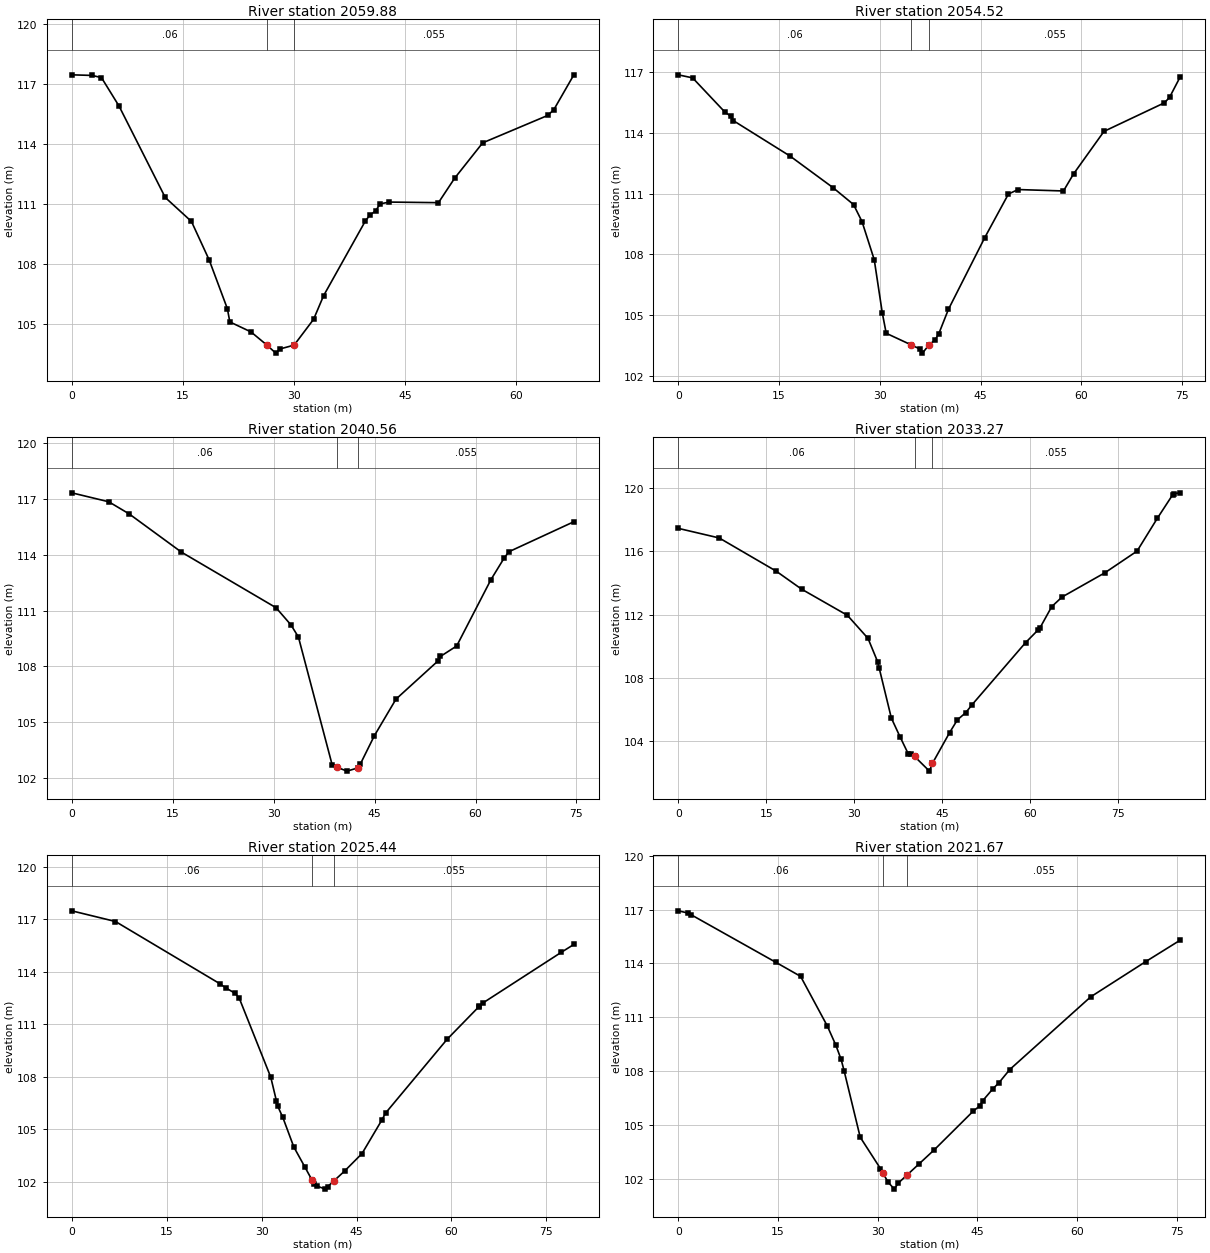
Type RM Length L Ch R = 1 ,2059.88 ,5.98,5.37,4.2
XS GIS Cut Line= 5
343720.7360839845422872.91271973343724.6077270515422859.23309326
343725.1607055665422842.51348877343726.8198852545422832.15032959
 343739.541076665422809.07452393
#Sta/Elev= 27
       0  117.47    2.76  117.44    4.01  117.33    6.38  115.91   12.62  111.34
   16.16  110.14   18.55  108.22   21.01  105.78   21.34  105.12    24.2  104.62
   26.36 103.957   27.54  103.56   28.13  103.77   30.02  103.96   32.65  105.25
      34  106.43   39.65  110.17   40.24  110.45   41.05  110.68   41.63  111.02
   42.89  111.11   49.51  111.08   51.69   112.3   55.48  114.07   64.26  115.44
   65.09  115.73   67.79  117.47
#Mann= 3 , 0 , 0
       0     .06       0   26.36     .04       0   30.02    .055       0
Bank Sta=26.36,30.02
XS Rating Curve= 0 ,0
Exp/Cntr=0.3,0.1

Type RM Length L Ch R = 1 ,2054.52 ,12.81,13.96,14.46
XS GIS Cut Line= 5
343730.9680786135422881.06512451343733.5952758795422864.62188721
343731.1065063485422855.08770752343728.3408813485422830.35388184
343739.8176879885422810.04187012
#Sta/Elev= 28
       0  116.86    2.14  116.71    6.95  115.02    7.82  114.82     8.2   114.6
   16.65  112.85   23.01   111.3   26.09  110.46   27.35  109.62   29.17  107.74
   30.37  105.11   30.95  104.11   34.59 103.549   36.05  103.32   36.34  103.13
   37.37 103.554   38.22  103.78   38.78  104.09   40.21  105.29   45.62  108.83
   49.14  110.98   50.58   111.2   57.33  111.13   58.83  111.97   63.36  114.07
   72.36  115.48   73.12  115.75   74.72  116.77
#Mann= 3 , 0 , 0
       0     .06       0   34.59     .04       0   37.37    .055       0
Bank Sta=34.59,37.37
XS Rating Curve= 0 ,0
Exp/Cntr=0.3,0.1

Type RM Length L Ch R = 1 ,2040.56 ,7.27,7.29,7.43
XS GIS Cut Line= 4
343738.9880981455422885.90148926343741.4769287115422865.58929443
343743.9658813485422840.30267334343743.8275146485422811.56188965
#Sta/Elev= 21
       0  117.31     5.5  116.83    8.53  116.18    16.3  114.13   30.36  111.15
   32.57  110.23   33.68  109.58    38.7  102.72   39.47  102.59    40.9  102.39
   42.48  102.56   42.87  102.76   44.97  104.29   48.18  106.25   54.46  108.31
   54.79  108.54    57.2   109.1   62.28  112.65   64.23   113.8   64.95  114.15
   74.61  115.76
#Mann= 3 , 0 , 0
       0     .06       0   39.47     .04       0   42.48    .055       0
Bank Sta=39.47,42.48
XS Rating Curve= 0 ,0
Exp/Cntr=0.3,0.1

Type RM Length L Ch R = 1 ,2033.27 ,7.45,7.82,8.18
XS GIS Cut Line= 3
343745.7858886725422887.38110352343752.7958984385422828.58770752
343747.0051269535422802.84667969
#Sta/Elev= 30
       0  117.46    6.99  116.85   16.69  114.75   21.02  113.61   28.84  111.95
   32.35  110.49   33.98  109.02   34.27  108.59   36.33  105.44   37.79  104.27
   39.22  103.17    39.7  103.19   40.29  103.01   42.82  102.08   43.33  102.57
   46.26  104.52   47.59  105.33      49  105.78   50.12   106.3   59.21  110.22
   61.31  111.01   61.66  111.15   63.67   112.5   65.43  113.11   72.71  114.64
   78.22  116.02   81.66  118.09   84.31   119.6   84.51  119.66   85.59  119.71
#Mann= 3 , 0 , 0
       0     .06       0   40.29     .04       0   43.33    .055       0
Bank Sta=40.29,43.33
XS Rating Curve= 0 ,0
Exp/Cntr=0.3,0.1

Type RM Length L Ch R = 1 ,2025.44 ,3.43,3.77,4.29
XS GIS Cut Line= 4
343752.2620849615422887.28308105343757.5164794925422850.80432129
343760.0054931645422838.92108154343753.7830810555422809.21270752
#Sta/Elev= 28
       0  117.47    6.91  116.86   23.44   113.3    24.3  113.08   25.81  112.76
   26.46  112.49   31.45  107.97   32.35  106.61   32.52  106.34   33.36  105.67
   35.09  103.99   36.86  102.83   37.96 102.102   38.31  101.87   38.78  101.75
    40.1  101.58   40.47  101.73   41.47 102.063   43.11  102.61   45.87  103.61
      49  105.52   49.61  105.93   59.33  110.14    64.3  111.98   64.37  112.01
   64.94   112.2   77.36   115.1   79.35  115.55
#Mann= 3 , 0 , 0
       0     .06       0   37.96     .04       0   41.47    .055       0
Bank Sta=37.96,41.47
XS Rating Curve= 0 ,0
Exp/Cntr=0.3,0.1

Type RM Length L Ch R = 1 ,2021.67 ,6.52,7.14,7.19
XS GIS Cut Line= 4
 343757.101684575422881.61791992343760.8350830085422851.08068848
343764.9832763675422838.09191895343757.6549072275422807.83087158
#Sta/Elev= 27
       0  116.93    1.45  116.81     1.9  116.72   14.65  114.07   18.41  113.28
   22.41  110.53   23.71  109.45   24.51  108.65   24.95  108.03   27.38  104.32
   30.43  102.57   30.76  102.35   31.57  101.82   32.51  101.43   33.09  101.76
   34.36 102.194   36.19  102.82   38.55  103.63    44.4  105.78   45.39  106.07
    45.8  106.35   47.37  107.03   48.24  107.35   49.88  108.09   62.06  112.14
   70.33   114.1   75.54   115.3
#Mann= 3 , 0 , 0
       0     .06       0   30.76     .04       0   34.36    .055       0
Bank Sta=30.76,34.36
XS Rating Curve= 0 ,0
Exp/Cntr=0.3,0.1

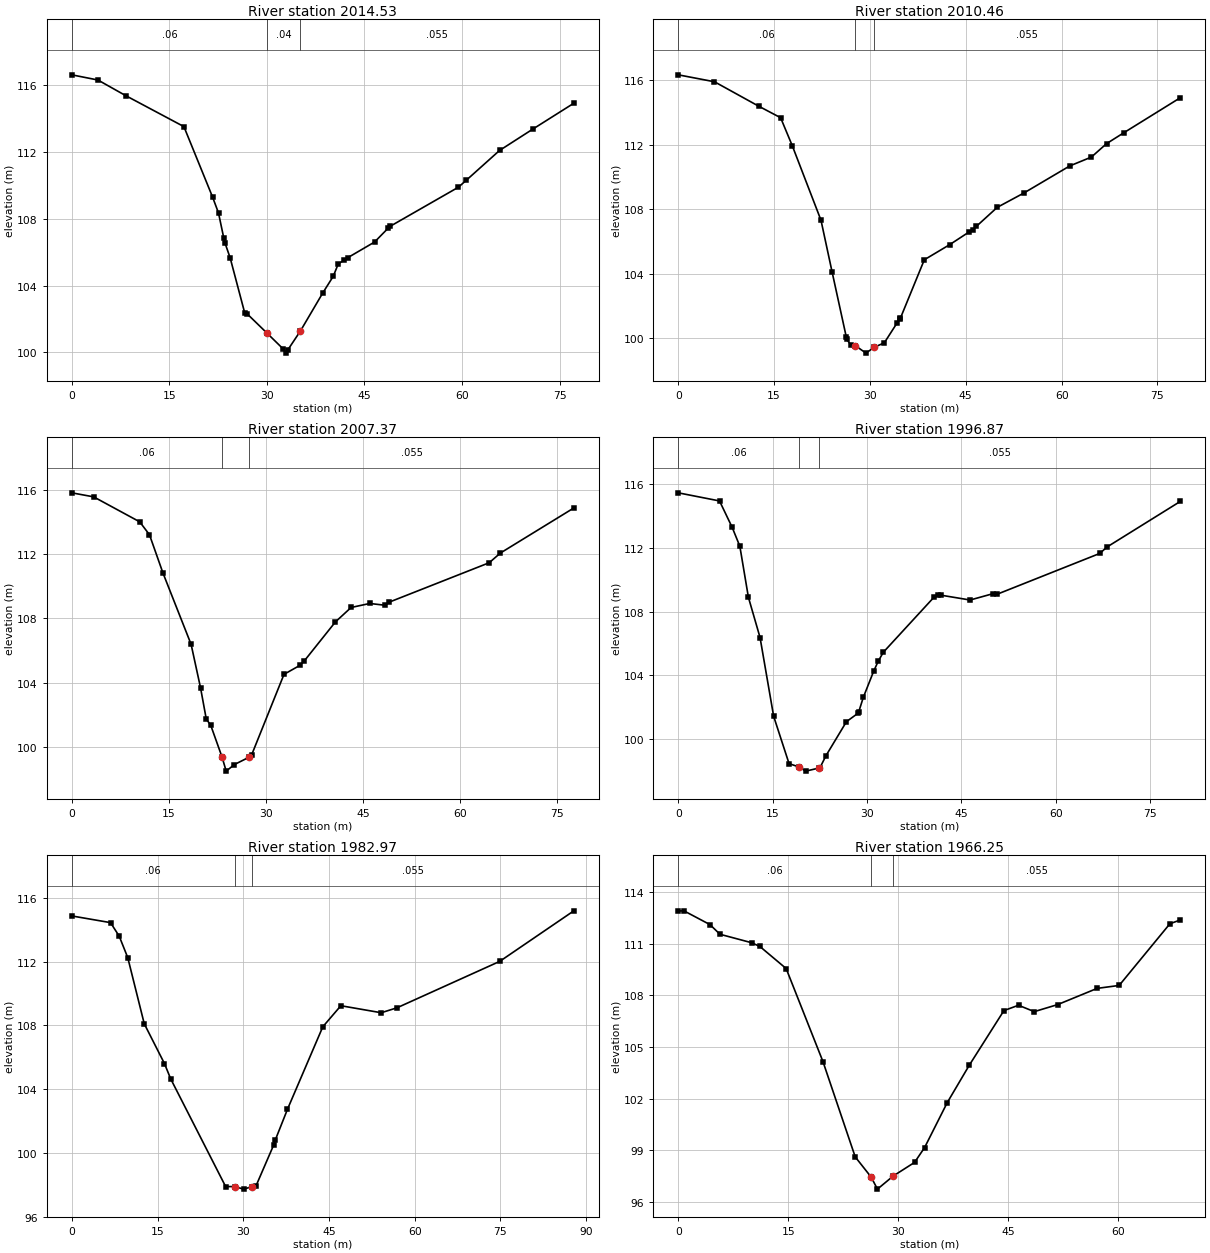
Type RM Length L Ch R = 1 ,2014.53 ,4.45,4.08,4.12
XS GIS Cut Line= 6
343763.4622802735422881.89428711343766.0894775395422855.08770752
343769.8228759775422847.76428223 343771.343872075422834.36108398
 343767.333923345422823.03051758 343759.175903325422808.66009521
#Sta/Elev= 29
       0  116.62    4.02  116.31    8.27  115.38   17.24  113.52   21.64  109.31
   22.56  108.35   23.38  106.83   23.56  106.55   24.36  105.65   26.58  102.38
   26.94  102.32   30.01  101.16   32.53   100.2   32.94   99.96   33.21  100.15
   35.16  101.29   38.57  103.55    40.2  104.56   40.98  105.31   41.82  105.51
   42.46  105.68   46.55  106.61   48.64  107.44   48.94  107.55   59.43  109.89
   60.66  110.31   65.76  112.09   70.88  113.37   77.19  114.92
#Mann= 3 , 0 , 0
       0     .06       0   30.01     .04       0   35.16    .055       0
Bank Sta=30.01,35.16
XS Rating Curve= 0 ,0
Exp/Cntr=0.3,0.1

Type RM Length L Ch R = 1 ,2010.46 ,3.56,3.08,2.32
XS GIS Cut Line= 6
343768.7166748055422881.75610352343769.9611206055422857.71307373
343773.6945190435422847.76428223343774.9389038095422835.88110352
343770.2376708985422822.06329346343760.005493164 5422808.1072998
#Sta/Elev= 30
       0  116.34    5.67  115.91   12.57   114.4   16.02  113.68   17.86  111.93
   22.34  107.32   24.08  104.11   26.31  100.06   26.37   99.93      27    99.6
   27.63   99.55   27.73   99.54   29.38   99.08   30.65   99.44   32.25   99.72
   34.26  100.96    34.7  101.21   34.76  101.24   38.51  104.87   42.49  105.81
    45.5  106.59   46.09  106.72   46.65  106.94   49.92  108.12   54.09  109.01
   61.27  110.69   64.66  111.24   67.02  112.07   69.74  112.75   78.57  114.92
#Mann= 3 , 0 , 0
       0     .06       0   27.63     .04       0   30.65    .055       0
Bank Sta=27.63,30.65
XS Rating Curve= 0 ,0
Exp/Cntr=0.3,0.1

Type RM Length L Ch R = 1 ,2007.37 ,11.96,10.5,8.32
XS GIS Cut Line= 5
343773.5562744145422877.88708496343773.6945190435422857.85131836
 343776.045104985422847.48791504343780.608093262 5422834.7756958
343760.420288086 5422808.1072998
#Sta/Elev= 25
       0   115.8    3.38  115.55    10.5     114   12.01   113.2   14.09  110.83
   18.45  106.39   19.91  103.69   20.79  101.76   21.49  101.36   23.25  99.372
   23.87   98.52   25.15   98.93   27.44   99.39    27.8   99.52   32.81  104.53
   35.24  105.08   35.96  105.37   40.77  107.79   43.18  108.68   46.07  108.93
   48.41  108.82   49.06  109.01   64.54  111.46   66.26  112.06   77.62  114.86
#Mann= 3 , 0 , 0
       0     .06       0   23.25     .04       0   27.44    .055       0
Bank Sta=23.25,27.44
XS Rating Curve= 0 ,0
Exp/Cntr=0.3,0.1

Type RM Length L Ch R = 1 ,1996.87 ,15.36,13.9,10.86
XS GIS Cut Line= 5
343784.0648803715422878.99249268343785.0328979495422862.27288818
343783.2352905275422855.77868652343784.4796752935422838.64471436
 343760.558471685422807.69268799
#Sta/Elev= 29
       0  115.47    6.56  114.96    8.58  113.29    9.79  112.11   11.15   108.9
      13  106.37   15.16  101.42   17.61   98.44   19.14   98.24   20.26   97.97
   22.32   98.16   22.49   98.16   23.49   98.95   26.73  101.08   28.53   101.6
   28.69  101.71   29.41  102.61   31.06  104.26    31.8   104.9    32.6  105.45
   40.67  108.92   41.28  109.03    41.8  109.03   46.38  108.73   49.94  109.12
   50.65  109.09   66.99  111.66   68.12  112.06   79.78  114.93
#Mann= 3 , 0 , 0
       0     .06       0   19.14     .04       0   22.32    .055       0
Bank Sta=19.14,22.32
XS Rating Curve= 0 ,0
Exp/Cntr=0.3,0.1

Type RM Length L Ch R = 1 ,1982.97 ,16.59,16.72,16.4
XS GIS Cut Line= 3
343804.8842773445422879.11907959343804.4791259775422862.90252686
343760.5501098635422806.34429932
#Sta/Elev= 21
       0  114.86    6.78  114.44     8.3  113.59     9.8  112.24   12.68   108.1
   16.22   105.6    17.3  104.65   26.92   97.89   28.53   97.89   30.05   97.73
   31.61   97.89   32.23   97.93   35.34  100.51   35.64  100.84   37.74  102.74
   43.92  107.91   47.08  109.23   54.14  108.79    56.9   109.1   74.87  112.01
   87.84  115.18
#Mann= 3 , 0 , 0
       0     .06       0   28.53     .04       0   31.61    .055       0
Bank Sta=28.53,31.61
XS Rating Curve= 0 ,0
Exp/Cntr=0.3,0.1

Type RM Length L Ch R = 1 ,1966.25 ,12.09,14.44,16.34
XS GIS Cut Line= 6
343820.0289306645422866.68371582343820.0289306645422855.76751709
343812.7005004885422846.64788818343807.3079223635422839.60089111
343793.4805297855422831.58648682343781.7274780275422814.17608643
#Sta/Elev= 24
       0   112.9     .82  112.89    4.33   112.1    5.69  111.54      10  111.05
   11.14  110.83   14.72  109.55   19.74  104.15   24.14   98.62   26.31   97.45
   27.17   96.75   29.32   97.51   32.23    98.3    33.6   99.16   36.69  101.77
   39.71  103.95   44.42  107.11   46.41  107.42   48.56  107.05   51.76  107.46
   57.14   108.4   60.14  108.57   67.06  112.15   68.48  112.37
#Mann= 3 , 0 , 0
       0     .06       0   26.31     .04       0   29.32    .055       0
Bank Sta=26.31,29.32
XS Rating Curve= 0 ,0
Exp/Cntr=0.3,0.1