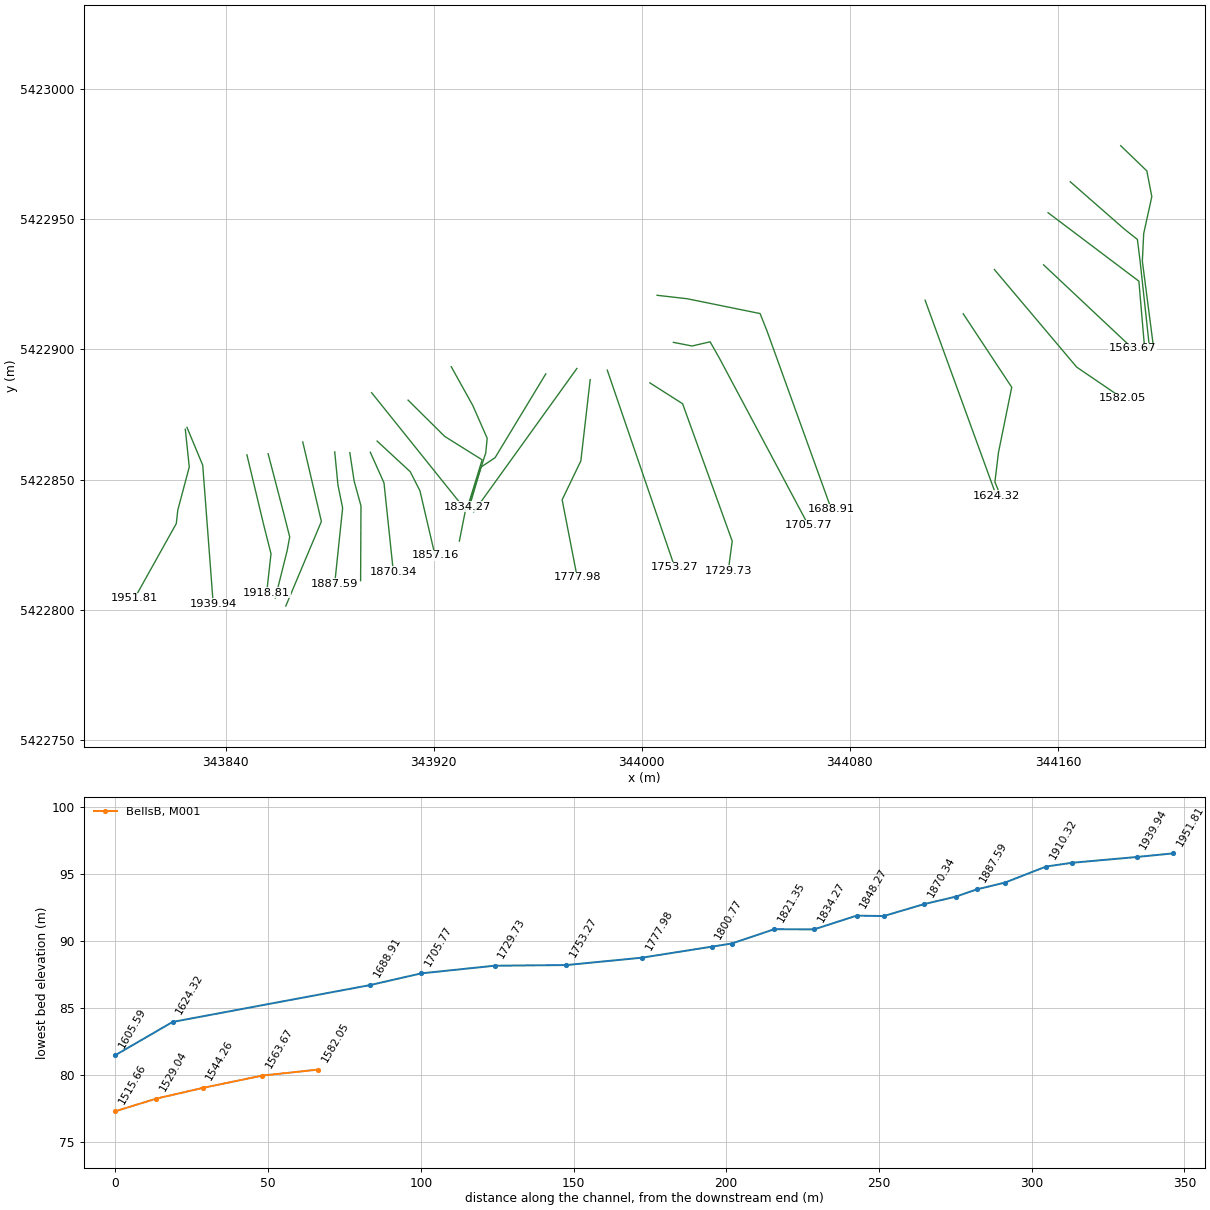
HEC-RAS study Corner_Brook2.prj: Corner_Brook2

--- Corner_Brook2.g03 (geometry) --- (continued)

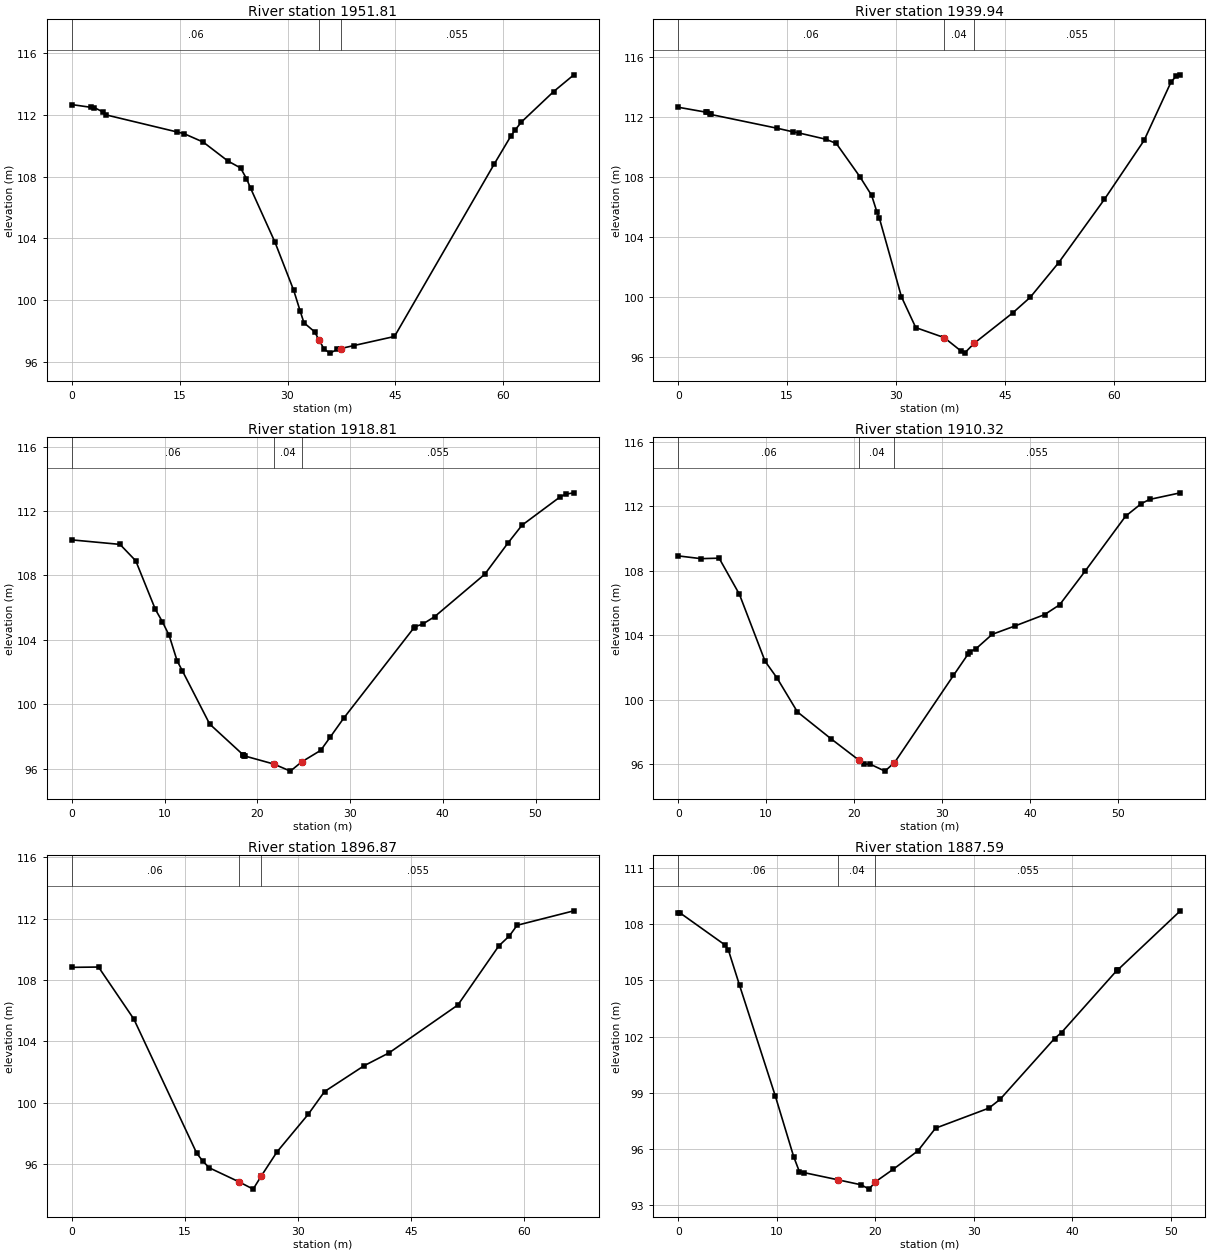
Type RM Length L Ch R = 1 ,1951.81 ,11.11,11.87,15.26
XS GIS Cut Line= 5
343824.4406738285422869.32012939343825.961486816 5422854.8112793
 343821.536926275422838.23010254343820.9838867195422833.11749268
343804.9440917975422804.37652588
#Sta/Elev= 30
       0  112.68    2.71   112.5    3.11  112.49    4.34   112.2    4.78  112.01
   14.59  110.91   15.58   110.8   18.27  110.25   21.71  109.02   23.47  108.57
   24.29  107.88   24.86  107.26   28.25  103.76   30.86  100.63   31.75    99.3
   32.28   98.53   33.75   97.95   34.38   97.42   35.08   96.82   35.91   96.56
   36.89    96.8   37.43   96.86   39.21   97.05   44.87   97.64   58.76  108.84
   61.03  110.62   61.62  111.02   62.52  111.55   66.99  113.52   69.81  114.61
#Mann= 3 , 0 , 0
       0     .06       0   34.38     .04       0   37.43    .055       0
Bank Sta=34.38,37.43
XS Rating Curve= 0 ,0
Exp/Cntr=0.3,0.1

Type RM Length L Ch R = 1 ,1939.94 ,20.43,21.14,21.98
XS GIS Cut Line= 3
343825.0775146485422870.05511475343831.133911133 5422855.5269165
343835.1715087895422802.25708008
#Sta/Elev= 29
       0  112.67    3.85  112.34    3.99  112.33    4.37  112.24    4.48  112.19
   13.64  111.27   15.74  111.04    16.6  110.96   20.32  110.54   21.77  110.26
   25.01  108.05   26.64   106.8   27.35  105.72   27.72  105.26   30.74  100.05
   32.72   97.99    36.6   97.33   36.62   97.33   38.98   96.42   39.44   96.29
   40.76  96.943    46.1   98.98   48.49  100.01   52.41  102.32   58.71  106.54
   64.17  110.46    67.9  114.37   68.62  114.75   69.16  114.83
#Mann= 3 , 0 , 0
       0     .06       0    36.6     .04       0   40.76    .055       0
Bank Sta=36.6,40.76
XS Rating Curve= 0 ,0
Exp/Cntr=0.3,0.1

Type RM Length L Ch R = 1 ,1918.81 ,8.39,8.49,8.56
XS GIS Cut Line= 4
343848.1270751955422859.49609375343854.6259155275422832.41308594
343857.3914794925422821.49707031343855.7321166995422806.57391357
#Sta/Elev= 29
       0  110.21     5.2  109.93     6.9  108.91    9.01   105.9    9.77  105.13
    10.5  104.28   11.36   102.7   11.92  102.09   14.87   98.78   18.48   96.87
   18.51   96.85   18.58   96.82   18.71   96.79   21.78    96.3   23.57   95.86
   24.78   96.43   26.84   97.15   27.85   97.96   29.31   99.14   36.91  104.77
   36.99  104.82   37.82  104.98   39.11  105.44   44.53  108.08   47.02  110.01
   48.54  111.12   52.68  112.89   53.28  113.05   54.13  113.13
#Mann= 3 , 0 , 0
       0     .06       0   21.78     .04       0   24.78    .055       0
Bank Sta=21.78,24.78
XS Rating Curve= 0 ,0
Exp/Cntr=0.3,0.1

Type RM Length L Ch R = 1 ,1910.32 ,13.55,13.45,13.39
XS GIS Cut Line= 5
 343856.285278325422859.91052246343862.507507324 5422836.1439209
343864.5817260745422827.99151611343863.6137084965422822.74072266
343859.0507202155422804.50128174
#Sta/Elev= 27
       0  108.92    2.59  108.75    4.65  108.78    6.96  106.54    9.88  102.39
   11.23  101.36   13.56   99.25   17.37   97.59   20.51   96.28   21.11   96.02
   21.84   96.01   23.52   95.58   24.57    96.1   24.61   96.11   31.31  101.51
   32.98  102.84   33.16  102.98   33.82  103.14   35.72  104.06   38.32  104.58
   41.67  105.28   43.39  105.89   46.31  107.99   50.89  111.38   52.68  112.16
   53.62  112.42   57.12  112.83
#Mann= 3 , 0 , 0
       0     .06       0   20.51     .04       0   24.57    .055       0
Bank Sta=20.51,24.57
XS Rating Curve= 0 ,0
Exp/Cntr=0.3,0.1

Type RM Length L Ch R = 1 ,1896.87 ,9.42,9.28,9.18
XS GIS Cut Line= 3
343869.6077270515422864.45111084343876.771118164 5422833.8939209
343863.0836791995422801.41888428
#Sta/Elev= 19
       0  108.82    3.55  108.84    8.24  105.45   16.59   96.71   17.41   96.19
   18.24   95.77   22.17   94.86   24.07   94.38   25.17   95.25   27.23    96.8
   31.39   99.26   33.54  100.73   38.78  102.41    42.1  103.25   51.24  106.37
   56.68  110.22   58.08  110.87    59.1  111.56   66.63   112.5
#Mann= 3 , 0 , 0
       0     .06       0   22.17     .04       0   25.17    .055       0
Bank Sta=22.17,25.17
XS Rating Curve= 0 ,0
Exp/Cntr=0.3,0.1

Type RM Length L Ch R = 1 ,1887.59 ,6.51,6.81,7.02
XS GIS Cut Line= 4
343881.896911621 5422860.6217041343883.1412963875422847.90930176
343884.9389038095422839.06591797343881.8969116215422810.04870605
#Sta/Elev= 24
       0  108.59     .18   108.6    4.72   106.9    5.09  106.62    6.23  104.73
    9.87   98.81   11.72    95.6    12.3    94.8   12.77   94.75   16.19   94.37
   18.57    94.1   19.37   93.87   20.02  94.261    21.8   94.92   24.33   95.91
   26.12   97.12   31.54   98.19   32.66   98.65    38.2   101.9   38.91  102.22
   44.51  105.52   44.56  105.54   44.62  105.56   50.97  108.71
#Mann= 3 , 0 , 0
       0     .06       0   16.19     .04       0   20.02    .055       0
Bank Sta=16.19,20.02
XS Rating Curve= 0 ,0
Exp/Cntr=0.3,0.1

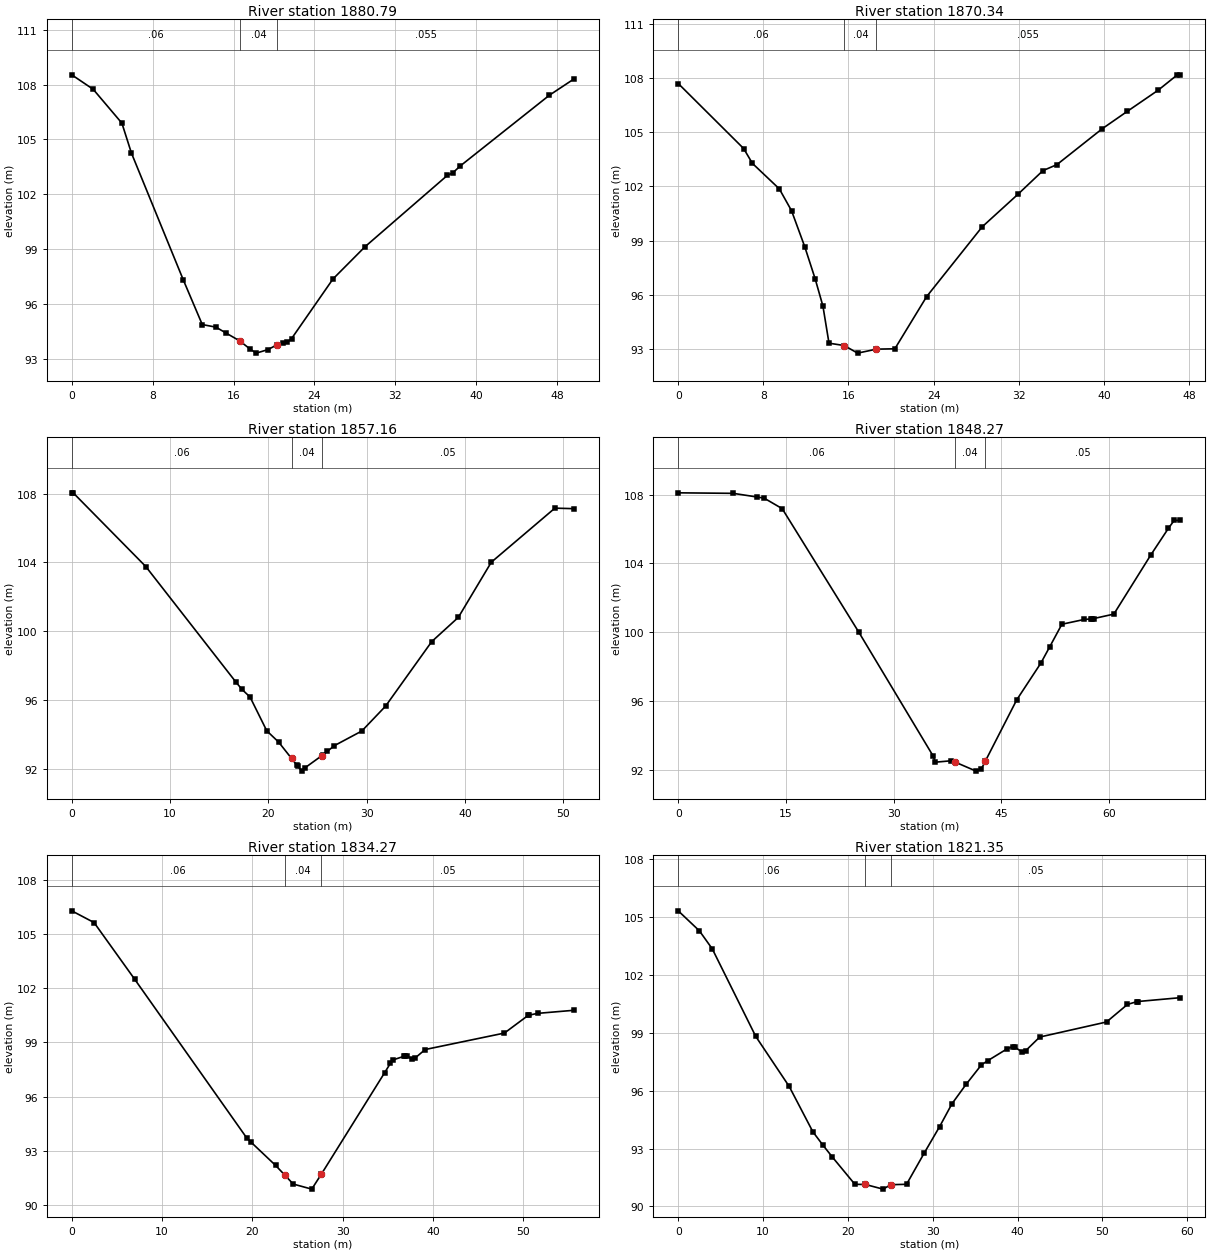
Type RM Length L Ch R = 1 ,1880.79 ,11.11,10.44,9.91
XS GIS Cut Line= 4
343887.7042846685422860.34527588343889.3635253915422849.42932129
343891.9907226565422839.89508057343891.8524780275422811.15411377
#Sta/Elev= 23
       0  108.53    2.12  107.74    4.96  105.89     5.9  104.26   11.04   97.32
   12.91   94.89   14.26   94.75   15.22   94.44   16.61      94   17.67   93.54
   18.25   93.33   19.39   93.52   20.33   93.79   20.93   93.87   21.31   93.92
   21.74   94.12   25.84   97.38   29.01   99.14   37.16  103.04    37.7  103.18
   38.45  103.56   47.26  107.42   49.67   108.3
#Mann= 3 , 0 , 0
       0     .06       0   16.61     .04       0   20.33    .055       0
Bank Sta=16.61,20.33
XS Rating Curve= 0 ,0
Exp/Cntr=0.3,0.1

Type RM Length L Ch R = 1 ,1870.34 ,11.52,13.18,13.86
XS GIS Cut Line= 3
343895.5858764655422860.48352051343900.8400878915422848.73828125
343904.4353027345422814.60852051
#Sta/Elev= 23
       0  107.69    6.15  104.09    6.97  103.27     9.5  101.86   10.65  100.65
   11.89   98.66   12.87   96.88    13.6   95.37   14.17   93.32    15.6   93.19
   16.86   92.77   18.63   92.99   20.36   93.01   23.35    95.9   28.57   99.76
   31.91  101.55   34.28  102.87   35.59   103.2   39.86  105.19   42.21  106.15
   45.11  107.32   46.91  108.17   47.19  108.16
#Mann= 3 , 0 , 0
       0     .06       0    15.6     .04       0   18.63    .055       0
Bank Sta=15.6,18.63
XS Rating Curve= 0 ,0
Exp/Cntr=0.3,0.1

Type RM Length L Ch R = 1 ,1857.16 ,7.94,8.89,10
XS GIS Cut Line= 4
 343898.213073735422864.76708984343910.9340820315422853.02191162
343914.6674804695422845.69848633343920.4749145515422820.82647705
#Sta/Elev= 24
       0  108.04     .16  108.03    7.53  103.76    16.7   97.05   17.31   96.63
   18.14   96.18   19.84   94.22   21.04   93.57   22.36  92.617   22.91   92.22
   23.02   92.15   23.39   91.88   23.77   92.09   25.42   92.77   25.53   92.82
   25.98   93.02   26.72   93.36   29.51   94.21   31.92   95.65   36.62    99.4
   39.33  100.81   42.68  104.01   49.15  107.15   51.08  107.12
#Mann= 3 , 0 , 0
       0     .06       0   22.36     .04       0   25.42     .05       0
Bank Sta=22.36,25.42
XS Rating Curve= 0 ,0
Exp/Cntr=0.3,0.1

Type RM Length L Ch R = 1 ,1848.27 ,12.45,13.99,15.17
XS GIS Cut Line= 3
343896.088500977 5422883.3649292343932.2098999025422838.39147949
343929.8264770515422826.35388184
#Sta/Elev= 26
       0  108.11    7.65  108.08   10.94  107.87   11.97   107.8   14.48  107.19
   25.17   99.99    35.5    92.8   35.82   92.43   37.95   92.51    38.5   92.45
    41.5   91.91   42.22   92.03   42.78  92.487   47.16   96.06   50.51   98.19
   51.76   99.15   53.45  100.46   56.58  100.74   57.57  100.77   57.68  100.78
   57.87  100.79   60.69  101.05   65.85   104.5    68.3  106.05   69.09   106.5
   69.95  106.51
#Mann= 3 , 0 , 0
       0     .06       0    38.5     .04       0   42.78     .05       0
Bank Sta=38.5,42.78
XS Rating Curve= 0 ,0
Exp/Cntr=0.3,0.1

Type RM Length L Ch R = 1 ,1834.27 ,15.6,12.92,10.12
XS GIS Cut Line= 4
343910.1044921885422880.51928711343924.2083129885422866.56329346
343938.5886840825422857.58172607343933.0576782235422839.61871338
#Sta/Elev= 24
       0  106.27    2.47  105.62    6.96  102.49    19.4   93.69   19.84   93.48
   22.57   92.19   23.56   91.67   24.52   91.16   26.57   90.88   27.65   91.72
   34.63   97.31   35.27   97.83   35.54   98.02    36.8   98.23   36.94   98.26
   37.15   98.23   37.65   98.08   37.99   98.12   39.13    98.6    47.9   99.51
   50.54  100.49   50.62   100.5   51.59   100.6   55.59  100.77
#Mann= 3 , 0 , 0
       0     .06       0   23.56     .04       0   27.65     .05       0
Bank Sta=23.56,27.65
XS Rating Curve= 0 ,0
Exp/Cntr=0.3,0.1

Type RM Length L Ch R = 1 ,1821.35 ,17.76,13.93,9.68
XS GIS Cut Line= 5
 343926.697082525422893.36987305343934.9935302735422878.44671631
343940.5244750985422865.87249756343939.9713134775422860.20709229
343932.9194946295422838.65148926
#Sta/Elev= 30
       0  105.32     2.5  104.28    4.01  103.35    9.14   98.81   13.08   96.22
   15.87   93.87   17.07   93.17   18.17   92.56   20.82   91.15   22.07   91.14
   24.14    90.9   25.07   91.13   26.91   91.15   28.97   92.75   30.81   94.14
   32.26   95.32   33.93   96.33   35.74   97.34    36.5   97.56   38.73   98.16
   39.41   98.29   39.72   98.24   40.48   98.02   40.97   98.08   42.61   98.78
   50.48   99.56   52.95  100.47   54.03  100.61   54.14  100.62   59.18  100.82
#Mann= 3 , 0 , 0
       0     .06       0   22.07     .04       0   25.07     .05       0
Bank Sta=22.07,25.07
XS Rating Curve= 0 ,0
Exp/Cntr=0.3,0.1

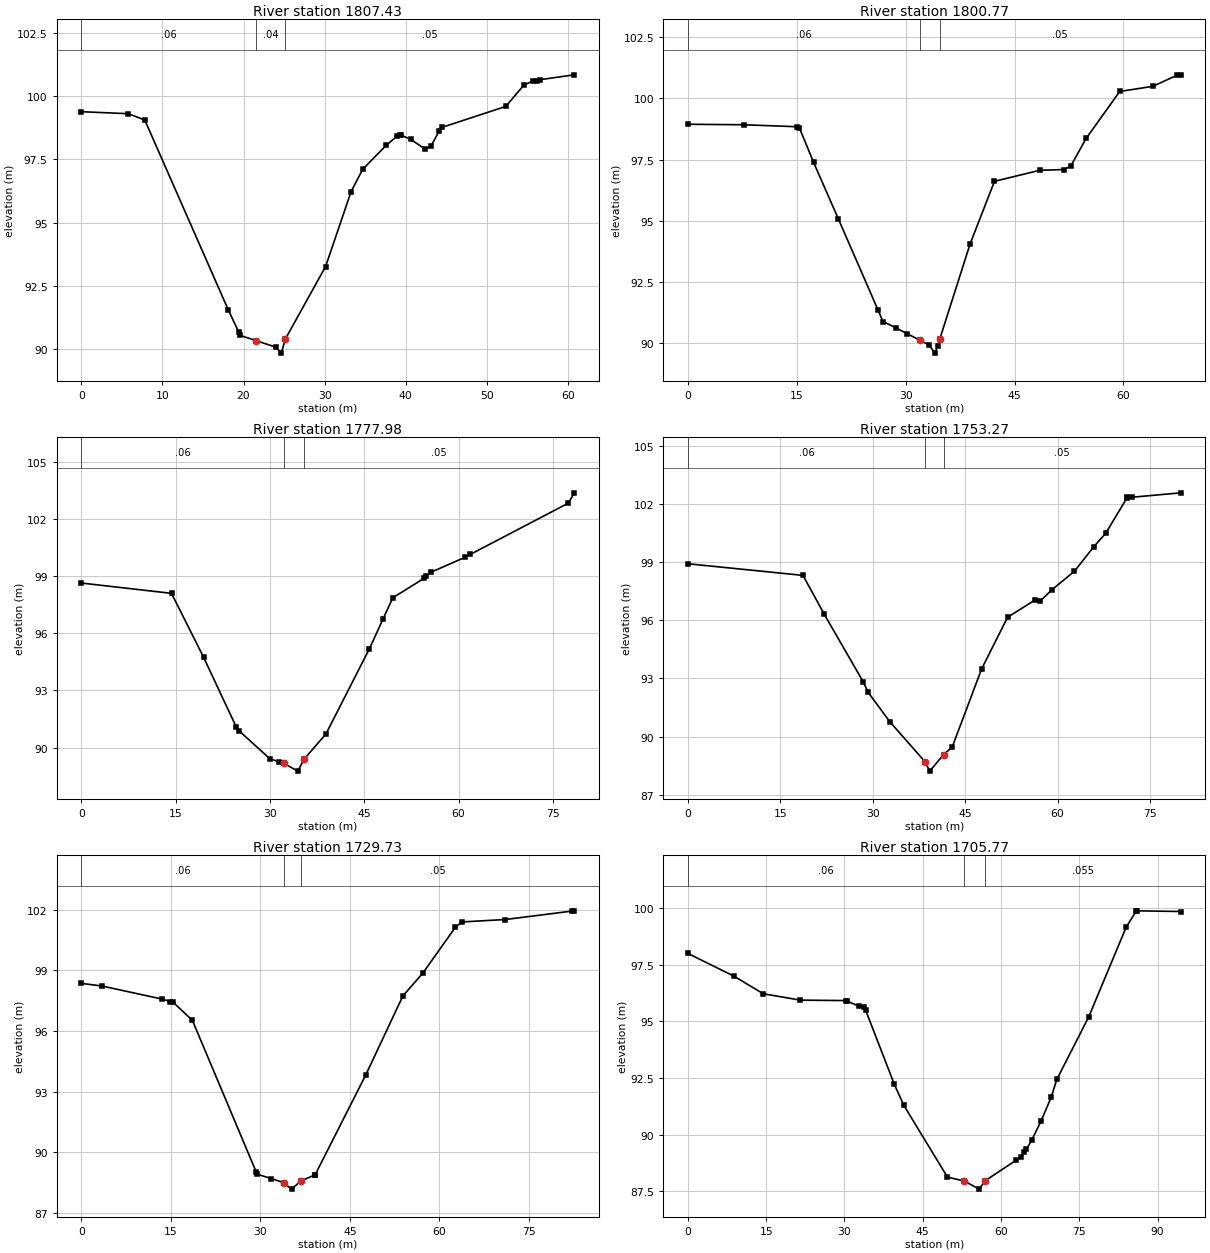
Type RM Length L Ch R = 1 ,1807.43 ,6.99,6.66,6.33
XS GIS Cut Line= 4
343963.0629272465422890.60632324 343943.566528325422858.41088867
 343938.173889165422854.81829834343933.4724731455422838.78967285
#Sta/Elev= 28
       0   99.39    5.79   99.31    7.82   99.06   18.11   91.55    19.4   90.67
    19.6   90.53   21.59   90.32   23.95   90.07   24.67   89.83   25.15   90.38
   30.13   93.26   33.28   96.23   34.71   97.11   37.64   98.07   38.95   98.42
   39.27   98.46   39.39   98.47   40.66   98.29   42.45    97.9   43.12   98.02
   44.12   98.61    44.5   98.77   52.37    99.6   54.64  100.46   55.74   100.6
   56.21  100.61   56.64  100.66   60.82  100.85
#Mann= 3 , 0 , 0
       0     .06       0   21.59     .04       0   25.15     .05       0
Bank Sta=21.59,25.15
XS Rating Curve= 0 ,0
Exp/Cntr=0.3,0.1

Type RM Length L Ch R = 1 ,1800.77 ,20.94,22.78,23.41
XS GIS Cut Line= 2
343975.0184936525422892.67388916343935.345092773 5422837.5770874
#Sta/Elev= 25
       0   98.94    7.72   98.92      15   98.84   15.35    98.8   17.32   97.38
   20.73   95.07   26.19   91.35   26.87   90.88   28.67   90.62   30.17   90.39
   31.99  90.111   33.17   89.93   34.05   89.59   34.41    89.9   34.68  90.151
   38.88   94.06   42.23   96.61   48.48   97.06   51.82   97.09   52.73   97.23
   54.85   98.36   59.48  100.28   64.04  100.49   67.43  100.95   67.89  100.96
#Mann= 3 , 0 , 0
       0     .06       0   31.99     .04       0   34.68     .05       0
Bank Sta=31.99,34.68
XS Rating Curve= 0 ,0
Exp/Cntr=0.3,0.1

Type RM Length L Ch R = 1 ,1777.98 ,21.46,24.72,28.06
XS GIS Cut Line= 4
343980.1383056645422888.39147949343976.5432739265422857.16333008
343969.353088379 5422842.2401123343975.1605224615422812.39367676
#Sta/Elev= 21
       0   98.63   14.33   98.09   19.42   94.75   24.65   91.07   25.12   90.87
   29.94   89.43   31.43   89.25   32.26   89.17   34.42   88.77   35.43    89.4
    38.9   90.72   45.79   95.17      48   96.76   49.54   97.86   54.51   98.88
   54.85   99.01   55.63    99.2   61.03   99.98   61.85  100.13   77.47  102.82
   78.41  103.36
#Mann= 3 , 0 , 0
       0     .06       0   32.26     .04       0   35.43     .05       0
Bank Sta=32.26,35.43
XS Rating Curve= 0 ,0
Exp/Cntr=0.3,0.1

Type RM Length L Ch R = 1 ,1753.27 ,23.46,23.53,23.82
XS GIS Cut Line= 2
 343986.71307373 5422892.0324707344012.6475219735422816.35290527
#Sta/Elev= 22
       0   98.92   18.68   98.32   22.14   96.31   28.45   92.83   29.25   92.29
   32.77   90.77    38.5    88.7   39.25   88.22    41.5   89.07   42.91   89.47
   47.67   93.49   51.89   96.16    56.3   97.04   57.21      97   59.09   97.58
   62.73   98.53   65.88    99.8   67.81  100.49   71.29  102.33   71.32  102.34
   72.02  102.35      80  102.58
#Mann= 3 , 0 , 0
       0     .06       0    38.5     .04       0    41.5     .05       0
Bank Sta=38.5,41.5
XS Rating Curve= 0 ,0
Exp/Cntr=0.3,0.1

Type RM Length L Ch R = 1 ,1729.73 ,23.22,23.97,25.7
XS GIS Cut Line= 4
344003.0916748055422887.14788818344015.6744995125422879.13348389
344034.7561035165422826.34967041344033.2351074225422814.88092041
#Sta/Elev= 22
       0   98.35    3.45   98.22   13.56   97.57   14.92   97.45   15.28   97.44
    18.6   96.52   29.29   89.02   29.47   88.91   31.83   88.69   33.89  88.492
   35.21   88.17   36.78  88.572   39.18   88.88   39.19   88.89   47.64   93.81
   53.88   97.73   57.23   98.86   62.66  101.12   63.76  101.39   71.05  101.51
    82.3  101.93   82.61  101.94
#Mann= 3 , 0 , 0
       0     .06       0   33.89     .04       0   36.78     .05       0
Bank Sta=33.89,36.78
XS Rating Curve= 0 ,0
Exp/Cntr=0.3,0.1

Type RM Length L Ch R = 1 ,1705.77 ,17.93,16.86,16.52
Node Photo=..\..\..\..\Corner Brook\Windshield Survey\CB photos\P1000705.JPG
XS GIS Cut Line= 5
      344012.139     5422902.717      344019.302     5422901.315
       344026.26     5422902.924      344029.788     5422896.702
      344064.067     5422832.421
#Sta/Elev= 28
       0      98     8.8      97   14.44   96.22   21.54   95.94    30.3   95.92
   30.41   95.91   32.85   95.66   33.78   95.64   34.05    95.5   39.56   92.22
   41.37    91.3   49.73   88.13   52.91   87.96   55.84    87.6    56.9  87.962
   62.86   88.87    63.9   89.02   64.48   89.24   64.86   89.36   65.86   89.75
    67.7   90.62    69.6   91.65   70.69   92.44   76.82   95.21   83.98   99.16
    85.9   99.87   86.12   99.88   94.44   99.85
#Mann= 3 , 0 , 0
       0     .06       0   52.91    .035       0    56.9    .055       0
Bank Sta=52.91,56.9
XS Rating Curve= 0 ,0
Exp/Cntr=0.3,0.1

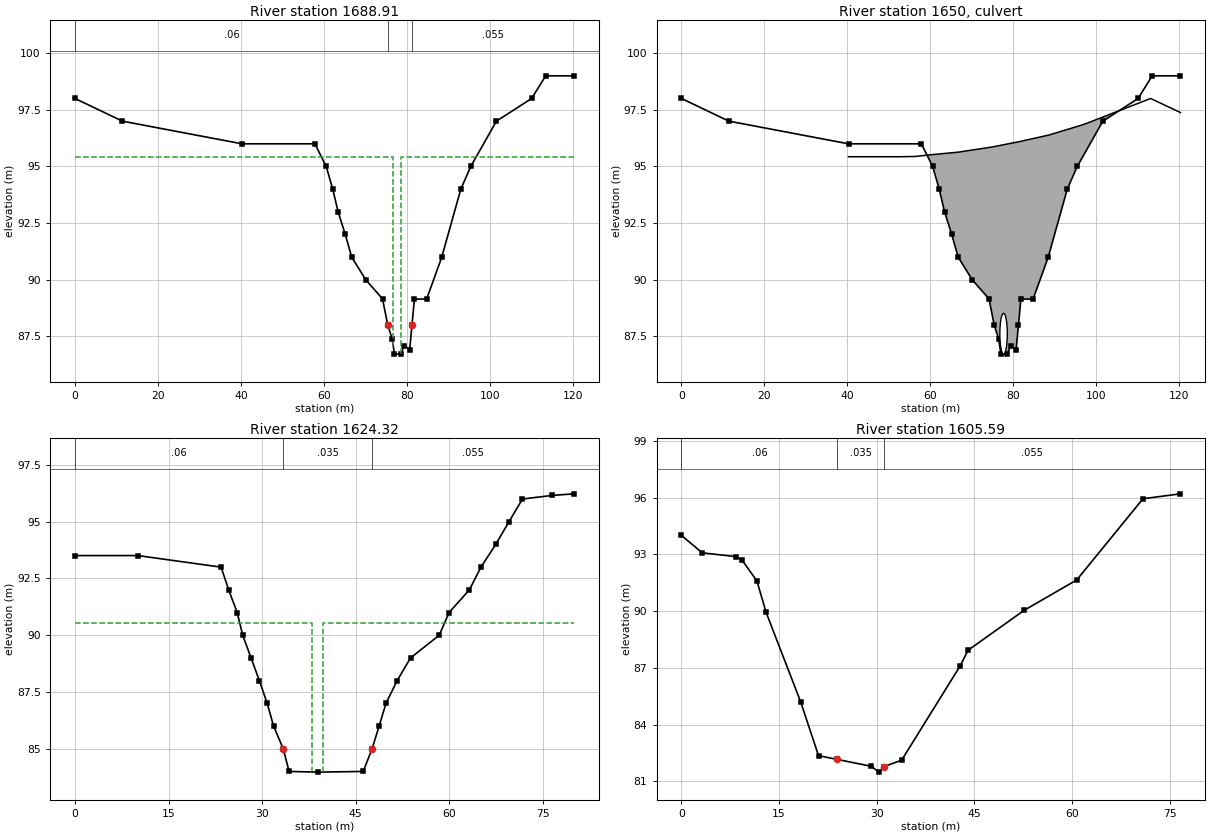
Type RM Length L Ch R = 1 ,1688.91 ,64.88,64.59,65.49
XS GIS Cut Line= 5
      344005.862     5422920.796      344017.456     5422919.468
      344045.474     5422913.779      344048.045     5422907.328
       344072.87     5422838.617
#Sta/Elev= 27
       0      98   11.43      97   40.26      96   57.82      96   60.54      95
   62.12      94   63.41      93   65.14      92   66.69      91   70.08      90
   74.11   89.16   75.38      88   76.46   87.38   76.99   86.72   78.53   86.72
   79.32   87.09   80.66   86.92   81.21  87.996    81.8   89.15   84.75   89.15
   88.39      91   92.98      94   95.38      95  101.56      97  110.05      98
  113.44      99  120.26      99
#Mann= 3 , 0 , 0
       0     .06       0   75.38    .035       0   81.21    .055       0
#XS Ineff= 2 , 0
       0   76.73   95.43   78.53       0   95.43
Permanent Ineff=
       F       F
Bank Sta=75.38,81.21
XS Rating Curve= 0 ,0
Exp/Cntr=0.5,0.3

Type RM Length L Ch R = 2 ,1650    ,,,
BEGIN DESCRIPTION:
Bliss Street (Structure #2120)
END DESCRIPTION:
Bridge Culvert--1,0,-1,-1, 0
Deck Dist Width WeirC Skew NumUp NumDn MinLoCord MaxHiCord MaxSubmerge Is_Ogee
21.2,15.5,1.67,0, 11, 13, 95.43, , 0.98, 0, 0.7,0.53,,
   40.26   52.35   56.26   60.77   66.61   74.88   81.52   88.61   97.05  113.06
  120.26
   95.43   95.43   95.44   95.53   95.63   95.86    96.1   96.39   96.86      98
   97.38
                                                                                
        
       0   10.32   13.62   17.53   22.04   28.85   36.98   44.83   51.73   59.58
   67.12    75.2      80
      95      95   95.43   95.44   95.53   94.97   95.53   96.06   96.49   96.95
   97.28   97.38   97.38
                                                                                
                        
BR Coef=-1 , 0 , 0 ,, 0 ,,,0.8,-1,,0,
WSPro=,,,, 1 ,,,, 0 ,,,, 0 ,,,,-1 ,-1 ,-1 , 0 , 0 , 0 , 0 , 0
Culvert=1,1.8,,56,0.03,0.5,1,2,1,86.72,77.63,84.33,38.91,Culvert #1  , 0 ,4.4
Culvert Bottom n=0.03
BC Design=,, 0 ,, 0 ,,,,,,
BC Use User HTab Curves=0
BC User HTab FreeFlow(D)= 0

Type RM Length L Ch R = 1 ,1624.32 ,17.6,18.73,19.48
Node Photo=..\..\..\..\Corner Brook\Windshield Survey\CB photos\P1000701.JPG
XS GIS Cut Line= 2
344108.9406738285422918.89208984344136.3378906255422843.72967529
#Sta/Elev= 28
       0   93.51   10.08   93.51   23.42      93   24.64      92      26      91
   26.89      90   28.23      89   29.56      88   30.81      87   31.84      86
   33.38      85   34.32      84   38.91   83.97   46.21      84   47.63      85
   48.76      86   49.86      87   51.64      88   53.79      89   58.39      90
   59.97      91   63.23      92   65.08      93   67.45      94   69.57      95
   71.74      96   76.49   96.16      80   96.23
#Mann= 3 , 0 , 0
       0     .06       0   33.38    .035       0   47.63    .055       0
#XS Ineff= 2 , 0
       0   38.01   90.55   39.81       0   90.55
Permanent Ineff=
       F       F
Bank Sta=33.38,47.63
XS Rating Curve= 0 ,0
Exp/Cntr=0.5,0.3

Type RM Length L Ch R = 1 ,1605.59 ,22.78,23.54,25
Node Photo=..\..\..\..\Corner Brook\Windshield Survey\CB photos\P1000703.JPG
XS GIS Cut Line= 5
344123.5905151375422913.68847656344142.2462768555422885.46252441
344137.1588745125422860.46691895344135.7728881845422849.03912354
 344138.025329595422843.67150879
#Sta/Elev= 19
       0      94     3.2   93.08    8.42   92.88    9.29   92.71    11.6   91.59
      13   89.94   18.32    85.2   21.06   82.36   23.96   82.16   29.14    81.8
   30.37   81.49   31.08   81.78   33.83   82.12   42.83   87.11   44.03   87.93
   52.64   90.04   60.74   91.65   70.91   95.94   76.67    96.2
#Mann= 3 , 0 , 0
       0     .06       0   23.96    .035       0   31.08    .055       0
Bank Sta=23.96,31.08
XS Rating Curve= 0 ,0
Exp/Cntr=0.3,0.1

River Reach=BellsB          ,M001

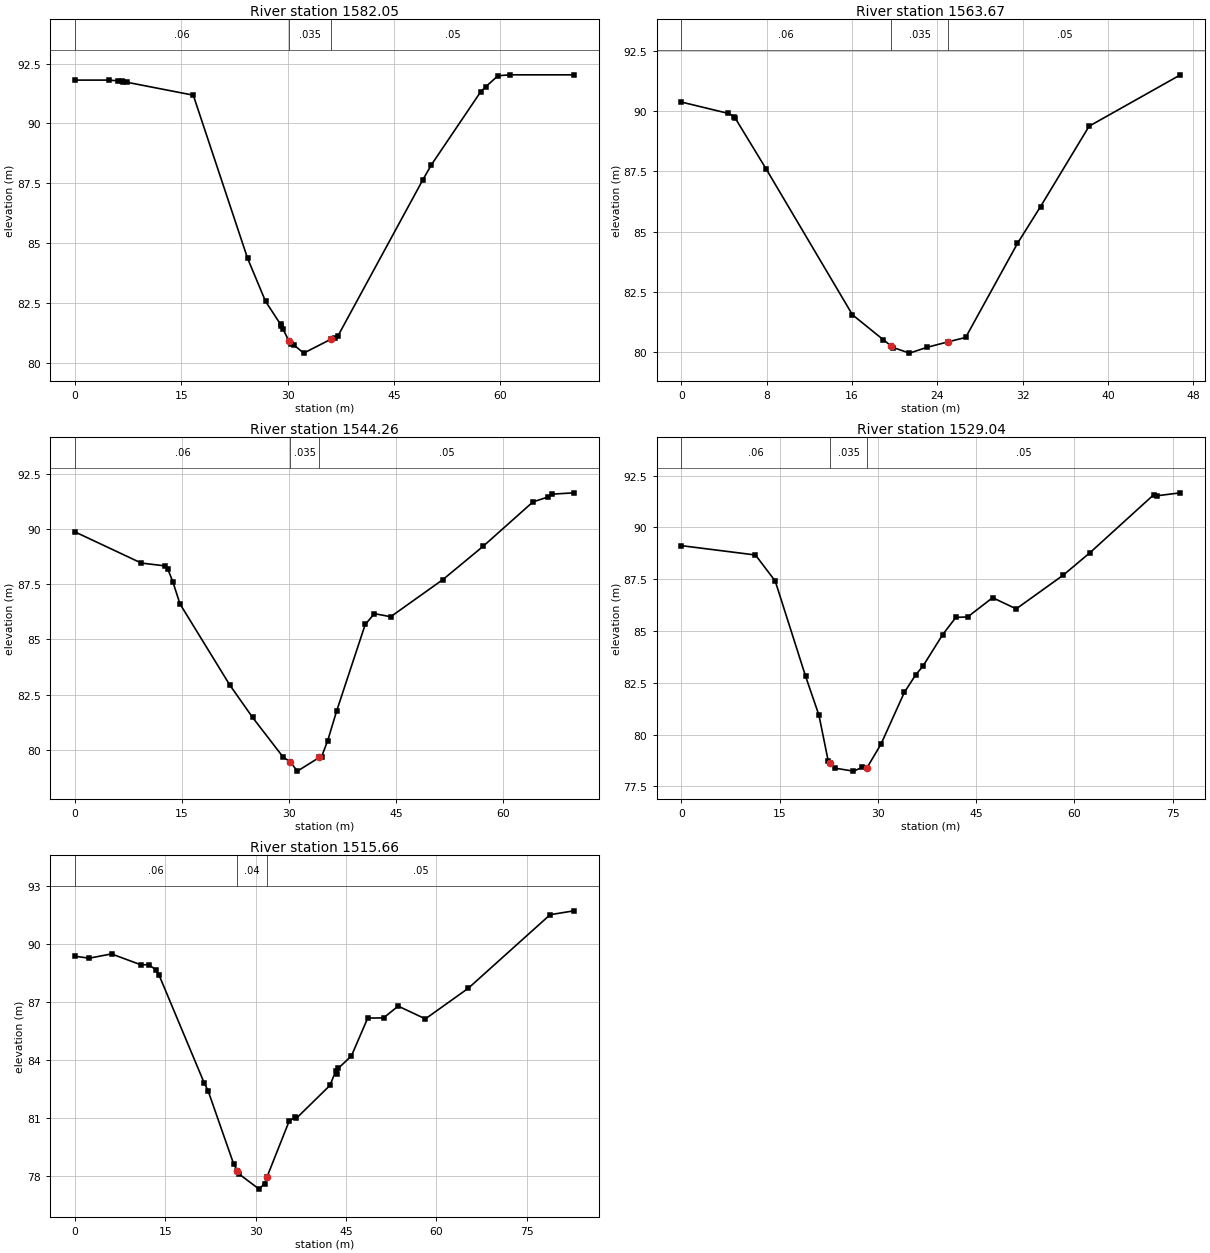
Type RM Length L Ch R = 1 ,1582.05 ,17.81,18.37,19.1
XS GIS Cut Line= 3
344135.5728759775422930.68328857344167.2293090825422893.19610596
344184.8796997075422881.19189453
#Sta/Elev= 26
       0   91.81    4.82   91.81       6   91.78    6.57   91.77    6.77   91.75
    7.32   91.72   16.69   91.18   24.35   84.37   26.89   82.57   29.01   81.61
   29.11   81.53   29.37    81.4   30.17  80.928   30.42   80.78   30.93   80.74
   32.27   80.41   36.11   80.99    36.7   81.05   37.07   81.11   49.07   87.64
   50.28   88.27   57.24   91.32   57.95   91.53   59.68   91.99   61.34   92.03
   70.41   92.03
#Mann= 3 , 0 , 0
       0     .06       0   30.17    .035       0   36.11     .05       0
Bank Sta=30.17,36.11
XS Rating Curve= 0 ,0
Exp/Cntr=0.3,0.1

Type RM Length L Ch R = 1 ,1563.67 ,18.98,19.42,20.26
XS GIS Cut Line= 2
344154.485717773 5422932.4967041344188.6195068365422900.46429443
#Sta/Elev= 17
       0   90.37     4.4    89.9    4.94   89.77    5.02   89.72    7.94    87.6
   16.04   81.55   18.95   80.51   19.66   80.26   19.87   80.19   21.39   79.96
   23.03    80.2   25.03   80.43   26.66   80.61   31.52   84.51   33.69   86.04
   38.24   89.37   46.81    91.5
#Mann= 3 , 0 , 0
       0     .06       0   19.66    .035       0   25.03     .05       0
Bank Sta=19.66,25.03
XS Rating Curve= 0 ,0
Exp/Cntr=0.3,0.1

Type RM Length L Ch R = 1 ,1544.26 ,15.64,15.21,13.49
XS GIS Cut Line= 3
344156.2185058595422952.52209473344191.1436767585422926.21228027
344193.3801269535422900.07452393
#Sta/Elev= 24
       0   89.87     9.3   88.46   12.68   88.33   13.01   88.19   13.72   87.61
   14.72   86.61    21.7   82.94    24.9   81.47   29.17   79.68   30.17   79.46
   31.18   79.04   34.26   79.66   34.58    79.7   35.43   80.42   36.69   81.77
   40.69   85.68   41.98   86.17   44.26   86.03   51.57   87.71   57.19   89.21
   64.21   91.23   66.31   91.45   66.89   91.58   69.96   91.64
#Mann= 3 , 0 , 0
       0     .06       0   30.17    .035       0   34.26     .05       0
Bank Sta=30.17,34.26
XS Rating Curve= 0 ,0
Exp/Cntr=0.3,0.1

Type RM Length L Ch R = 1 ,1529.04 ,18.66,13.38,5.34
XS GIS Cut Line= 5
344164.751708984 5422964.4151001344185.5438842775422946.23449707
344190.568725586 5422942.2520752344191.6082763675422933.94091797
344195.2468872075422900.35009766
#Sta/Elev= 25
       0   89.12    11.3   88.67   14.32   87.41   18.96   82.81   20.99   80.94
   22.42   78.71   22.69   78.63    23.5   78.38   26.26   78.24   27.62   78.42
   28.34   78.41   30.46   79.54   34.03   82.04   35.79    82.9   36.86    83.3
   39.89   84.83    41.9   85.66    43.7   85.68   47.51   86.61   51.11   86.07
    58.3    87.7   62.37   88.78   72.08   91.57   72.64   91.53   76.19   91.67
#Mann= 3 , 0 , 0
       0     .06       0   22.69    .035       0   28.34     .05       0
Bank Sta=22.69,28.34
XS Rating Curve= 0 ,0
Exp/Cntr=0.3,0.1

Type RM Length L Ch R = 1 ,1515.66 ,11.06,13.23,17.9
XS GIS Cut Line= 6
344184.1577148445422978.26690674344194.2072753915422968.57067871
 344196.113281255422958.70111084344192.9945068365422944.50292969
344192.4744873055422933.94091797344196.8062744145422900.52331543
#Sta/Elev= 30
       0   89.35    2.36   89.25    6.06   89.47      11    88.9   12.23   88.92
   13.45   88.64   13.96   88.37   21.44    82.8   22.08    82.4   26.35   78.59
   26.95   78.26   27.29   78.07   30.56    77.3   31.46   77.59    31.9   77.95
   35.55   80.82   36.48   81.01   36.73   80.96   42.33   82.67    43.3   83.43
   43.45   83.25   43.73   83.56   45.88   84.19   48.59   86.15   51.22   86.16
   53.64   86.77   58.16   86.11   65.27   87.69   78.87    91.5   82.83    91.7
#Mann= 3 , 0 , 0
       0     .06       0   26.95     .04       0    31.9     .05       0
Bank Sta=26.95,31.9
XS Rating Curve= 0 ,0
Exp/Cntr=0.3,0.1