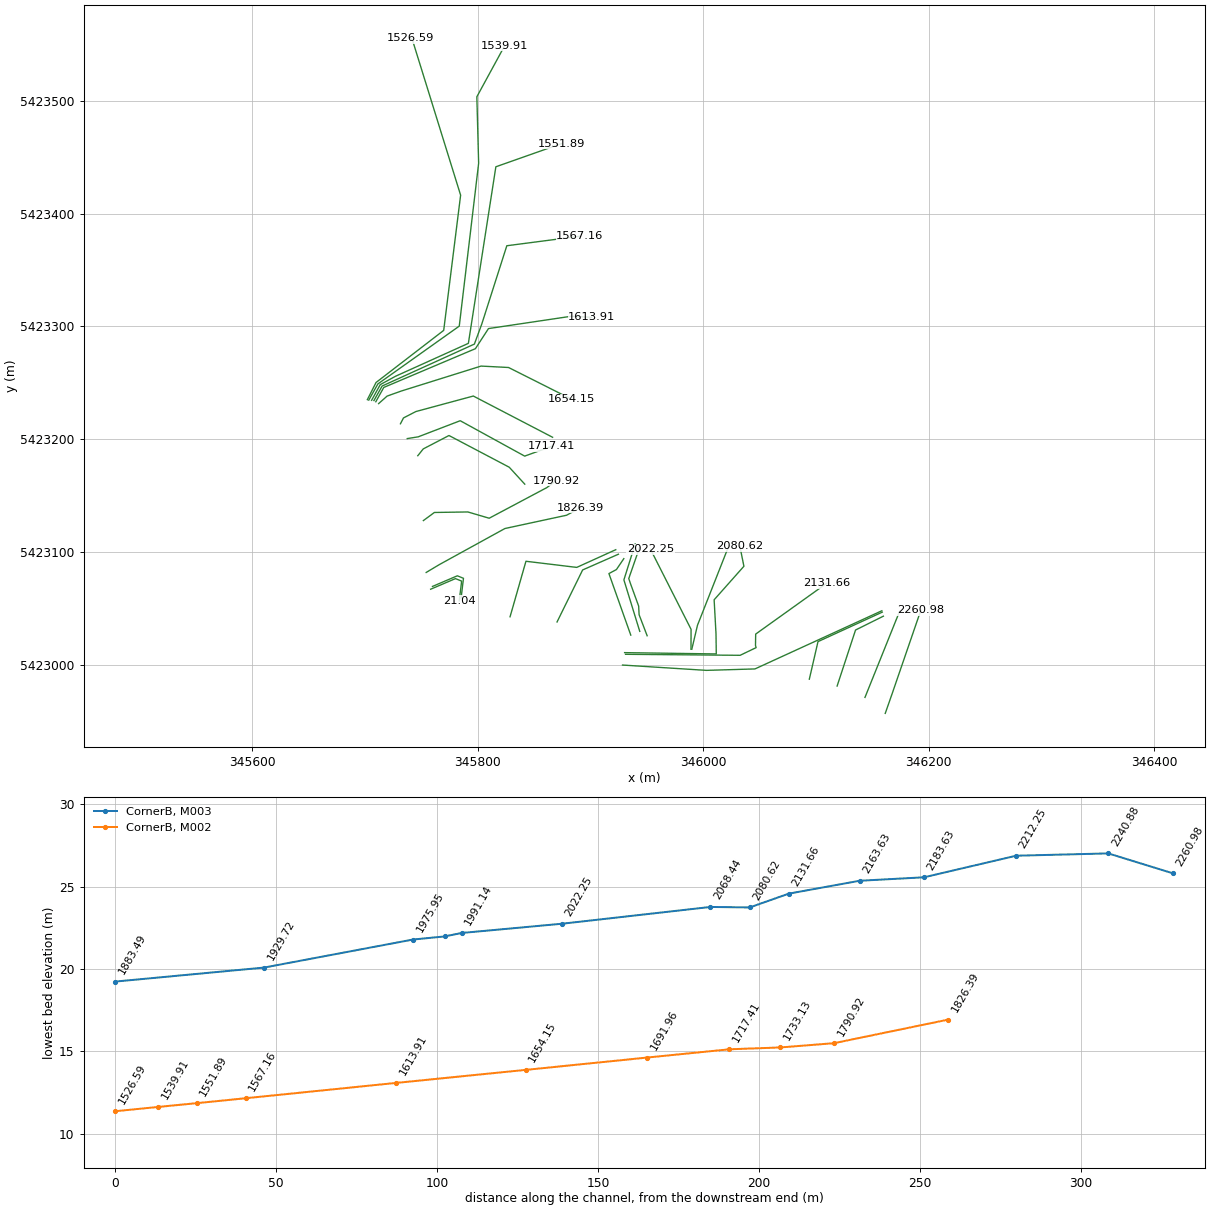
HEC-RAS study Corner_Brook2.prj: Corner_Brook2

--- Corner_Brook2.g03 (geometry) --- (continued)

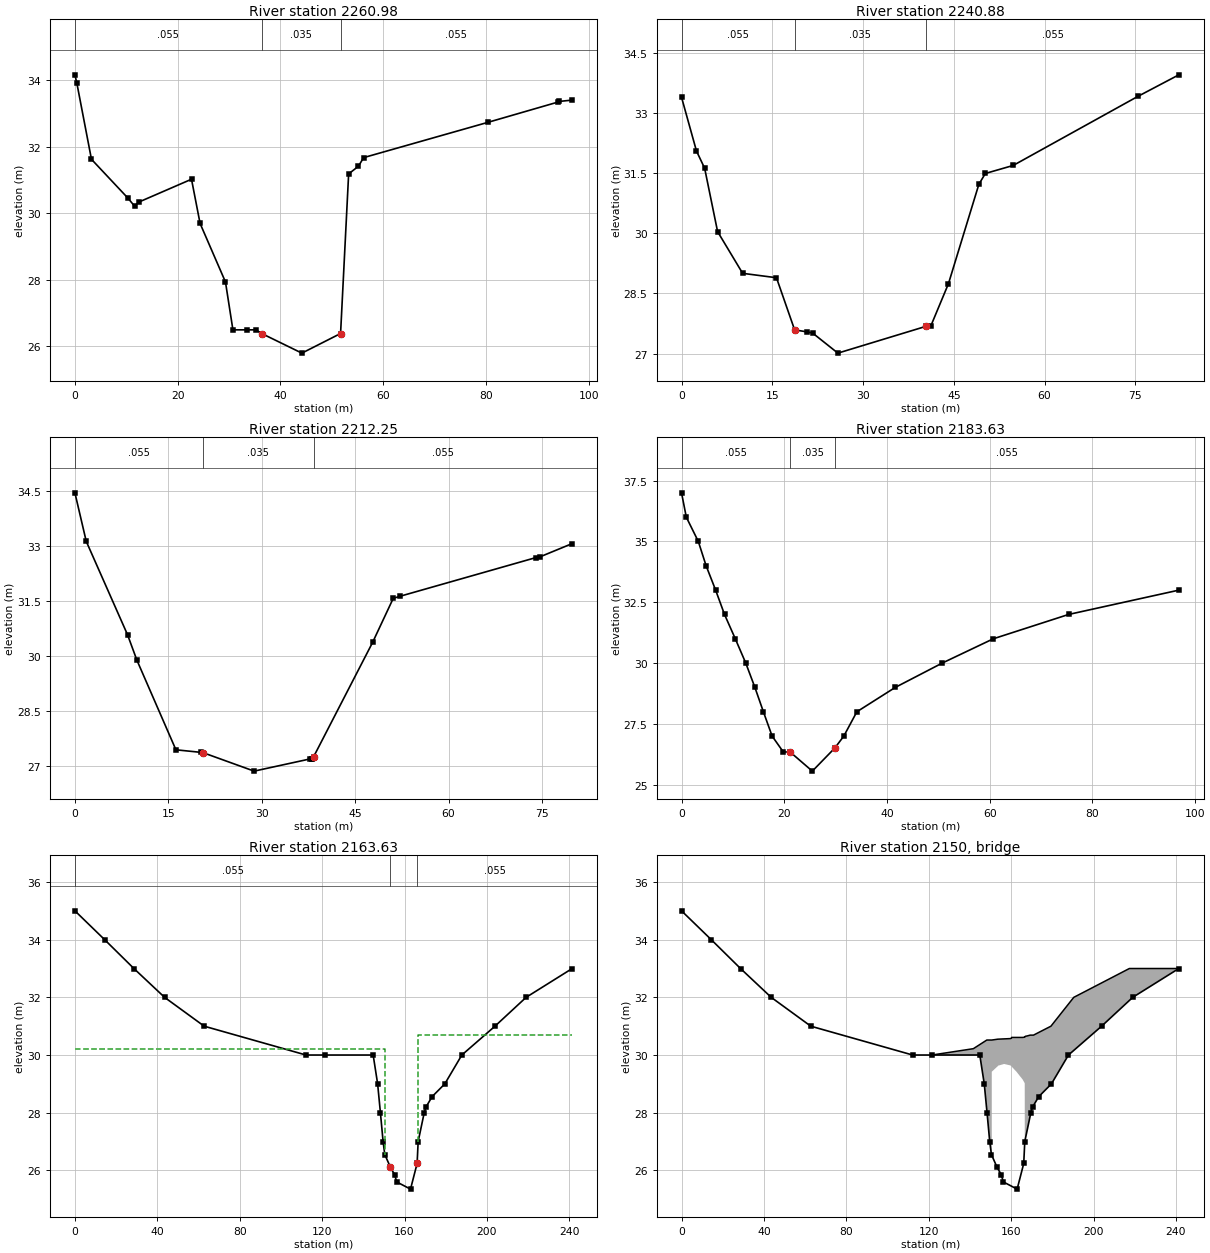
Type RM Length L Ch R = 1 ,2260.98 ,23.13,20.09,20.28
Node Photo=..\..\..\Corner Brook\Windshield Survey\CB photos\P1000676.JPG
XS GIS Cut Line= 3
      346161.359     5422956.991       346166.76     5422972.345
      346192.969     5423048.462
#Sta/Elev= 22
       0   34.17     .39   33.91    3.22   31.63   10.33   30.46   11.61   30.22
   12.39   30.34   22.69   31.03   24.36    29.7    29.3   27.94   30.75    26.5
   33.52    26.5    35.2    26.5   36.35   26.39   44.17    25.8    51.7   26.39
   53.27   31.19   55.17   31.42   56.19   31.68   80.35   32.74   93.99   33.35
   94.25   33.37   96.78   33.41
#Mann= 3 , 0 , 0
       0    .055       0   36.35    .035       0    51.7    .055       0
Bank Sta=36.35,51.7
XS Rating Curve= 0 ,0
Exp/Cntr=0.5,0.3

Type RM Length L Ch R = 1 ,2240.88 ,28.07,28.63,29.71
XS GIS Cut Line= 2
346143.3950805665422971.15368652346174.0800781255423047.40252686
#Sta/Elev= 18
       0   33.39    2.47   32.05    3.82   31.62    5.96   30.04    10.1      29
   15.69   28.89   18.69   27.59   20.74   27.54   21.67   27.51   25.84   27.01
   40.44   27.68   41.18   27.68   44.11   28.74   49.14   31.22   50.21   31.49
   54.81   31.69   75.39   33.41   82.19   33.95
#Mann= 3 , 0 , 0
       0    .055       0   18.69    .035       0   40.44    .055       0
Bank Sta=18.69,40.44
XS Rating Curve= 0 ,0
Exp/Cntr=0.3,0.1

Type RM Length L Ch R = 1 ,2212.25 ,26.98,28.63,31.48
XS GIS Cut Line= 3
346118.6710815435422981.20568848346135.0164794925423030.85992432
346159.7166748055423043.15087891
#Sta/Elev= 18
       0   34.44    1.82   33.12    8.45   30.58    9.95   29.89   16.22   27.45
   20.27   27.38   20.61   27.37   28.78   26.87   37.72    27.2   38.12   27.19
   38.14   27.19   38.33   27.26    47.8   30.37   51.12   31.57   52.28   31.63
   74.06   32.68    74.7    32.7   79.86   33.06
#Mann= 3 , 0 , 0
       0    .055       0   20.61    .035       0   38.33    .055       0
Bank Sta=20.61,38.33
XS Rating Curve= 0 ,0
Exp/Cntr=0.3,0.1

Type RM Length L Ch R = 1 ,2183.63 ,26.62,19.98,12.38
XS GIS Cut Line= 3
       346094.03      5422987.31      346101.712     5423020.588
      346158.706     5423046.703
#Sta/Elev= 22
       0      37     .93      36    3.27      35    4.79      34    6.64      33
    8.37      32   10.47      31   12.51      30   14.29      29   15.94      28
   17.64      27   19.81   26.35   21.18   26.34   25.47   25.56   29.85   26.51
    31.6      27   34.14      28   41.61      29   50.75      30   60.71      31
   75.37      32   96.84      33
#Mann= 3 , 0 , 0
       0    .055       0   21.18    .035       0   29.85    .055       0
Bank Sta=21.18,29.85
XS Rating Curve= 0 ,0
Exp/Cntr=0.3,0.1

Type RM Length L Ch R = 1 ,2163.63 ,22.26,22,21.26
Node Photo=..\..\..\..\Corner Brook\Windshield Survey\CB photos\P1000674.JPG
XS GIS Cut Line= 4
      345928.344     5422999.821       346002.75     5422995.103
      346045.799     5422996.378      346158.322     5423047.918
#Sta/Elev= 26
       0      35   14.43      34   28.63      33   43.53      32   62.75      31
  112.18      30  121.52      30  144.77      30  146.94      29  148.29      28
  149.59      27  150.41   26.55  153.14   26.11   155.2   25.85  156.19    25.6
   162.9   25.35   166.1   26.24  166.61      27  169.55      28  170.42    28.2
  173.42   28.56  179.55      29  187.81      30   203.9      31  219.01      32
  241.39      33
#Mann= 3 , 0 , 0
       0    .055       0  153.14    .035       0   166.1    .055       0
#XS Ineff= 2 , 0
       0  150.58   30.22   166.6       0   30.69
Permanent Ineff=
       F       F
Bank Sta=153.14,166.1
XS Rating Curve= 0 ,0
Exp/Cntr=0.5,0.3

Type RM Length L Ch R = 3 ,2150    ,,,
Node Photo=..\..\..\Corner Brook\Windshield Survey\CB photos\P1000666.JPG
BEGIN DESCRIPTION:
O'Connell Drive (Structure 2110C)
END DESCRIPTION:
Bridge Culvert--1,0,-1,-1, 0
Deck Dist Width WeirC Skew NumUp NumDn MinLoCord MaxHiCord MaxSubmerge Is_Ogee
2.8,14,1.67,0, 24, 21, 30, , 0.98, 0, 0,0,,
  121.52  141.64  148.18  150.55  150.58  150.59  153.59  153.63  156.59  159.59
  160.05  160.21  162.59  165.59  166.59   166.6  166.93  167.66  169.24  170.83
   179.3  190.38  217.37  241.39
      30   30.22   30.52   30.52   30.52   30.52   30.55   30.55   30.56   30.57
   30.58   30.61   30.61   30.61   30.62   30.63   30.65   30.66   30.69   30.69
      31      32      33      33
                                      24   29.42   29.62   29.63   29.69   29.64
   29.62    29.6   29.42   29.15   29.02      24
                                
   63.59  121.13  129.24  131.89  132.23  132.24  134.88  135.24  138.24  138.43
  141.24  143.24  147.24  148.23  148.24  148.38  150.89  153.03  155.32  162.74
   171.7
      31   30.13   30.46   30.47   30.48   30.48    30.5  30.505   30.51   30.53
   30.54   30.55   30.58   30.59   30.59   30.59    30.6   30.61   30.56   30.49
   30.58
                                      24   29.42   29.59   29.62   29.69   29.69
   29.64   29.57   29.15   29.02      24
        
BR Coef=-1 , 0 , 0 ,, 0 ,,,0.8,-1,,0,
WSPro=,,,, 1 ,,,, 0 ,,,, 0 ,,,,-1 ,-1 ,-1 , 0 , 0 , 0 , 0 , 0
BC Design=,, 0 ,, 0 ,,,,,,
BC Use User HTab Curves=0
BC User HTab FreeFlow(D)= 0

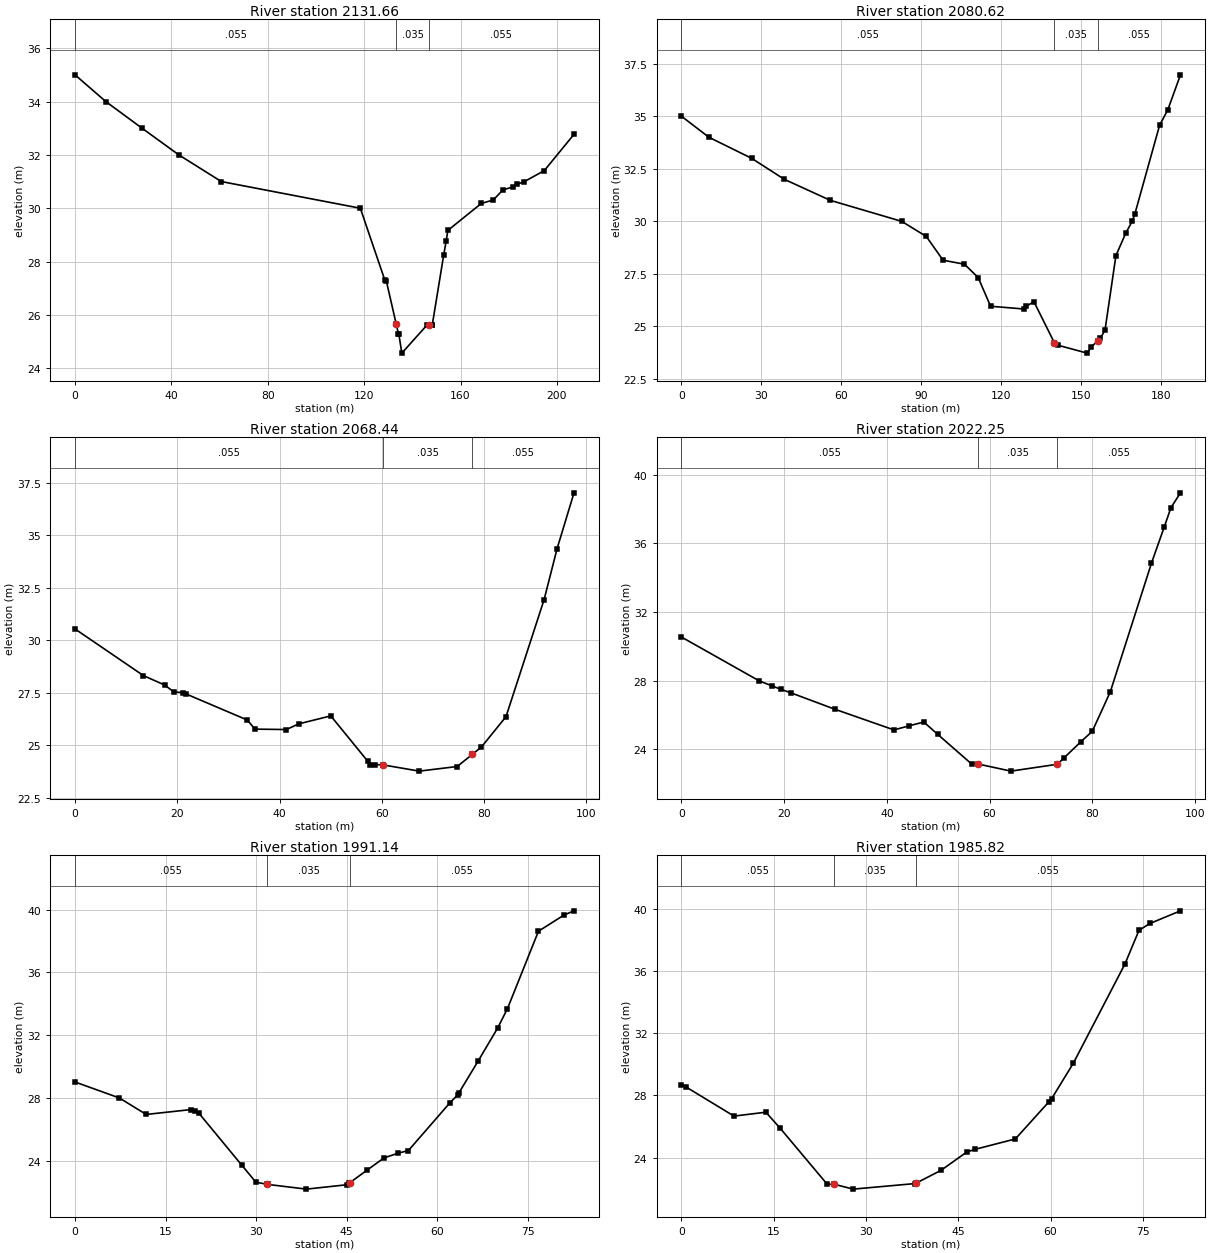
Type RM Length L Ch R = 1 ,2131.66 ,11.18,12.2,13.35
XS GIS Cut Line= 6
       345931.02     5423009.346      346032.623     5423008.449
       346046.82     5423015.244      346046.274     5423017.228
      346046.445     5423027.265      346109.389     5423072.259
#Sta/Elev= 27
       0      35   12.77      34   27.81      33   43.09      32   60.74      31
  118.41      30   128.6    27.3  129.24   27.26  133.32  25.651  134.21    25.3
  134.39   25.28  135.63   24.57  145.96   25.61   146.8   25.62  148.21   25.63
  148.29   25.64  153.03   28.26  154.04   28.78  154.75   29.17  168.61   30.18
  173.58   30.31  177.62   30.69   181.8    30.8  183.46    30.9   186.3   30.99
  194.75   31.41  207.08   32.77
#Mann= 3 , 0 , 0
       0    .055       0  133.32    .035       0   146.8    .055       0
Bank Sta=133.32,146.8
XS Rating Curve= 0 ,0
Exp/Cntr=0.3,0.1

Type RM Length L Ch R = 1 ,2080.62 ,7.82,12.17,17.26
XS GIS Cut Line= 6
      345930.185     5423010.828      346011.495     5423009.672
      346011.251     5423027.508      346009.591     5423057.665
      346035.995      5423087.37      346032.374     5423105.315
#Sta/Elev= 28
       0      35   10.31      34   26.33      33   38.62      32   55.87      31
    82.7      30   91.97   29.28   98.25   28.15   106.3   27.96  111.46   27.32
   116.1   25.96  128.59   25.83  129.56   25.97  132.41   26.17  140.04   24.23
   141.3   24.11  152.37   23.73  153.95   24.03  156.53   24.33  157.34   24.43
   159.1   24.84  163.18   28.37  166.91   29.45  169.37   30.02  170.31   30.36
  179.58   34.57  182.68   35.31  187.42   36.97
#Mann= 3 , 0 , 0
       0    .055       0  140.04    .035       0  156.53    .055       0
Bank Sta=140.04,156.53
XS Rating Curve= 0 ,0
Exp/Cntr=0.3,0.1

Type RM Length L Ch R = 1 ,2068.44 ,33.61,46.19,57.27
XS GIS Cut Line= 3
345989.7929077155423013.86950684345994.8095092775423035.04589844
346022.6514892585423105.56347656
#Sta/Elev= 23
       0   30.53   13.37   28.31   17.52   27.86   19.34   27.53   21.14    27.5
   21.76   27.43   33.72   26.19   35.17   25.76   41.34   25.74   43.75   26.01
   50.02   26.39   57.22   24.24   57.73   24.06    58.7   24.07   60.17   24.06
   67.32   23.76   74.74   23.98   77.71   24.56   79.48   24.91   84.28   26.35
   91.74   31.93   94.27   34.35   97.58   37.01
#Mann= 3 , 0 , 0
       0    .055       0   60.17    .035       0   77.71    .055       0
Bank Sta=60.17,77.71
XS Rating Curve= 0 ,0
Exp/Cntr=0.3,0.1

Type RM Length L Ch R = 1 ,2022.25 ,34.56,31.11,28.31
XS GIS Cut Line= 3
345989.0667114265423013.80352783 345989.132690435423031.48352051
345953.182128906 5423102.3637085
#Sta/Elev= 22
       0   30.55   15.18   27.99   17.68    27.7   19.31   27.51   21.32    27.3
   29.82   26.35   41.38   25.14   44.34   25.38   47.19    25.6   49.86   24.89
   56.52   23.15   57.83   23.15   64.14   22.74   73.19   23.14   74.41   23.49
   77.73   24.44   79.99   25.06    83.5   27.36   91.52   34.86   93.99   36.95
   95.31   38.09   97.16   38.95
#Mann= 3 , 0 , 0
       0    .055       0   57.83    .035       0   73.19    .055       0
Bank Sta=57.83,73.19
XS Rating Curve= 0 ,0
Exp/Cntr=0.3,0.1

Type RM Length L Ch R = 1 ,1991.14 ,4.99,5.33,3.98
XS GIS Cut Line= 6
 345950.168090825423025.80169678345943.0416870125423044.42907715
345942.630493164 5423052.0993042 345935.503906255423071.68548584
345933.8593139655423076.47930908345943.4526977545423104.00952148
#Sta/Elev= 27
       0   29.01    7.36   27.99    11.8   26.94    19.2   27.25   19.94   27.15
   20.51   27.03   27.63   23.71   29.98   22.62   31.83   22.49   31.94   22.48
   38.35   22.18   45.08   22.46   45.34   22.54   45.58    22.6   48.47   23.41
   51.21   24.17   53.54   24.47   55.25   24.64    62.1   27.67   63.45    28.2
   63.58   28.29   66.78   30.33   70.04   32.45   71.67   33.69    76.8   38.62
   81.03   39.65   82.69   39.92
#Mann= 3 , 0 , 0
       0    .055       0   31.83    .035       0   45.58    .055       0
Bank Sta=31.83,45.58
XS Rating Curve= 0 ,0
Exp/Cntr=0.3,0.1

Type RM Length L Ch R = 1 ,1985.82 ,9.55,9.86,16.12
XS GIS Cut Line= 3
345943.615112305 5423029.6887207345929.5490722665423075.29351807
345939.5516967775423107.15447998
#Sta/Elev= 21
       0   28.66     .72   28.55    8.54   26.67   13.72   26.92   15.98   25.92
    23.7   22.28   24.86   22.28   27.92   21.97   38.04   22.33   38.17   22.36
    42.2   23.18   46.39   24.36   47.72   24.53   54.28    25.2   59.76    27.6
   60.16   27.78    63.7   30.07   72.11   36.47   74.38   38.63   76.18   39.07
   81.12   39.88
#Mann= 3 , 0 , 0
       0    .055       0   24.86    .035       0   38.17    .055       0
Bank Sta=24.86,38.17
XS Rating Curve= 0 ,0
Exp/Cntr=0.3,0.1

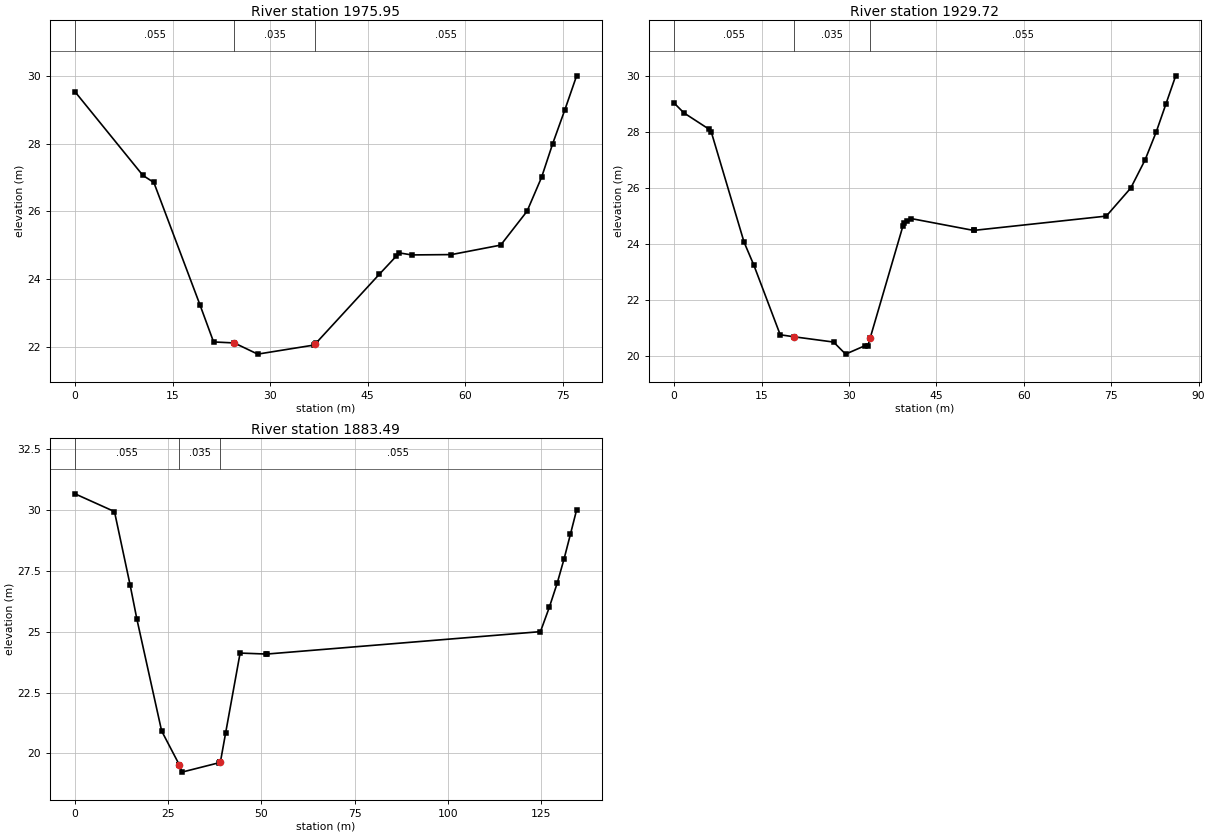
Type RM Length L Ch R = 1 ,1975.95 ,52.27,46.23,29.18
XS GIS Cut Line= 4
      345935.646     5423026.368      345916.273     5423080.885
      345922.939     5423084.477      345929.488     5423094.137
#Sta/Elev= 21
       0   29.53   10.43   27.06   12.12   26.85    19.2   23.24    21.3   22.14
   24.49   22.11   28.08   21.78    36.8   22.05   36.89   22.07   37.07   22.11
   46.78   24.14   49.41   24.68   49.86   24.77   51.74   24.71   57.86   24.72
   65.43      25   69.48      26   71.71      27   73.43      28    75.3      29
    77.1      30
#Mann= 3 , 0 , 0
       0    .055       0   24.49    .035       0   36.89    .055       0
Bank Sta=24.49,36.89
XS Rating Curve= 0 ,0
Exp/Cntr=0.3,0.1

Type RM Length L Ch R = 1 ,1929.72 ,44.45,46.23,49.08
XS GIS Cut Line= 3
      345870.248     5423037.994      345892.961      5423084.11
      345924.694     5423098.062
#Sta/Elev= 25
       0   29.03    1.68   28.68    6.05   28.09    6.41   27.98   12.01   24.07
   13.69   23.25   18.21   20.77   20.52    20.7   27.37   20.51   29.43   20.08
   32.75   20.38   33.26   20.38   33.66  20.664   39.27   24.65   39.41   24.74
   39.92   24.81   40.73   24.91   51.38   24.49   51.41   24.49   74.16      25
   78.36      26   80.81      27   82.73      28    84.4      29   86.07      30
#Mann= 3 , 0 , 0
       0    .055       0   20.52    .035       0   33.66    .055       0
Bank Sta=20.52,33.66
XS Rating Curve= 0 ,0
Exp/Cntr=0.3,0.1

Type RM Length L Ch R = 1 ,1883.49 ,70.29,57.09,46.34
XS GIS Cut Line= 5
      345828.559     5423042.591      345831.718      5423053.53
      345842.662     5423091.804       345887.72     5423086.365
      345922.318     5423102.044
#Sta/Elev= 22
       0   30.66   10.59   29.93   14.78   26.92   16.62    25.5   23.24   20.92
   27.95   19.54   27.98   19.53   28.02   19.53   28.69   19.23   38.76   19.62
   38.82   19.63   39.01   19.65   40.41   20.84   44.29   24.12   51.24   24.08
   51.49   24.08  124.86      25  127.24      26  129.37      27  131.22      28
   132.9      29  134.56      30
#Mann= 3 , 0 , 0
       0    .055       0   28.02    .035       0   38.82    .055       0
Bank Sta=28.02,38.82
XS Rating Curve= 0 ,0
Exp/Cntr=0.3,0.1

River Reach=CornerB         ,TR002

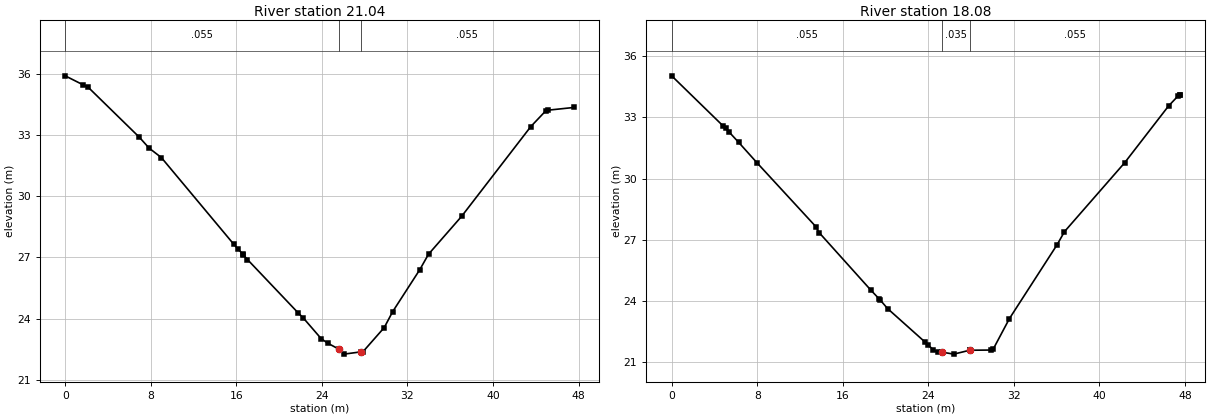
Type RM Length L Ch R = 1 ,21.04   ,2.92,2.96,3.06
XS GIS Cut Line= 4
345758.1389160165423067.02331543345780.1409301765423076.43328857
345785.6174926765423074.22491455345783.5037231455423056.65307617
#Sta/Elev= 28
       0   35.89    1.67   35.45    2.13   35.34    6.94   32.88    7.85   32.35
    8.99   31.89   15.74   27.66   16.15   27.42   16.61   27.16   16.63   27.14
   17.04    26.9   21.76    24.3   22.28   24.03   23.93   23.03   24.53   22.81
   25.64    22.5   26.07   22.27   27.64   22.38   27.83   22.38   29.83   23.57
   30.62   24.35   33.15    26.4   33.97   27.16   37.06   29.01   43.54   33.41
   44.94   34.18   45.17   34.21   47.53   34.34
#Mann= 3 , 0 , 0
       0    .055       0   25.64    .035       0   27.64    .055       0
Bank Sta=25.64,27.64
XS Rating Curve= 0 ,0
Exp/Cntr=0.3,0.1

Type RM Length L Ch R = 1 ,18.08   ,6.77,18.08,0.34
XS GIS Cut Line= 4
345759.7786865235423069.50152588345781.7808837895423078.91149902
345787.257324219  5423076.703125345785.1434936525423059.13110352
#Sta/Elev= 30
       0   35.03    4.82   32.57    5.09   32.46    5.33    32.3    6.25   31.78
    7.98   30.77   13.47   27.65   13.79   27.35   18.63   24.53   19.41    24.1
    19.5   24.05   20.19   23.63   23.65   22.01   23.93   21.87   24.47   21.61
   24.86   21.49   25.24    21.5   26.38    21.4   27.86   21.59   27.91   21.59
   29.83    21.6   30.08   21.66   31.58   23.14   36.04   26.76   36.73    27.4
   42.35   30.77   46.47   33.56   47.36   34.05    47.5   34.08   47.53   34.08
#Mann= 3 , 0 , 0
       0    .055       0   25.24    .035       0   27.91    .055       0
Bank Sta=25.24,27.91
XS Rating Curve= 0 ,0
Exp/Cntr=0.3,0.1

River Reach=CornerB         ,M002

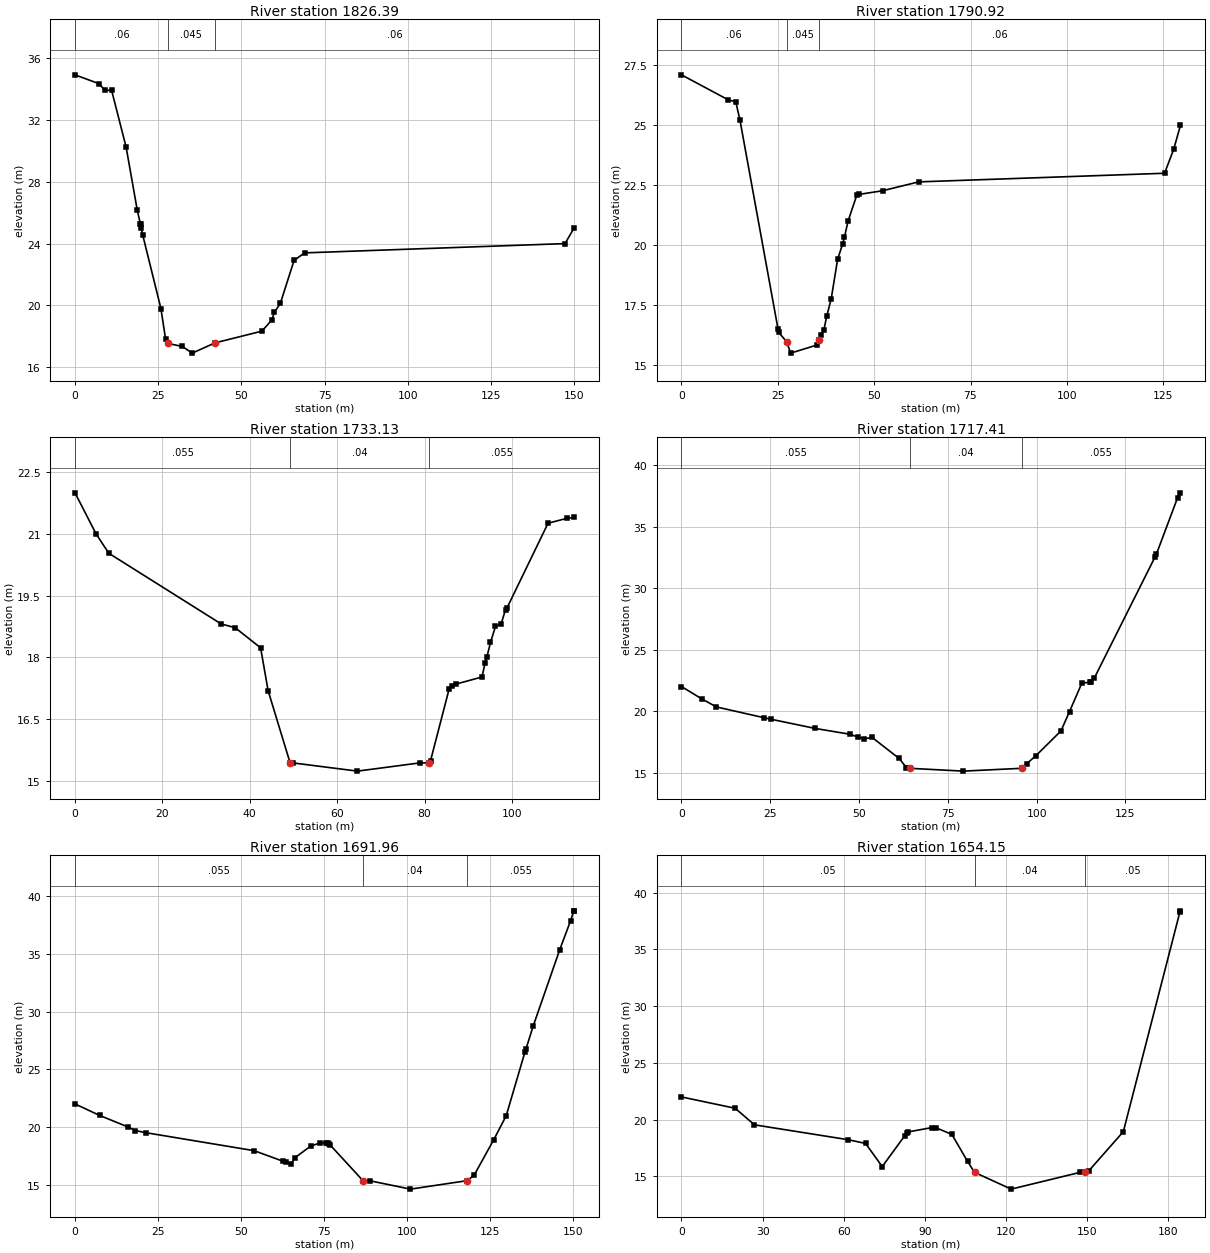
Type RM Length L Ch R = 1 ,1826.39 ,40.26,35.47,34.01
XS GIS Cut Line= 5
      345754.172     5423081.877      345765.677     5423088.757
      345824.044     5423120.836      345878.652     5423132.582
      345891.045     5423139.228
#Sta/Elev= 24
       0   34.91    7.29   34.33    8.92   33.91      11   33.91   15.37   30.23
   18.72   26.15   19.64   25.28   19.75   25.24    19.9      25   20.32   24.58
   25.82    19.8   27.23   17.81   27.87   17.55   32.24   17.35   35.24   16.92
   42.03   17.58   56.14   18.34   59.14   19.06   59.88   19.55   61.69   20.13
   65.82   22.91   68.98    23.4  147.23      24  149.93      25
#Mann= 3 , 0 , 0
       0     .06       0   27.87    .045       0   42.03     .06       0
Bank Sta=27.87,42.03
XS Rating Curve= 0 ,0
Exp/Cntr=0.3,0.1

Type RM Length L Ch R = 1 ,1790.92 ,18.6,16.77,13.53
XS GIS Cut Line= 6
      345751.702     5423127.865      345761.429     5423135.042
      345791.135     5423135.505      345810.069     5423129.948
      345861.119     5423157.051      345869.281     5423163.092
#Sta/Elev= 25
       0   27.11   12.09   26.07    14.1   25.98   15.19   25.21   25.04   16.51
   25.21   16.36   27.26   15.97   28.35   15.49   35.18   15.83   35.63   16.02
   36.21   16.26   36.94   16.45   37.68   17.02   38.86   17.76   40.51    19.4
    41.8   20.04   42.27   20.32   43.25   21.01    45.5   22.09   46.19   22.12
   52.19   22.27   61.53   22.64  125.35      23  127.72      24  129.48      25
#Mann= 3 , 0 , 0
       0     .06       0   27.26    .045       0   35.63     .06       0
Bank Sta=27.26,35.63
XS Rating Curve= 0 ,0
Exp/Cntr=0.3,0.1

Type RM Length L Ch R = 1 ,1733.13 ,16.21,15.72,15.8
XS GIS Cut Line= 5
      345746.741     5423185.349       345751.59     5423191.382
      345774.408     5423203.252      345827.859     5423175.139
      345841.612     5423160.146
#Sta/Elev= 28
       0      22    4.83      21    7.74   20.53   33.46   18.81   36.64   18.72
   42.48   18.23   44.19   17.19   49.23   15.43   49.39   15.43   49.87   15.43
   64.64   15.23    78.9   15.43   81.07   15.43   81.36   15.48   85.65   17.24
    86.3    17.3   87.28   17.35   93.14   17.52   93.85   17.86   94.25      18
   95.09   18.36   96.23   18.75   97.52   18.81   98.53   19.16   98.87    19.2
  108.26   21.26  112.57   21.38   114.2    21.4
#Mann= 3 , 0 , 0
       0    .055       0   49.23     .04       0   81.07    .055       0
Bank Sta=49.23,81.07
XS Rating Curve= 0 ,0
Exp/Cntr=0.3,0.1

Type RM Length L Ch R = 1 ,1717.41 ,25.46,25.45,26.11
XS GIS Cut Line= 5
      345737.376      5423200.53      345747.104      5423202.08
      345784.369     5423216.364      345841.542     5423184.989
      345865.534     5423193.662
#Sta/Elev= 28
       0      22    5.68      21    9.85   20.34   23.29   19.46    25.2   19.34
   37.66   18.59   47.43   18.12   49.76   17.88   51.48   17.74   53.63   17.87
   61.28   16.15   63.35   15.41   64.06   15.35   64.26   15.35   79.34   15.12
   95.77   15.35   97.27   15.74   99.85   16.39  106.85   18.39  109.25   19.96
  112.76    22.3  114.98   22.33  115.37   22.33  116.22   22.68  133.31   32.52
  133.71   32.76  139.66   37.34  140.49   37.75
#Mann= 3 , 0 , 0
       0    .055       0   64.26     .04       0   95.77    .055       0
Bank Sta=64.26,95.77
XS Rating Curve= 0 ,0
Exp/Cntr=0.3,0.1

Type RM Length L Ch R = 1 ,1691.96 ,32.19,37.81,37.44
XS GIS Cut Line= 5
      345731.341     5423213.631      345734.047      5423218.83
      345745.026     5423224.492      345795.976     5423238.237
      345866.305      5423201.69
#Sta/Elev= 30
       0      22    7.43      21   15.98      20   18.21   19.69   21.48    19.5
   53.93   17.95   62.77   17.02   63.44   16.97   65.14   16.78   66.12   17.32
   70.98   18.35   73.88   18.63   75.68   18.65    76.1   18.63   76.53   18.55
   76.77   18.46   86.71   15.35   88.69   15.35  100.99   14.62  117.99   15.35
  120.14   15.81  126.06   18.89  129.82   20.97   135.5   26.52   135.8   26.77
  137.95   28.74  145.88    35.3  149.21   37.86  150.21   38.72  150.24   38.72
#Mann= 3 , 0 , 0
       0    .055       0   86.71     .04       0  117.99    .055       0
Bank Sta=86.71,117.99
XS Rating Curve= 0 ,0
Exp/Cntr=0.3,0.1

Type RM Length L Ch R = 1 ,1654.15 ,26.43,40.25,54.75
XS GIS Cut Line= 6
      345711.988     5423231.515       345719.48      5423238.17
      345731.897     5423242.609      345802.852     5423264.787
      345827.233     5423263.538      345883.185     5423235.425
#Sta/Elev= 21
       0      22   19.87      21      27   19.54    61.6   18.23    68.1    17.9
   74.26   15.86   82.52   18.55   83.58   18.79   83.79   18.91   92.69    19.3
   94.23   19.27  100.02    18.7  105.81   16.32   108.4   15.35  121.96   13.87
  147.46   15.35  149.16   15.35  150.78   15.51  163.45   18.94  184.39   38.33
  184.58   38.41
#Mann= 3 , 0 , 0
       0     .05       0   108.4     .04       0  149.16     .05       0
Bank Sta=108.4,149.16
XS Rating Curve= 0 ,0
Exp/Cntr=0.3,0.1

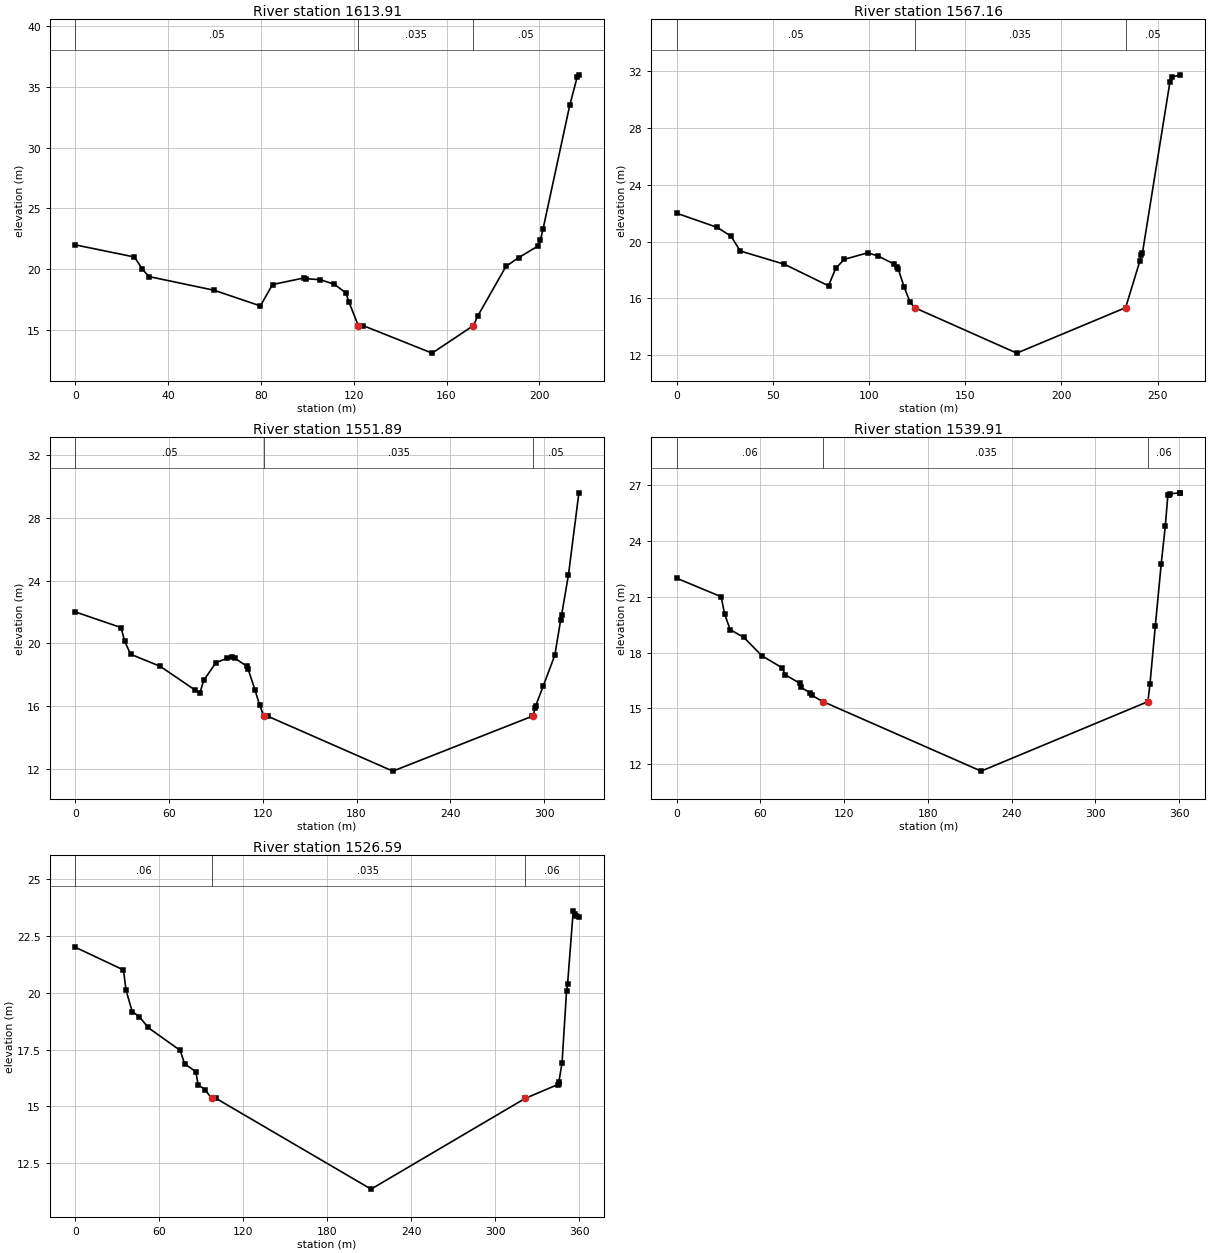
Type RM Length L Ch R = 1 ,1613.91 ,6.28,46.75,75.1
XS GIS Cut Line= 6
      345709.491     5423233.179      345716.566     5423245.864
      345797.852     5423280.216      345809.417     5423298.021
      345882.872     5423308.954      345901.002     5423308.017
#Sta/Elev= 26
       0      22   25.51      21   28.94      20   31.72   19.39   59.84   18.26
   79.77   16.97      85   18.73    98.7   19.28    99.5   19.21   105.6   19.13
  111.57   18.76  116.56   18.05     118   17.26  121.95   15.35  124.02   15.35
  153.76   13.08  171.58   15.35  173.37   16.12  185.61   20.23     191   20.94
  199.51   21.92  200.42   22.36  201.59   23.33  213.08   33.51  216.25   35.81
  217.01   36.01
#Mann= 3 , 0 , 0
       0     .05       0  121.95    .035       0  171.58     .05       0
Bank Sta=121.95,171.58
XS Rating Curve= 0 ,0
Exp/Cntr=0.3,0.1

Type RM Length L Ch R = 1 ,1567.16 ,8.5,15.27,80.02
XS GIS Cut Line= 6
      345707.826     5423234.219       345715.11     5423247.112
      345796.942     5423284.288      345803.506     5423302.093
      345825.699     5423371.437      345890.402     5423379.871
#Sta/Elev= 24
       0      22   21.14      21   28.31   20.38   33.07   19.34   55.97   18.41
   78.96   16.89   82.71   18.12   87.13   18.75   99.33   19.21  104.69   18.99
  113.13   18.41  114.66    18.2  115.15   18.09  118.29   16.79  121.24   15.77
  123.67   15.35  176.78   12.15  233.35   15.35  240.76   18.64   241.4   19.04
   242.1   19.21  256.35   31.22  257.21   31.57  261.73   31.74
#Mann= 3 , 0 , 0
       0     .05       0  123.67    .035       0  233.35     .05       0
Bank Sta=123.67,233.35
XS Rating Curve= 0 ,0
Exp/Cntr=0.3,0.1

Type RM Length L Ch R = 1 ,1551.89 ,13.15,11.97,90.06
XS GIS Cut Line= 6
      345705.745     5423234.427      345713.445      5423248.36
      345727.212     5423255.882      345791.603     5423284.932
      345815.984     5423441.425      345874.115     5423461.906
#Sta/Elev= 29
       0      22   29.32      21   31.61   20.14   35.45    19.3   54.38   18.53
    76.5   17.03   79.77   16.83   82.24   17.64   90.01   18.76   97.09   19.04
  100.63   19.13  102.25   19.04  109.62   18.55  110.54   18.38   115.1      17
  117.95   16.07  120.71   15.35   123.2   15.35  203.24   11.85  292.43   15.35
  292.96   15.35  294.22   15.85  294.64   16.01  299.44   17.27  306.87   19.24
  310.57   21.46  311.19   21.79  315.59   24.36  322.27   29.59
#Mann= 3 , 0 , 0
       0     .05       0  120.71    .035       0  292.96     .05       0
Bank Sta=120.71,292.96
XS Rating Curve= 0 ,0
Exp/Cntr=0.3,0.1

Type RM Length L Ch R = 1 ,1539.91 ,10.59,13.32,74.85
XS GIS Cut Line= 6
      345703.248     5423234.634      345711.364     5423248.984
      345783.516     5423300.208      345800.708      5423444.52
      345799.119     5423503.467      345823.812     5423548.759
#Sta/Elev= 27
       0      22   31.96      21   34.39   20.08   38.39   19.23   48.26   18.81
   61.04   17.83   75.82   17.17   77.71   16.81   88.41   16.34      89   16.13
   95.72   15.83   96.71   15.71  104.98   15.35  105.21   15.35  218.21   11.62
  337.43   15.35  337.56   15.35  337.69   15.35  339.18   16.31  342.97    19.4
  347.23   22.77  350.14   24.78  352.02   26.49  353.08    26.5   353.2   26.53
  360.53   26.59  360.86   26.59
#Mann= 3 , 0 , 0
       0     .06       0  104.98    .035       0  337.69     .06       0
Bank Sta=104.98,337.69
XS Rating Curve= 0 ,0
Exp/Cntr=0.3,0.1

Type RM Length L Ch R = 1 ,1526.59 ,11.14,8.6,95.57
XS GIS Cut Line= 6
      345701.999      5423235.05      345709.699     5423250.231
      345769.716     5423296.429      345784.723     5423416.258
      345742.212     5423553.073      345740.337     5423555.259
#Sta/Elev= 26
       0      22   34.44      21   36.29   20.11   40.73   19.16   45.79   18.95
   51.96   18.47   74.97   17.46   78.06   16.88   86.17   16.52    87.7   15.96
   92.79   15.73   97.37   15.35   97.63   15.35  100.58   15.35  211.29   11.36
  321.32   15.35  344.66   15.96  345.16   15.99  345.31   16.05  347.65    16.9
  350.89   20.07  351.64   20.39  355.65    23.6  356.82   23.48  357.97   23.36
   359.7   23.33
#Mann= 3 , 0 , 0
       0     .06       0   97.37    .035       0  321.32     .06       0
Bank Sta=97.37,321.32
XS Rating Curve= 0 ,0
Exp/Cntr=0.3,0.1