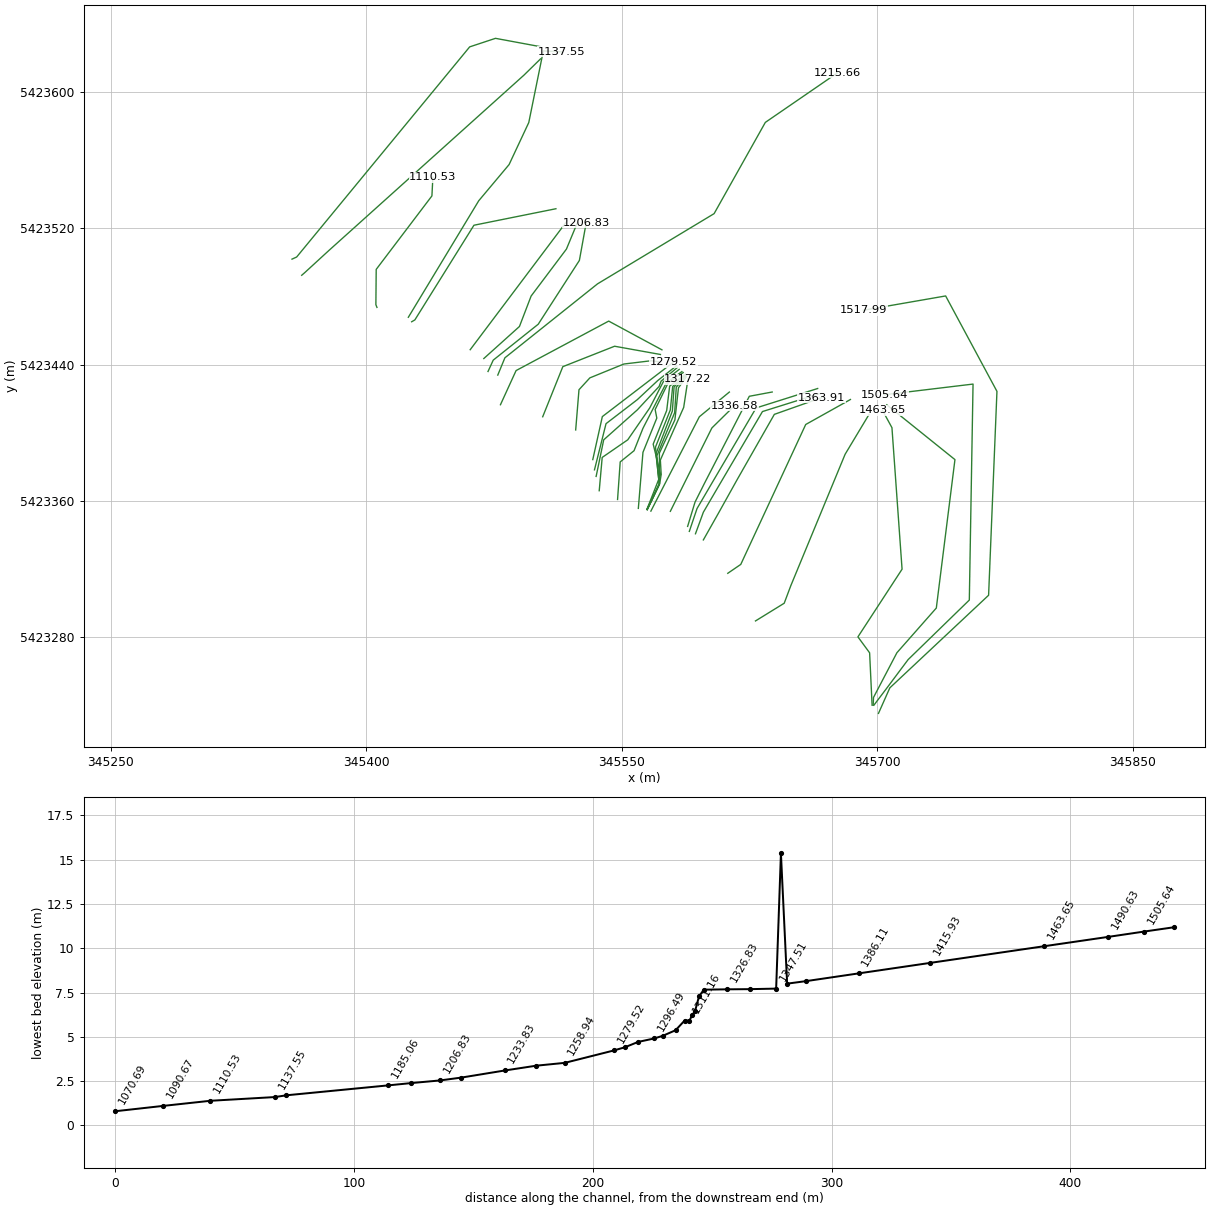
HEC-RAS study Corner_Brook2.prj: Corner_Brook2

--- Corner_Brook2.g03 (geometry) --- (continued)

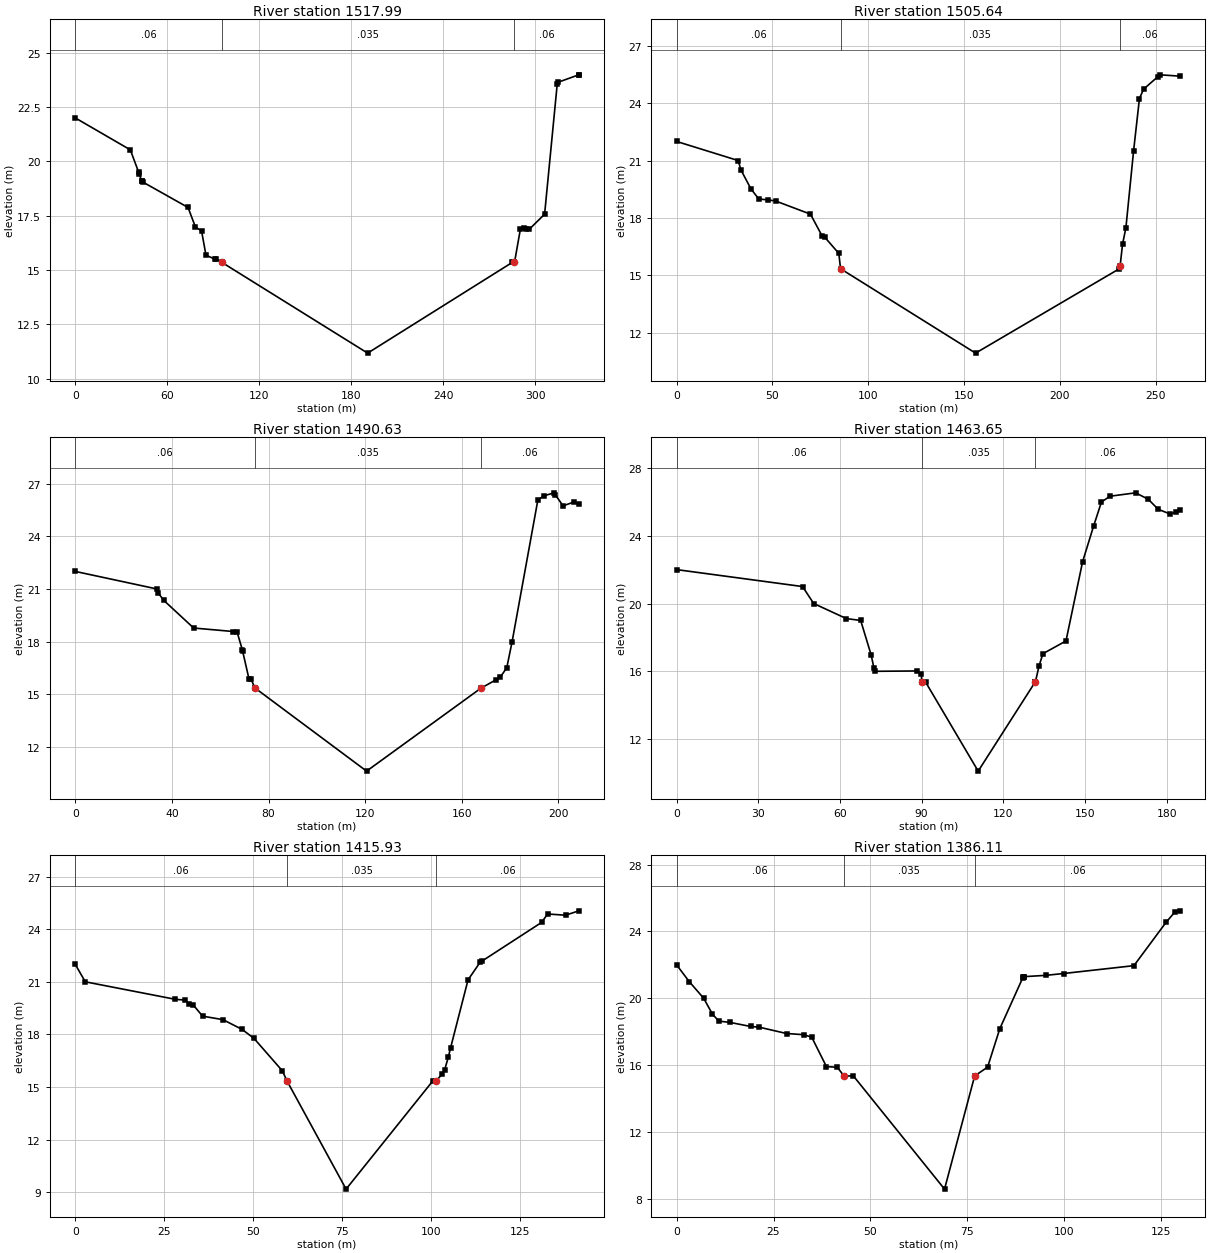
Type RM Length L Ch R = 1 ,1517.99 ,8.97,12.35,53.09
XS GIS Cut Line= 6
      345700.751     5423235.258       345707.41     5423250.231
      345765.412     5423304.612      345770.316     5423424.349
      345740.189     5423480.365      345691.846     5423471.963
#Sta/Elev= 26
       0      22   35.92   20.53   41.42   19.49   41.78   19.41   43.27    19.1
    43.8   19.08   44.29   19.04   73.55   17.88   78.38   16.98   82.38    16.8
   85.26   15.68   91.31    15.5   92.02    15.5   95.71   15.35  190.67   11.18
  284.92   15.35  286.42   15.35  290.33   16.91  292.72   16.95  293.67   16.89
  295.97   16.87  306.05   17.57  314.29   23.56  314.92   23.64  328.31   23.98
  328.41   23.98
#Mann= 3 , 0 , 0
       0     .06       0   95.71    .035       0  286.42     .06       0
Bank Sta=95.71,286.42
XS Rating Curve= 0 ,0
Exp/Cntr=0.3,0.1

Type RM Length L Ch R = 1 ,1505.64 ,15.22,15.01,28.16
XS GIS Cut Line= 6
      345698.045     5423240.041      345705.745     5423250.231
      345718.144     5423266.817      345754.091     5423301.802
      345756.279      5423428.62      345704.391     5423422.373
#Sta/Elev= 23
       0      22   32.17      21   33.48   20.53   38.81   19.52    42.9   18.99
   47.47   18.95   51.63   18.89   69.86    18.2   75.98   17.05   77.36   16.99
   84.64   16.15   85.54   15.35  155.98   10.94     231   15.35  231.39    15.5
  232.63   16.62  234.41    17.5  238.41   21.51  241.46   24.24  243.61   24.73
  250.92   25.37  252.26   25.48  262.74   25.41
#Mann= 3 , 0 , 0
       0     .06       0   85.54    .035       0  231.39     .06       0
Bank Sta=85.54,231.39
XS Rating Curve= 0 ,0
Exp/Cntr=0.3,0.1

Type RM Length L Ch R = 1 ,1490.63 ,32.16,26.98,34.14
XS GIS Cut Line= 6
      345697.629     5423240.041      345697.837     5423244.616
      345711.583     5423270.875      345734.714     5423297.114
      345745.654     5423384.263      345705.644     5423416.436
#Sta/Elev= 26
       0      22   33.86      21   34.22    20.8   36.59   20.36   49.01   18.78
    65.5   18.58   66.97   18.56    69.2   17.52   69.29   17.46    71.9   15.89
   72.74   15.88   74.43   15.35   74.57   15.35  120.58   10.64  167.82   15.35
  174.19   15.84  175.88   15.98  178.59   16.52   180.8      18  191.47   26.07
  193.99    26.3  198.13   26.47  198.72   26.35   201.9   25.73  206.22   25.94
  208.44   25.82
#Mann= 3 , 0 , 0
       0     .06       0   74.43    .035       0  167.82     .06       0
Bank Sta=74.43,167.82
XS Rating Curve= 0 ,0
Exp/Cntr=0.3,0.1

Type RM Length L Ch R = 1 ,1463.65 ,55.26,47.71,36.96
XS GIS Cut Line= 6
      345697.005     5423240.041      345695.548     5423270.819
      345688.681     5423280.177      345714.601     5423319.919
      345708.662     5423403.008      345703.035     5423413.315
#Sta/Elev= 28
       0      22   46.26      21   50.35      20   62.35   19.11   67.61      19
   71.41   16.99   72.49   16.19   72.85      16    88.2   16.02   89.92   15.84
      90   15.35    91.5   15.35  110.76   10.11  131.62   15.35  131.74   15.35
  133.11   16.32  134.55   17.04     143   17.79   149.1   22.46  153.11   24.55
  156.03   25.99  159.19   26.33  168.58   26.53  173.22   26.15  176.86   25.56
  181.09   25.29  183.39   25.37  184.96    25.5
#Mann= 3 , 0 , 0
       0     .06       0      90    .035       0  131.74     .06       0
Bank Sta=90,131.74
XS Rating Curve= 0 ,0
Exp/Cntr=0.3,0.1

Type RM Length L Ch R = 1 ,1415.93 ,31.39,29.83,29.88
XS GIS Cut Line= 5
       345628.54     5423289.535      345645.396     5423299.933
      345649.272     5423310.236      345681.155      5423387.39
      345695.221     5423410.817
#Sta/Elev= 26
       0      22    2.83      21   28.16      20   30.81   19.96   32.11   19.76
   33.18   19.68   35.81   19.04   41.55   18.84   46.95   18.28   50.27   17.77
   58.24   15.92   59.53   15.35   76.16    9.17  100.57   15.35   101.5   15.35
  103.11   15.72  103.85   15.96  104.89   16.69  105.54   17.23  110.45   21.11
  113.83   22.11  114.29   22.17  131.14   24.39  132.82   24.87  137.86    24.8
  141.62   25.05
#Mann= 3 , 0 , 0
       0     .06       0   59.53    .035       0   101.5     .06       0
Bank Sta=59.53,101.5
XS Rating Curve= 0 ,0
Exp/Cntr=0.3,0.1

Type RM Length L Ch R = 1 ,1386.11 ,24.24,22.2,21.91
Node Photo=..\..\..\Corner Brook\Windshield Survey\CB photos\P1000657.JPG
XS GIS Cut Line= 4
      345612.263     5423317.512       345619.89     5423322.731
      345658.024     5423404.882      345684.281     5423419.563
#Sta/Elev= 29
       0      22    3.25      21    6.99      20    9.25   19.05   10.91   18.63
   13.67   18.56   19.12   18.31    21.3   18.27   28.36   17.89   32.79   17.82
   34.86   17.67   38.65   15.91   41.46   15.87   43.18   15.35   45.61   15.35
   69.11    8.58   76.88   15.35   80.22   15.88   83.35   18.17   89.26   21.21
   89.37   21.28    89.5   21.29   89.51   21.29   95.23   21.37   99.82   21.48
  117.96   21.95  126.24   24.54  128.52   25.16   129.9   25.23
#Mann= 3 , 0 , 0
       0     .06       0   43.18    .035       0   76.88     .06       0
Bank Sta=43.18,76.88
XS Rating Curve= 0 ,0
Exp/Cntr=0.3,0.1

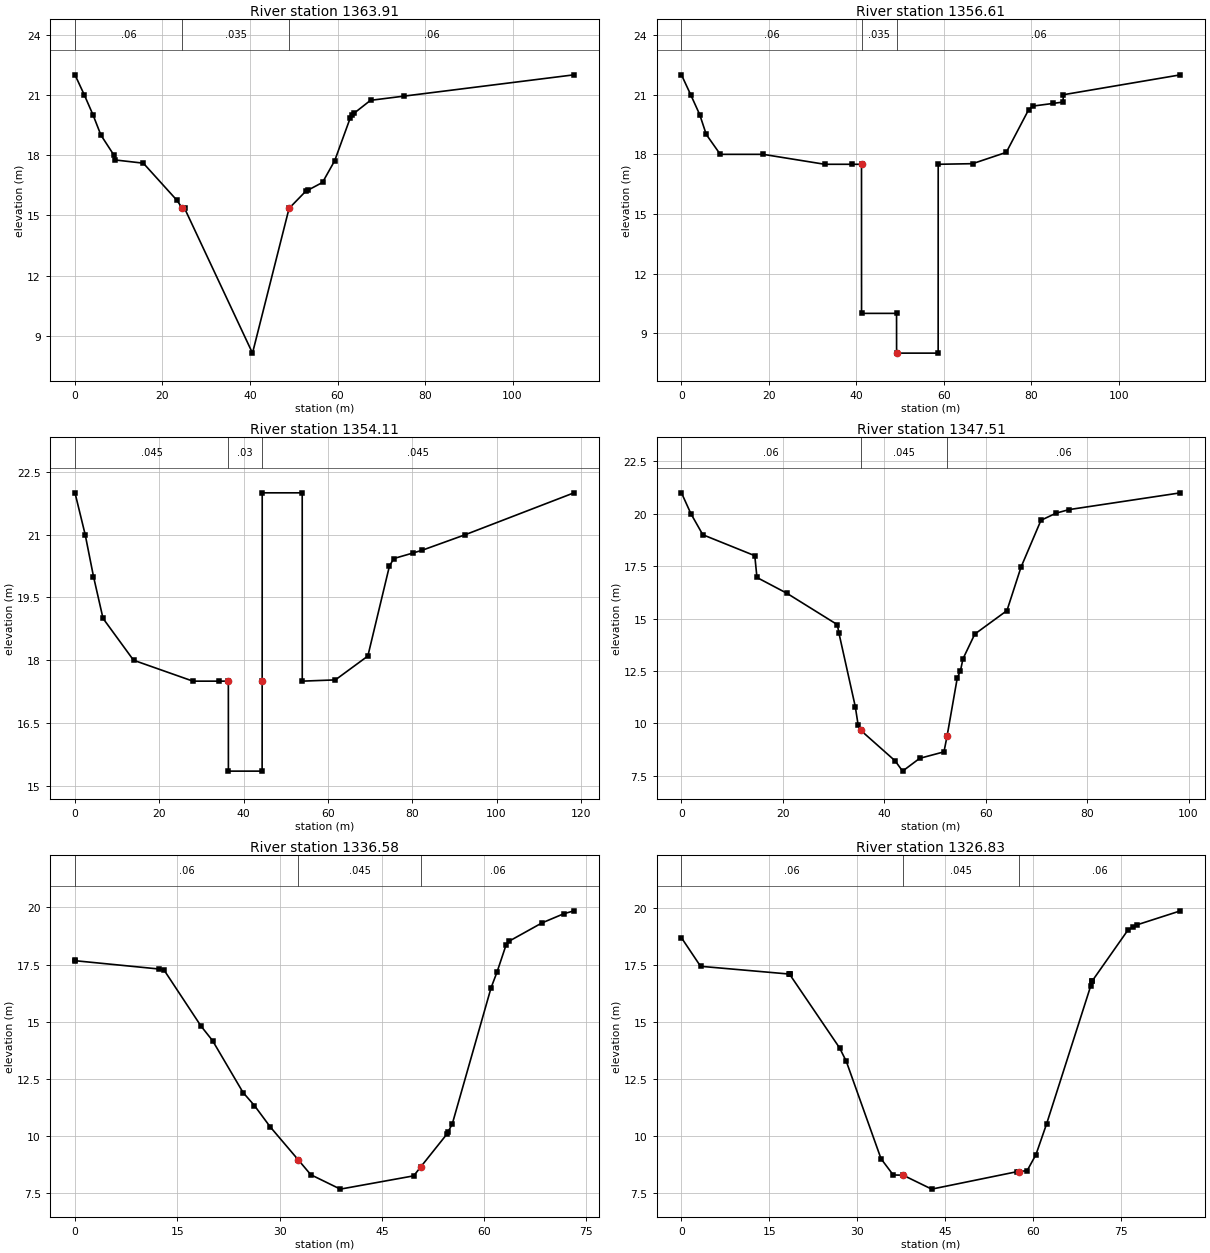
Type RM Length L Ch R = 1 ,1363.91 ,8.1,7.8,10.76
Node Photo=..\..\..\Corner Brook\Windshield Survey\CB photos\P1000652.JPG
XS GIS Cut Line= 5
       345597.92     5423337.105      345607.093     5423353.359
      345617.952     5423372.843      345639.601     5423410.833
      345667.279     5423420.628
#Sta/Elev= 22
       0      22    2.13      21    4.13      20    5.92      19     8.9      18
    9.19   17.76   15.62    17.6   23.26   15.76   24.55   15.35   25.05   15.35
   40.57    8.14   48.93   15.35   52.82   16.22   53.28   16.26   56.57   16.64
   59.35   17.72   62.94   19.87   63.28   20.02    63.8   20.09   67.54   20.73
   75.22   20.94  114.05      22
#Mann= 3 , 0 , 0
       0     .06       0   24.55    .035       0   48.93     .06       0
Bank Sta=24.55,48.93
XS Rating Curve= 0 ,0
Exp/Cntr=0.3,0.1

Type RM Length L Ch R = 1 ,1356.61 ,2.6,2.6,2.6
Node Photo=..\..\..\Corner Brook\Windshield Survey\CB photos\P1000651.JPG
BEGIN DESCRIPTION:
immediately downstream of Glynmill Dam
END DESCRIPTION:
XS GIS Cut Line= 5
      345593.298      5423340.72      345597.934     5423353.398
      345606.261     5423367.638       345632.63     5423412.484
      345666.152     5423422.998
#Sta/Elev= 22
       0      22    2.11      21    4.17      20    5.67      19    8.87      18
   18.66      18   32.75    17.5   39.04    17.5   41.15    17.5   41.16      10
   49.16      10   49.17       8   58.67       8   58.68    17.5   66.53   17.53
   74.24    18.1   79.36   20.25    80.4   20.43   84.88   20.56   87.18   20.63
   87.31      21  114.05      22
#Mann= 3 , 0 , 0
       0     .06       0   41.15    .035       0   49.17     .06       0
Bank Sta=41.15,49.17
XS Rating Curve= 0 ,0
Exp/Cntr=0.3,0.1

Type RM Length L Ch R = 1 ,1354.11 ,2,2,2
XS GIS Cut Line= 5
      345589.681     5423342.126      345594.201     5423355.516
      345602.528     5423369.756      345628.896     5423414.602
      345665.039     5423426.014
#Sta/Elev= 22
       0      22    2.42      21    4.39      20    6.65      19   13.89      18
   27.98    17.5   34.27    17.5   36.38    17.5   36.39   15.35   44.39   15.35
    44.4    17.5   44.41      22    53.9      22   53.91    17.5   61.76   17.53
   69.47    18.1   74.59   20.25   75.63   20.43   80.11   20.56   82.41   20.63
   92.59      21  118.37      22
#Mann= 3 , 0 , 0
       0    .045       0   36.38     .03       0    44.4    .045       0
Bank Sta=36.38,44.4
XS Rating Curve= 36 ,-1
       1    14.9       1   15.35    1.12    15.4    2.38    15.6    4.51    15.8
    7.27      16   10.17    16.2   14.42    16.4   19.65    16.6   24.04    16.8
   28.66      17   33.47    17.2   38.44    17.4   43.23    17.6   48.59    17.8
   57.78      18   68.06    18.2    79.6    18.4   99.06    18.6  118.06    18.8
  136.27      19  155.74    19.2   176.4    19.4  198.17    19.6     221    19.8
  244.86      20  269.68    20.2  295.44    20.4  322.11    20.6  349.65    20.8
  378.04      21  409.25    21.2  441.26    21.4  474.06    21.6  507.61    21.8
  541.91      22
Exp/Cntr=0.3,0.1

Type RM Length L Ch R = 1 ,1347.51 ,10.9,10.91,11.24
XS GIS Cut Line= 5
      345588.686     5423345.055      345593.026     5423359.294
      345598.692     5423370.579      345624.909     5423421.453
      345638.343      5423423.96
#Sta/Elev= 26
       0      21    1.87      20    4.21      19   14.46      18   14.89   16.96
   20.77   16.21   30.74   14.71   31.07   14.29   34.28    10.8   34.83    9.94
   35.34    9.67   42.14    8.21   43.61    7.72   46.98    8.33   51.77    8.64
   52.39     9.4   54.39   12.16   55.03   12.52   55.52   13.08   57.85   14.26
   64.19   15.38   66.96   17.45    70.9   19.69   73.88   20.03   76.45    20.2
   98.41      21
#Mann= 3 , 0 , 0
       0     .06       0   35.34    .045       0   52.39     .06       0
Bank Sta=35.34,52.39
XS Rating Curve= 0 ,0
Exp/Cntr=0.3,0.1

Type RM Length L Ch R = 1 ,1336.58 ,9.87,9.75,9.67
XS GIS Cut Line= 3
345578.5264892585423353.88812256345602.9235229495423402.84667969
345616.0902709965423415.81207275
#Sta/Elev= 24
       0    17.7     .04   17.67   12.25   17.31   13.02   17.28   18.49   14.81
   20.17   14.18   24.65   11.91   26.32   11.34   28.63   10.41   32.74    8.97
   34.58    8.32   38.91    7.69   49.67    8.27    50.7    8.66   54.61   10.12
    54.7   10.18   55.34   10.55   61.01   16.48   61.91   17.19   63.23   18.37
   63.64   18.52   68.47   19.32   71.66   19.72   73.18   19.85
#Mann= 3 , 0 , 0
       0     .06       0   32.74    .045       0    50.7     .06       0
Bank Sta=32.74,50.7
XS Rating Curve= 0 ,0
Exp/Cntr=0.3,0.1

Type RM Length L Ch R = 1 ,1326.83 ,9.03,9.61,10.57
XS GIS Cut Line= 3
345567.1068725595423354.02850342345595.5656738285423409.42608643
345613.1859130865423423.93969727
#Sta/Elev= 23
       0   18.69    3.26   17.44   18.41    17.1   18.44    17.1   18.45   17.09
   26.96   13.87   28.11   13.28   34.04    9.01   36.12     8.3   37.81    8.29
   42.68    7.68   57.15    8.44   57.65    8.45   58.96    8.49   60.46    9.19
   62.28   10.54   69.79   16.57   70.07    16.8   70.09   16.81   76.13   19.02
   77.07   19.17   77.74   19.26   85.11   19.87
#Mann= 3 , 0 , 0
       0     .06       0   37.81    .045       0   57.65     .06       0
Bank Sta=37.81,57.65
XS Rating Curve= 0 ,0
Exp/Cntr=0.3,0.1

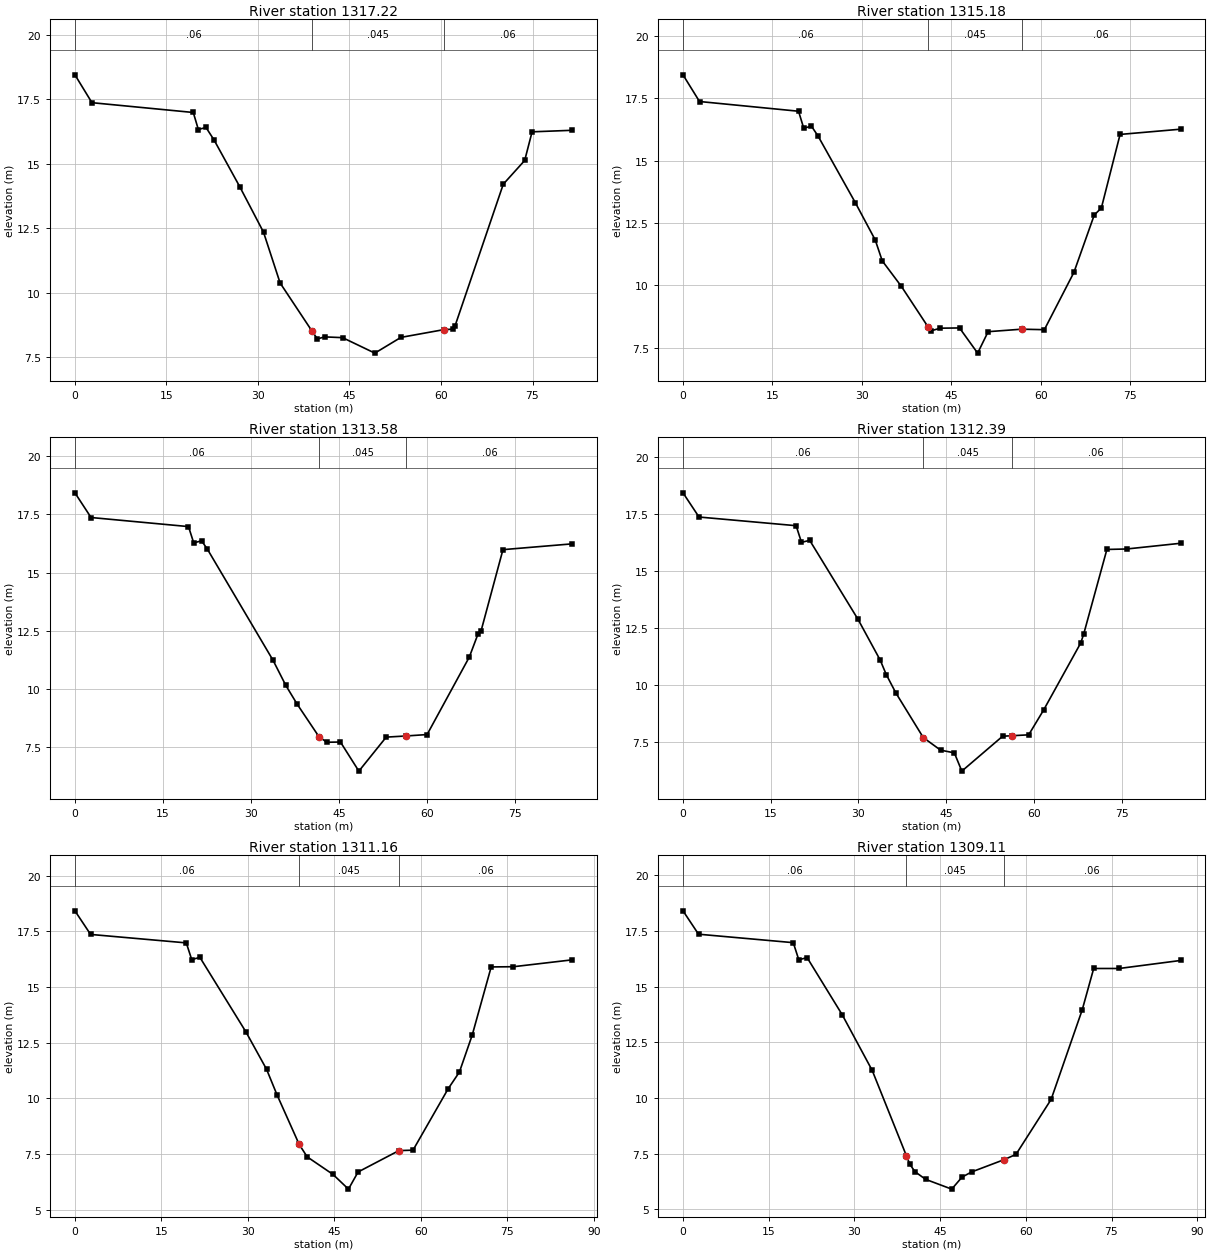
Type RM Length L Ch R = 1 ,1317.22 ,2.21,2.04,2.76
XS GIS Cut Line= 6
345565.0184936525423354.92169189345572.2908935555423370.13171387
345573.1593017585423375.54650879345572.6735229495423384.02532959
345586.377319336 5423414.9362793345588.875305176 5423431.4876709
#Sta/Elev= 22
       0   18.45    2.79   17.37    19.4   16.99   20.23   16.33   21.48   16.41
   22.79   15.93      27   14.12   30.91   12.35   33.63   10.38   38.88   8.507
   39.74    8.21   40.91    8.29   43.87    8.26   49.16    7.66   53.43    8.27
   60.45    8.57   62.04    8.59   62.28     8.7   70.21   14.21   73.72   15.13
   74.93   16.24   81.55    16.3
#Mann= 3 , 0 , 0
       0     .06       0   38.88    .045       0   60.45     .06       0
Bank Sta=38.88,60.45
XS Rating Curve= 0 ,0
Exp/Cntr=0.3,0.1

Type RM Length L Ch R = 1 ,1315.18 ,1.1,1.6,1.22
XS GIS Cut Line= 6
 345564.968872075423354.94750977345572.1588745125423369.88769531
345572.0980834965423388.09851074345581.2106933595423407.60107422
 345583.316284185423426.44488525345587.8651123055423432.73028564
#Sta/Elev= 23
       0   18.44    2.77   17.37   19.38   16.98   20.25    16.3   21.55   16.38
   22.64   15.99   28.89   13.32   32.24   11.82   33.42   10.98   36.62    9.96
   41.07   8.343   41.56    8.17   43.13    8.28   46.38    8.29   49.42    7.28
   51.18    8.14   56.79    8.24   60.61    8.22   65.57   10.52   68.98   12.82
   70.17    13.1   73.31   16.05   83.45   16.26
#Mann= 3 , 0 , 0
       0     .06       0   41.07    .045       0   56.79     .06       0
Bank Sta=41.07,56.79
XS Rating Curve= 0 ,0
Exp/Cntr=0.3,0.1

Type RM Length L Ch R = 1 ,1313.58 ,0.78,1.18,1.58
XS GIS Cut Line= 6
345564.9194946295423354.97808838345572.1093139655423369.91827393
345570.6159057625423386.47210693 345581.06829834 5423411.8572998
345582.025512695 5423426.8270874345587.8176879885423433.50067139
#Sta/Elev= 21
       0   18.43    2.75   17.37   19.36   16.98   20.25   16.28   21.59   16.37
   22.58   16.01   33.77   11.24   35.95   10.16   37.87    9.36   41.62    7.95
   42.95    7.72   45.26    7.73    48.4    6.48   53.06    7.94   56.47    7.99
   60.03    8.05   67.23   11.38   68.71   12.37   69.23    12.5   72.96   15.99
   84.81   16.24
#Mann= 3 , 0 , 0
       0     .06       0   41.62    .045       0   56.47     .06       0
Bank Sta=41.62,56.47
XS Rating Curve= 0 ,0
Exp/Cntr=0.3,0.1

Type RM Length L Ch R = 1 ,1312.39 ,0.46,1.23,1.32
XS GIS Cut Line= 6
345564.8464965825423355.00653076345572.0363159185423369.94647217
345570.0844726565423387.67047119345579.7243041995423412.77947998
345580.729309082 5423426.9362793345587.0941162115423433.58447266
#Sta/Elev= 22
       0   18.42    2.74   17.36   19.34   16.98   20.26   16.25   21.66   16.34
   29.92   12.88   33.72   11.09   34.75   10.46   36.38    9.66   41.08     7.7
   44.03    7.15   46.39    7.03   47.67    6.23   54.65    7.76    56.2    7.78
    59.1    7.82   61.66    8.91   67.99   11.84   68.49   12.22   72.47   15.94
   75.85   15.96   85.06   16.21
#Mann= 3 , 0 , 0
       0     .06       0   41.08    .045       0    56.2     .06       0
Bank Sta=41.08,56.2
XS Rating Curve= 0 ,0
Exp/Cntr=0.3,0.1

Type RM Length L Ch R = 1 ,1311.16 ,0.62,2.06,2.03
XS GIS Cut Line= 6
345564.8093261725423355.02832031345571.9993286135423369.96832275
345569.8137207035423391.62249756345578.523071289 5423413.4307251
345579.9135131845423427.22930908345587.4268798835423434.16430664
#Sta/Elev= 21
       0   18.42    2.72   17.36   19.32   16.98   20.26   16.23   21.68   16.33
   29.67   12.98   33.25    11.3   35.05   10.16    38.9    7.93   40.29    7.37
   44.77    6.58   47.45    5.92   49.12    6.69    56.2    7.65   58.65    7.67
   64.75   10.43    66.7   11.18   68.92   12.84   72.21    15.9   76.08   15.91
   86.31   16.22
#Mann= 3 , 0 , 0
       0     .06       0    38.9    .045       0    56.2     .06       0
Bank Sta=38.9,56.2
XS Rating Curve= 0 ,0
Exp/Cntr=0.3,0.1

Type RM Length L Ch R = 1 ,1309.11 ,6.52,3.75,6.42
XS GIS Cut Line= 6
345564.7744750985423355.04187012345572.8378906255423375.49188232
345568.4577026375423393.36468506345576.3964843755423413.10290527
345578.139099121 5423427.4229126345586.6586914065423434.00231934
#Sta/Elev= 21
       0   18.41    2.72   17.36    19.3   16.98   20.27   16.21   21.72   16.31
   27.85   13.75   33.12   11.24    39.1    7.41   39.71    7.02   40.62    6.69
   42.46    6.35   47.03    5.91   48.84    6.45    50.5    6.68   56.16    7.23
   58.28    7.47   64.43    9.94   69.87   13.96   71.88   15.82   76.32   15.82
   87.08   16.18
#Mann= 3 , 0 , 0
       0     .06       0    39.1    .045       0   56.16     .06       0
Bank Sta=39.1,56.16
XS Rating Curve= 0 ,0
Exp/Cntr=0.3,0.1

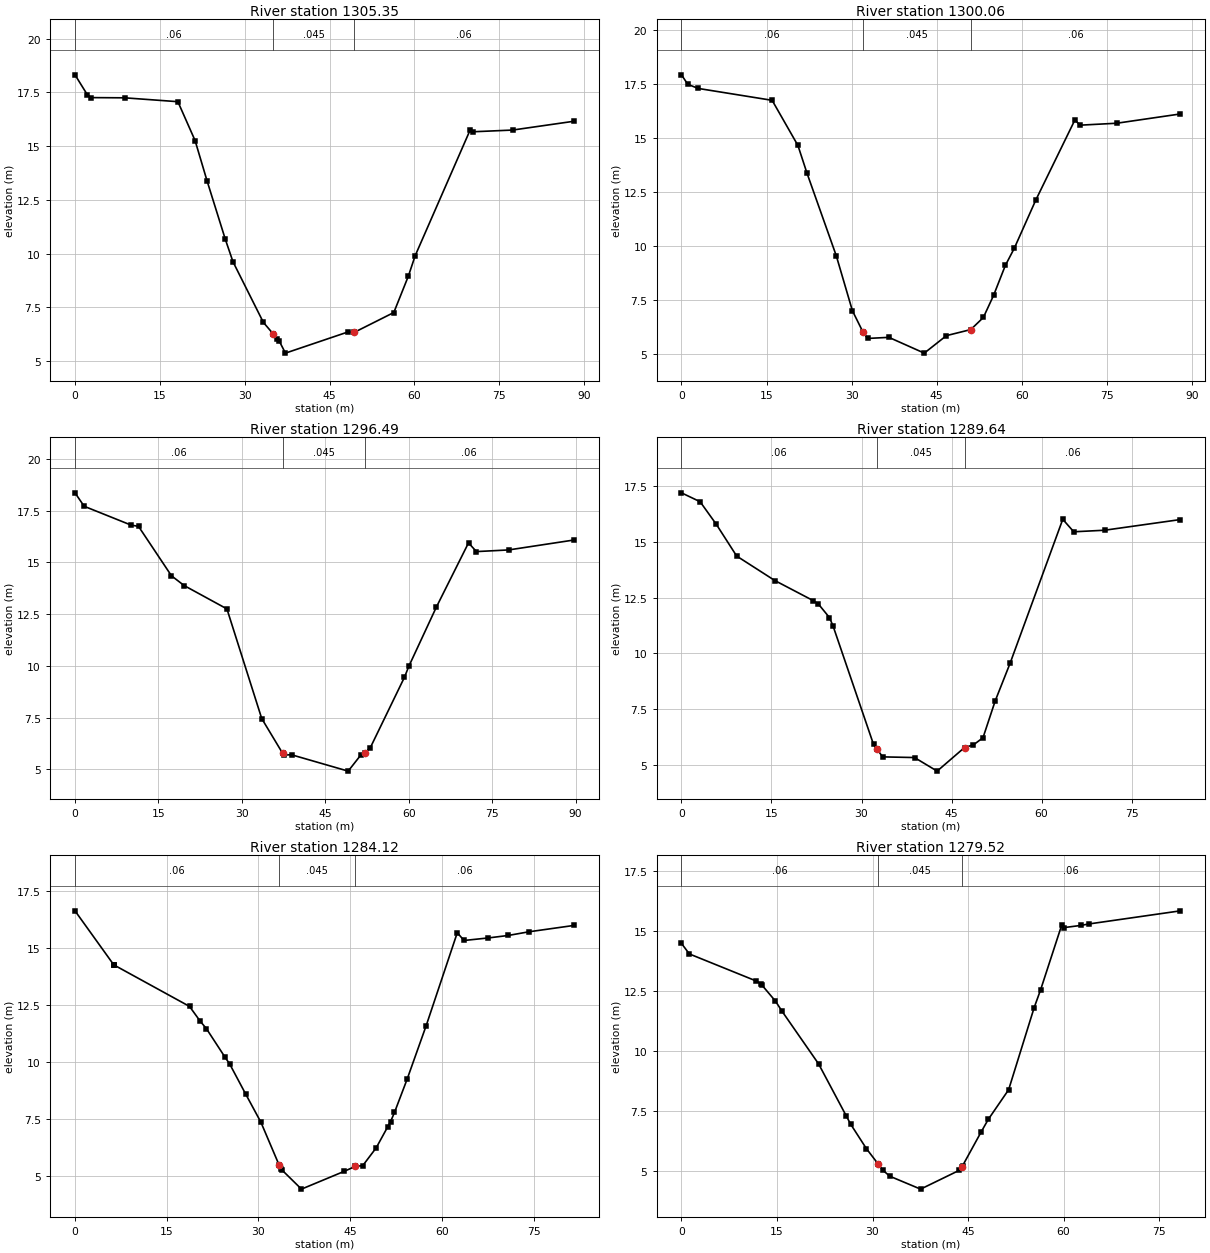
Type RM Length L Ch R = 1 ,1305.35 ,5.31,5.29,1.97
XS GIS Cut Line= 6
345559.7445068365423355.62988281345562.455322266 5423388.5269165
 345570.587707525423408.65209961345569.6195068365423413.68347168
345577.1710815435423429.16448975345586.0778808595423435.35668945
#Sta/Elev= 23
       0   18.32    2.19   17.39    2.87   17.26    8.78   17.25   18.19   17.07
   21.23   15.26   23.34   13.39   26.57   10.67   27.93    9.62    33.3     6.8
   35.05    6.26   35.66    6.01   36.11    5.93    37.2    5.37   48.31    6.36
   49.32    6.33   56.36    7.26   58.94    8.96   60.13     9.9   69.88   15.77
   70.32   15.67   77.36   15.75   88.21   16.16
#Mann= 3 , 0 , 0
       0     .06       0   35.05    .045       0   49.32     .06       0
Bank Sta=35.05,49.32
XS Rating Curve= 0 ,0
Exp/Cntr=0.3,0.1

Type RM Length L Ch R = 1 ,1300.06 ,8.07,3.57,2.09
XS GIS Cut Line= 6
345547.5458984385423360.85467529345549.094909668 5423382.9151001
345557.2272949225423389.49450684345562.4553222665423402.65332031
345576.2028808595423429.35791016345585.3032836915423435.93731689
#Sta/Elev= 23
       0   17.94    1.12    17.5    2.96   17.31   15.99   16.76   20.54   14.67
   22.11   13.41   27.31    9.56   30.15    7.02   32.04    6.02   32.84    5.74
   36.58    5.79   42.82    5.06   46.73    5.87   51.02    6.15   53.24    6.71
   55.04    7.73   57.12    9.12   58.69    9.91   62.48   12.14   69.38   15.85
   70.29   15.61   76.77    15.7      88   16.13
#Mann= 3 , 0 , 0
       0     .06       0   32.04    .045       0   51.02     .06       0
Bank Sta=32.04,51.02
XS Rating Curve= 0 ,0
Exp/Cntr=0.3,0.1

Type RM Length L Ch R = 1 ,1296.49 ,8.66,6.85,4.93
XS GIS Cut Line= 6
345536.7785034185423365.99432373345538.5211181645423385.53912354
345553.5272827155423395.89208984345566.4035034185423414.56591797
345574.439086914  5423430.046875345583.7418823245423437.23492432
#Sta/Elev= 22
       0   18.36    1.65   17.71   10.09    16.8   11.42   16.74   17.35   14.35
   19.62   13.88   27.32   12.75   33.58    7.45   37.34    5.77    37.6    5.69
   38.94     5.7   49.12    4.91   51.46    5.71   52.08    5.78    53.1    6.04
   59.25    9.45   60.02    9.97   64.95   12.82   70.76   15.94   72.19   15.52
   77.98    15.6   89.73   16.08
#Mann= 3 , 0 , 0
       0     .06       0   37.34    .045       0   52.08     .06       0
Bank Sta=37.34,52.08
XS Rating Curve= 0 ,0
Exp/Cntr=0.3,0.1

Type RM Length L Ch R = 1 ,1289.64 ,6.54,5.51,4.2
XS GIS Cut Line= 6
345534.960083008 5423374.4005127345539.4135131845423395.88031006
345559.163513184 5423413.4899292345571.9431152345423427.22930908
345573.1046752935423430.32550049345582.7863159185423438.45288086
#Sta/Elev= 23
       0   17.21    3.11   16.81    5.82   15.79     9.2   14.37   15.56   13.27
   21.94   12.37   22.83   12.21   24.65   11.61   25.27   11.22      32    5.91
    32.6   5.689   33.52    5.35   38.83    5.32    42.6    4.71   47.16    5.77
   48.65    5.89   50.24    6.21   52.28    7.87   54.76    9.56   63.53   16.02
   65.36   15.46    70.5   15.53   83.14   16.01
#Mann= 3 , 0 , 0
       0     .06       0    32.6    .045       0   47.16     .06       0
Bank Sta=32.6,47.16
XS Rating Curve= 0 ,0
Exp/Cntr=0.3,0.1

Type RM Length L Ch R = 1 ,1284.12 ,4.63,4.6,4.6
XS GIS Cut Line= 5
345533.9918823245423378.27069092345540.7689208985423405.36248779
345559.163513184 5423419.4888916345571.1685180665423430.71252441
345582.2053222665423439.42047119
#Sta/Elev= 30
       0   16.61    6.32   14.25    6.35   14.24    6.42   14.23   18.73   12.42
   20.51   11.76   21.48   11.45   24.52    10.2   25.31    9.89   27.93    8.57
   30.41    7.34   33.36    5.48   33.66    5.29   33.92    5.23   37.04    4.41
   44.03    5.19   45.86    5.41   47.06    5.44   49.26    6.22   51.12    7.13
   51.61    7.37   52.25    7.77   54.32    9.23   57.44   11.58   62.52   15.65
   63.63   15.31   67.55   15.42   70.86   15.53   74.21   15.69   81.61   15.97
#Mann= 3 , 0 , 0
       0     .06       0   33.36    .045       0   45.86     .06       0
Bank Sta=33.36,45.86
XS Rating Curve= 0 ,0
Exp/Cntr=0.3,0.1

Type RM Length L Ch R = 1 ,1279.52 ,21.06,20.58,18.23
XS GIS Cut Line= 3
345532.9932861335423384.27532959345538.6085205085423409.52868652
345580.2744750985423441.43670654
#Sta/Elev= 28
       0   14.49    1.24   14.05   11.65   12.93   12.46   12.81   12.57   12.77
   14.76   12.08   15.81   11.65   21.53    9.46   25.87    7.29   26.57    6.94
   29.04    5.92   30.91    5.27   31.67    5.01    32.7    4.77   37.55    4.23
   43.58    5.01      44    5.16   44.15    5.21   47.08    6.63   48.17    7.14
   51.37    8.38   55.38   11.81    56.4   12.56   59.71   15.26   60.07   15.15
   62.69   15.24   63.93    15.3   78.35   15.85
#Mann= 3 , 0 , 0
       0     .06       0   30.91    .045       0      44     .06       0
Bank Sta=30.91,44
XS Rating Curve= 0 ,0
Exp/Cntr=0.3,0.1

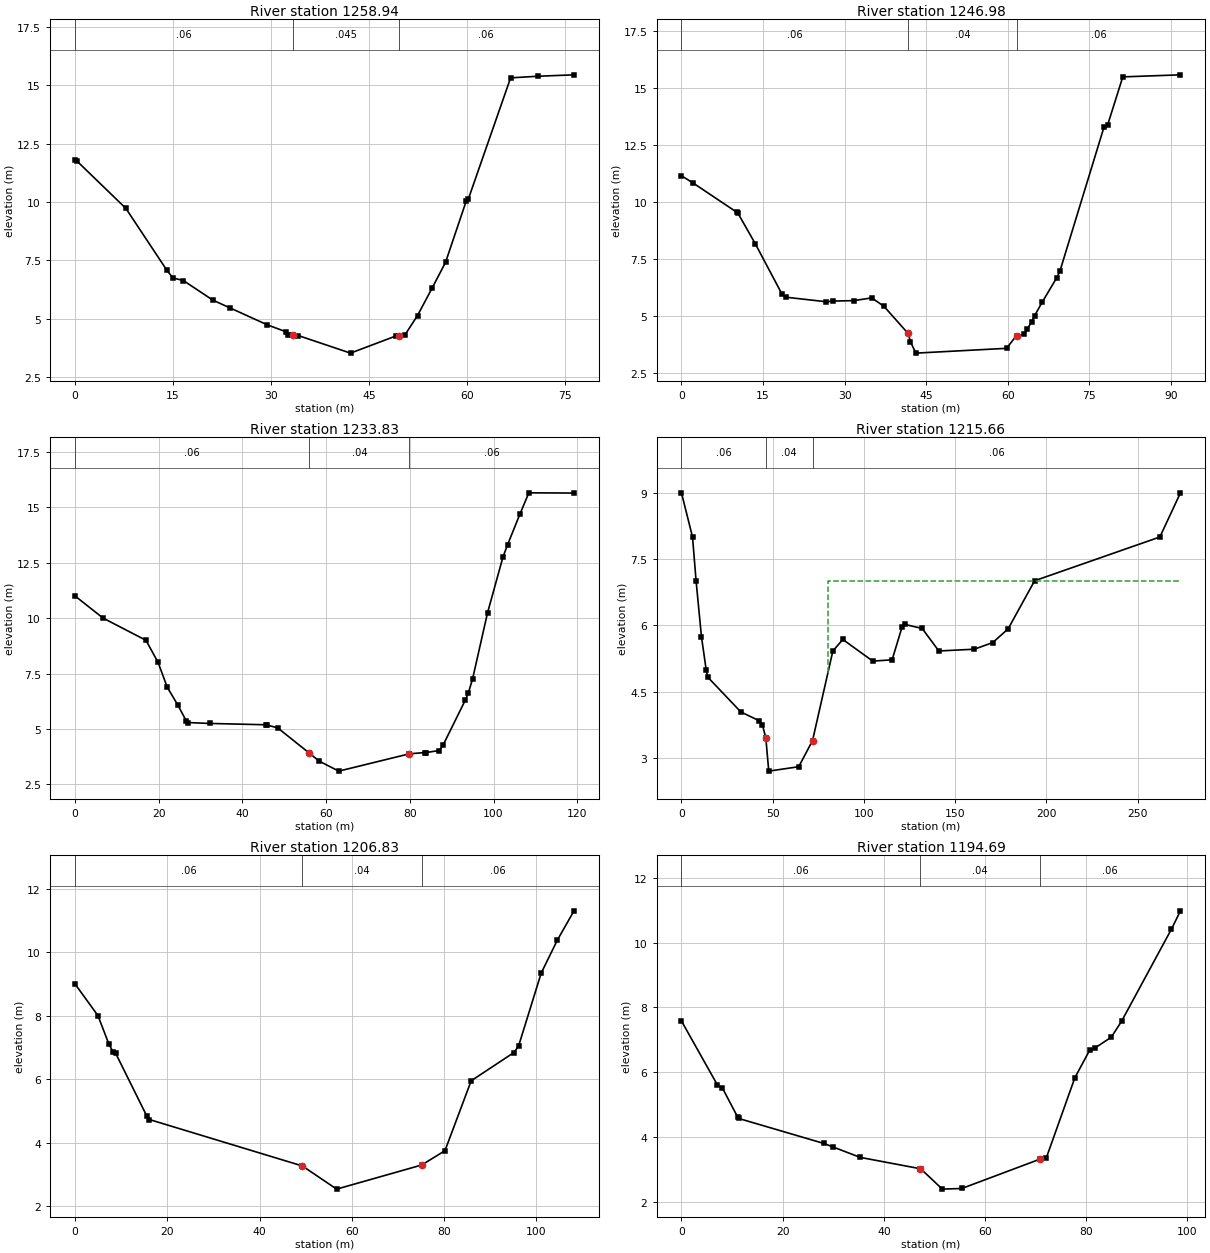
Type RM Length L Ch R = 1 ,1258.94 ,14.84,11.95,10.6
XS GIS Cut Line= 6
345522.9550781255423401.68572998345524.8914794925423425.29412842
 345531.281127935423432.26068115345551.2249145515423440.38812256
345567.2958984385423442.32330322345572.7175292975423441.54907227
#Sta/Elev= 26
       0   11.82     .36   11.74    7.78    9.73   14.08    7.07   14.99    6.75
   16.57    6.64   21.09     5.8   23.69    5.47   29.43    4.74   32.23    4.45
   32.63    4.29   33.14    4.29    33.4    4.29   34.19    4.28   42.15    3.53
   49.05    4.26    49.5    4.28    50.5    4.32    52.4    5.14   54.68    6.34
   56.69    7.42   59.87   10.06   60.19   10.14   66.64   15.32   70.86   15.39
   76.34   15.45
#Mann= 3 , 0 , 0
       0     .06       0    33.4    .045       0    49.5     .06       0
Bank Sta=33.4,49.5
XS Rating Curve= 0 ,0
Exp/Cntr=0.3,0.1

Type RM Length L Ch R = 1 ,1246.98 ,14.29,13.16,11.44
XS GIS Cut Line= 4
345503.5922851565423409.42608643345515.4036865235423438.84008789
345545.8032836915423450.83770752345572.7175292975423445.99987793
#Sta/Elev= 28
       0   11.14    2.15   10.82   10.24    9.53    10.4    9.49   13.55    8.17
   18.51    5.94   19.18    5.82   26.62    5.62   27.86    5.65    31.7    5.67
   34.98    5.79   37.22    5.42   41.66    4.23   42.09    3.87   43.08    3.37
   59.75    3.58   61.59    4.14      63    4.19   63.52    4.41   64.38    4.75
   64.91    5.01    66.3     5.6      69    6.68   69.56    6.96   77.65   13.26
   78.34   13.37   81.12   15.47   91.72   15.56
#Mann= 3 , 0 , 0
       0     .06       0   41.66     .04       0   61.59     .06       0
Bank Sta=41.66,61.59
XS Rating Curve= 0 ,0
Exp/Cntr=0.3,0.1

Type RM Length L Ch R = 1 ,1233.83 ,13.43,18.16,44.49
XS GIS Cut Line= 4
      345478.785     5423416.491      345487.955     5423436.547
      345542.344     5423465.597      345573.601     5423448.729
#Sta/Elev= 29
       0      11    6.72      10   16.96       9   19.86       8   22.05    6.88
   24.57    6.08   26.63    5.35   26.98    5.29   32.23    5.25    45.7    5.19
   45.85    5.18   48.44    5.05      56    3.91   58.36    3.55   63.03     3.1
   79.88    3.88   83.71    3.94   83.96    3.94   87.04    4.03   87.94    4.27
   93.23    6.29   93.96    6.61      95    7.26   98.57   10.24  102.25   12.75
  103.36   13.31  106.35   14.71  108.44   15.65  119.23   15.64
#Mann= 3 , 0 , 0
       0     .06       0      56     .04       0   79.88     .06       0
Bank Sta=56,79.88
XS Rating Curve= 0 ,0
Exp/Cntr=0.3,0.1

Type RM Length L Ch R = 1 ,1215.66 ,3.29,8.84,30.29
XS GIS Cut Line= 6
      345477.213       5423433.9      345481.391     5423444.044
      345535.779     5423487.463      345604.234     5423528.694
      345634.313     5423582.273      345676.696     5423611.391
#Sta/Elev= 27
       0       9    6.06       8    8.03       7   10.97    5.74   13.56    4.99
   14.36    4.83   32.53    4.04   42.62    3.84    44.4    3.74   46.23    3.45
   47.83     2.7   64.25     2.8   71.81    3.39   82.96    5.42   88.42    5.68
  104.84    5.19  115.43    5.22  120.85    5.96  122.47    6.02  131.88    5.93
  141.03    5.42  160.48    5.46  170.55    5.61  178.98    5.92  193.51    7.01
  262.13       8  273.42       9
#Mann= 3 , 0 , 0
       0     .06       0   46.23     .04       0   71.81     .06       0
#XS Ineff= 2 , 0
   10.97                   80.27   10.97       7
Permanent Ineff=
       F       F
Bank Sta=46.23,71.81
XS Rating Curve= 0 ,0
Exp/Cntr=0.3,0.1

Type RM Length L Ch R = 1 ,1206.83 ,5.65,12.13,10.44
XS GIS Cut Line= 5
      345471.485     5423436.009      345474.532      5423442.67
       345500.97      5423463.77      345525.126     5423501.218
       345529.12     5423523.268
#Sta/Elev= 17
       0       9    4.98       8    7.33    7.11    8.24    6.86     8.8    6.82
   15.56    4.84   16.14    4.73   49.26    3.27    56.7    2.54   75.14     3.3
   80.17    3.75   85.85    5.95   95.12    6.84   96.11    7.04  101.02    9.34
  104.53   10.38  108.13    11.3
#Mann= 3 , 0 , 0
       0     .06       0   49.26     .04       0   75.14     .06       0
Bank Sta=49.26,75.14
XS Rating Curve= 0 ,0
Exp/Cntr=0.3,0.1

Type RM Length L Ch R = 1 ,1194.69 ,13.81,9.63,10.09
XS GIS Cut Line= 5
345469.0161132815423443.62091064345489.9384765635423462.43969727
345496.7857055665423480.30792236345517.5178833015423507.87091064
345523.9846801765423523.45812988
#Sta/Elev= 21
       0    7.58    7.09    5.61     8.1    5.51   11.09    4.62   11.34    4.57
   28.14     3.8   29.98    3.69   35.33    3.37    47.2    3.02   47.28    3.02
   51.57    2.39   55.42    2.41   70.78    3.31   72.09    3.34   77.77    5.83
    80.7    6.68   81.77    6.75   84.97    7.08   86.99    7.57   96.84   10.41
   98.64   10.98
#Mann= 3 , 0 , 0
       0     .06       0    47.2     .04       0   70.78     .06       0
Bank Sta=47.2,70.78
XS Rating Curve= 0 ,0
Exp/Cntr=0.3,0.1

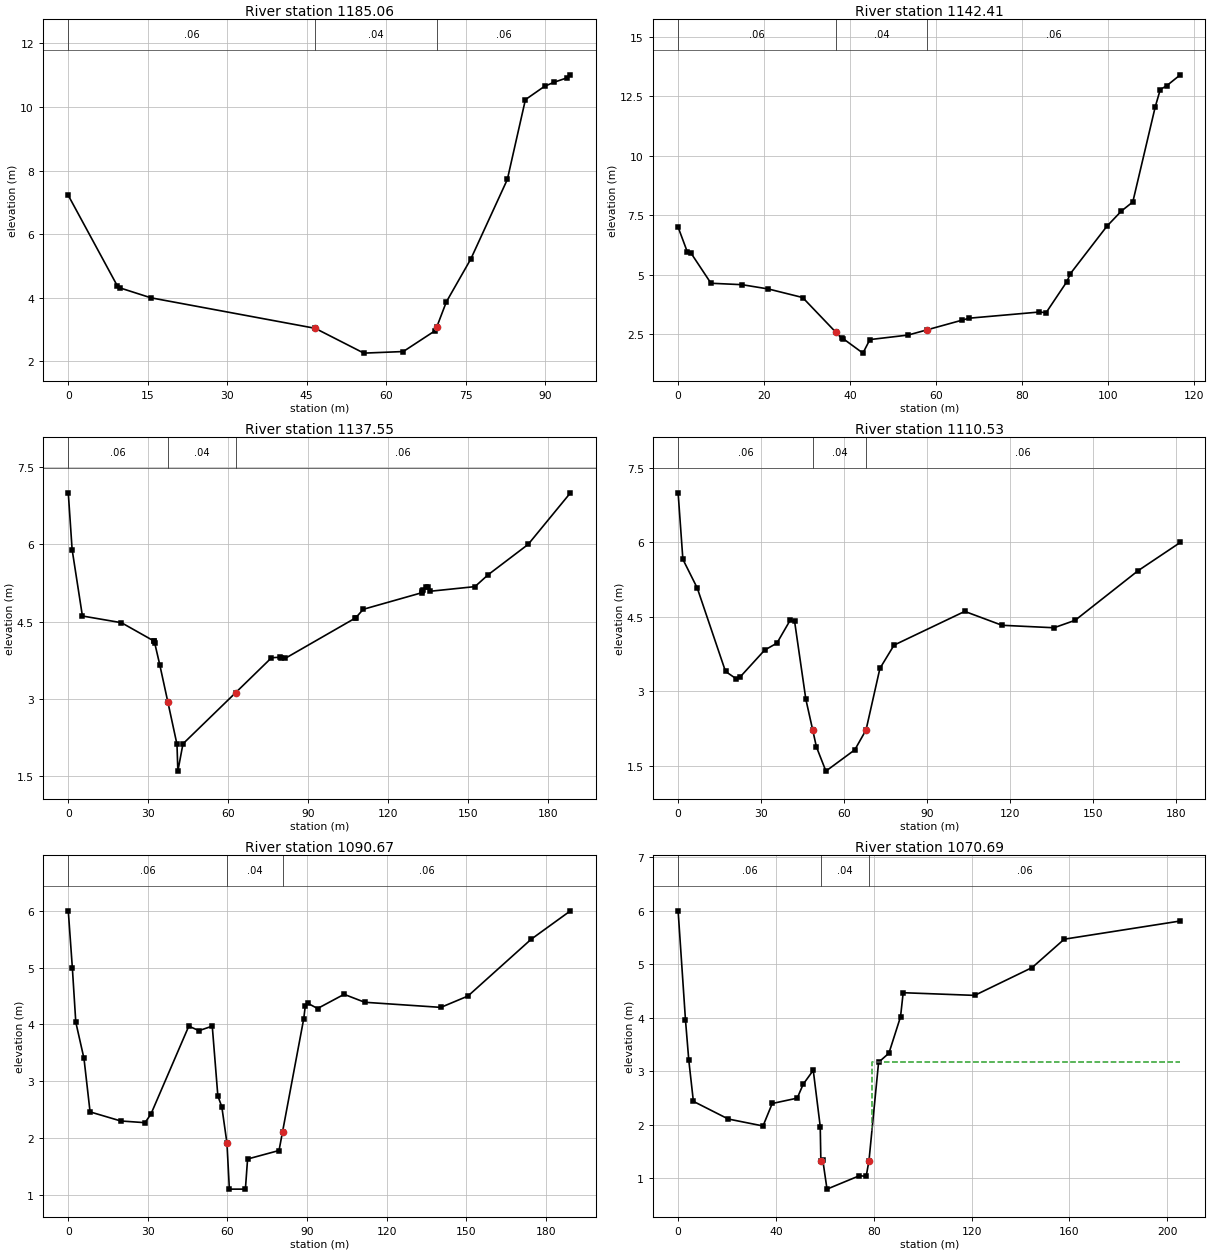
Type RM Length L Ch R = 1 ,1185.06 ,39.08,42.67,27.12
XS GIS Cut Line= 2
345461.0206909185423448.80969238345517.9926757815423524.51312256
#Sta/Elev= 17
       0    7.22    9.27    4.37    9.77    4.31   15.57       4   46.59    3.04
   55.77    2.26   63.21    2.31   69.26    2.97    69.5    3.07   71.33    3.87
   75.95    5.22   82.84    7.72   86.25   10.23   89.87   10.65   91.71   10.78
   94.19   10.92   94.75   11.01
#Mann= 3 , 0 , 0
       0     .06       0   46.59     .04       0    69.5     .06       0
Bank Sta=46.59,69.5
XS Rating Curve= 0 ,0
Exp/Cntr=0.3,0.1

Type RM Length L Ch R = 1 ,1142.41 ,4.43,4.85,27.61
XS GIS Cut Line= 4
      345426.654     5423465.206      345428.519     5423466.288
      345463.215     5423521.888      345511.352     5423531.572
#Sta/Elev= 27
       0       7    2.16    5.95    2.99    5.91    7.64    4.64   14.87    4.58
   20.97     4.4   28.96    4.04   36.66   2.583      38    2.33   38.37    2.31
   42.98     1.7    44.6    2.27   53.49    2.46   57.94   2.682    66.1    3.09
    67.7    3.17   84.05    3.43   85.58     3.4   90.39     4.7   91.26    5.05
   99.73    7.04  103.11    7.68  105.75    8.06  110.98   12.07  112.14   12.79
  113.63   12.95   116.8   13.41
#Mann= 3 , 0 , 0
       0     .06       0   36.66     .04       0   57.94     .06       0
Bank Sta=36.66,57.94
XS Rating Curve= 0 ,0
Exp/Cntr=0.3,0.1

Type RM Length L Ch R = 1 ,1137.55 ,29.92,27.02,29.65
XS GIS Cut Line= 6
      345424.695     5423467.845      345466.029     5423536.257
      345483.845     5423557.498      345495.411     5423582.174
      345503.954      5423624.25      345514.441     5423623.702
#Sta/Elev= 30
       0       7    1.44     5.9     5.3    4.61   19.94    4.48   32.28    4.12
    32.3    4.12    32.4    4.09   34.33    3.66   37.31    2.95   40.77    2.12
    41.1     1.6   43.02    2.13   62.73    3.12   76.22     3.8    79.3    3.81
   79.93     3.8   81.43    3.79  107.66    4.57  107.89    4.58  110.64    4.74
  132.49    5.06  132.77    5.09     133    5.12  133.99    5.18  134.91    5.17
  135.71    5.09  152.53    5.18  157.46    5.41  172.49       6  188.35       7
#Mann= 3 , 0 , 0
       0     .06       0   37.31     .04       0   62.73     .06       0
Bank Sta=37.31,62.73
XS Rating Curve= 0 ,0
Exp/Cntr=0.3,0.1

Type RM Length L Ch R = 1 ,1110.53 ,25.03,19.85,11
XS GIS Cut Line= 5
      345406.265     5423473.636      345405.634     5423475.242
      345405.824     5423495.961      345438.539     5423539.111
       345439.11     5423550.136
#Sta/Elev= 24
       0       7    1.72    5.66    6.92    5.08   17.12     3.4   21.03    3.25
   22.44    3.29   31.27    3.83    35.7    3.97   40.46    4.43   42.08    4.41
   46.14    2.84   48.62    2.22   49.96    1.88   53.39    1.39   63.84    1.82
   67.89    2.22    72.9    3.46   78.01    3.93  103.55    4.61  117.02    4.33
  135.79    4.28  143.42    4.43  166.17    5.43  181.43       6
#Mann= 3 , 0 , 0
       0     .06       0   48.62     .04       0   67.89     .06       0
Bank Sta=48.62,67.89
XS Rating Curve= 0 ,0
Exp/Cntr=0.3,0.1

Type RM Length L Ch R = 1 ,1090.67 ,16.1,19.98,36.69
XS GIS Cut Line= 5
      345362.084     5423492.508      345363.835     5423494.033
       345377.77     5423506.815      345492.503     5423609.947
      345502.318     5423619.568
#Sta/Elev= 29
       0       6    1.53       5    2.83    4.04    5.92     3.4    8.21    2.46
   19.77     2.3   28.91    2.27   31.14    2.42   45.42    3.97   49.24    3.89
   54.26    3.97   56.37    2.74   57.86    2.55    59.8    1.91   60.71     1.1
   66.75     1.1   67.57    1.63   79.42    1.78   80.75    2.11   88.73     4.1
   89.31    4.32   90.36    4.37   93.94    4.28  103.94    4.53  111.72    4.39
  140.41     4.3  150.63     4.5  174.45     5.5  189.25       6
#Mann= 3 , 0 , 0
       0     .06       0    59.8     .04       0   80.75     .06       0
Bank Sta=59.8,80.75
XS Rating Curve= 0 ,0
Exp/Cntr=0.3,0.1

Type RM Length L Ch R = 1 ,1070.69 ,4.67,4.88,5.23
Node Photo=..\..\..\Corner Brook\Windshield Survey\CB photos\P1000650.JPG
XS GIS Cut Line= 5
      345356.384     5423501.981      345359.122     5423503.233
      345460.709     5423626.616       345475.87     5423631.631
      345501.934     5423626.792
#Sta/Elev= 25
       0       6    3.01    3.96    4.36    3.21    6.24    2.44    20.5    2.11
   34.71    1.98   38.47     2.4   48.69     2.5   51.13    2.76   55.25    3.02
    58.1    1.97   58.36    1.32   59.12    1.35   60.87      .8   74.09    1.05
   76.88    1.04   78.03    1.33   81.96    3.17   86.18    3.34   90.93    4.02
   92.01    4.47  121.24    4.42  144.74    4.94  157.86    5.47  205.31    5.81
#Mann= 3 , 0 , 0
       0     .06       0   58.36     .04       0   78.03     .06       0
#XS Ineff= 2 , 0
    3.01   57.88    1.98   79.23    3.01    3.17
Permanent Ineff=
       F       F
Bank Sta=58.36,78.03
XS Rating Curve= 0 ,0
Exp/Cntr=0.5,0.3