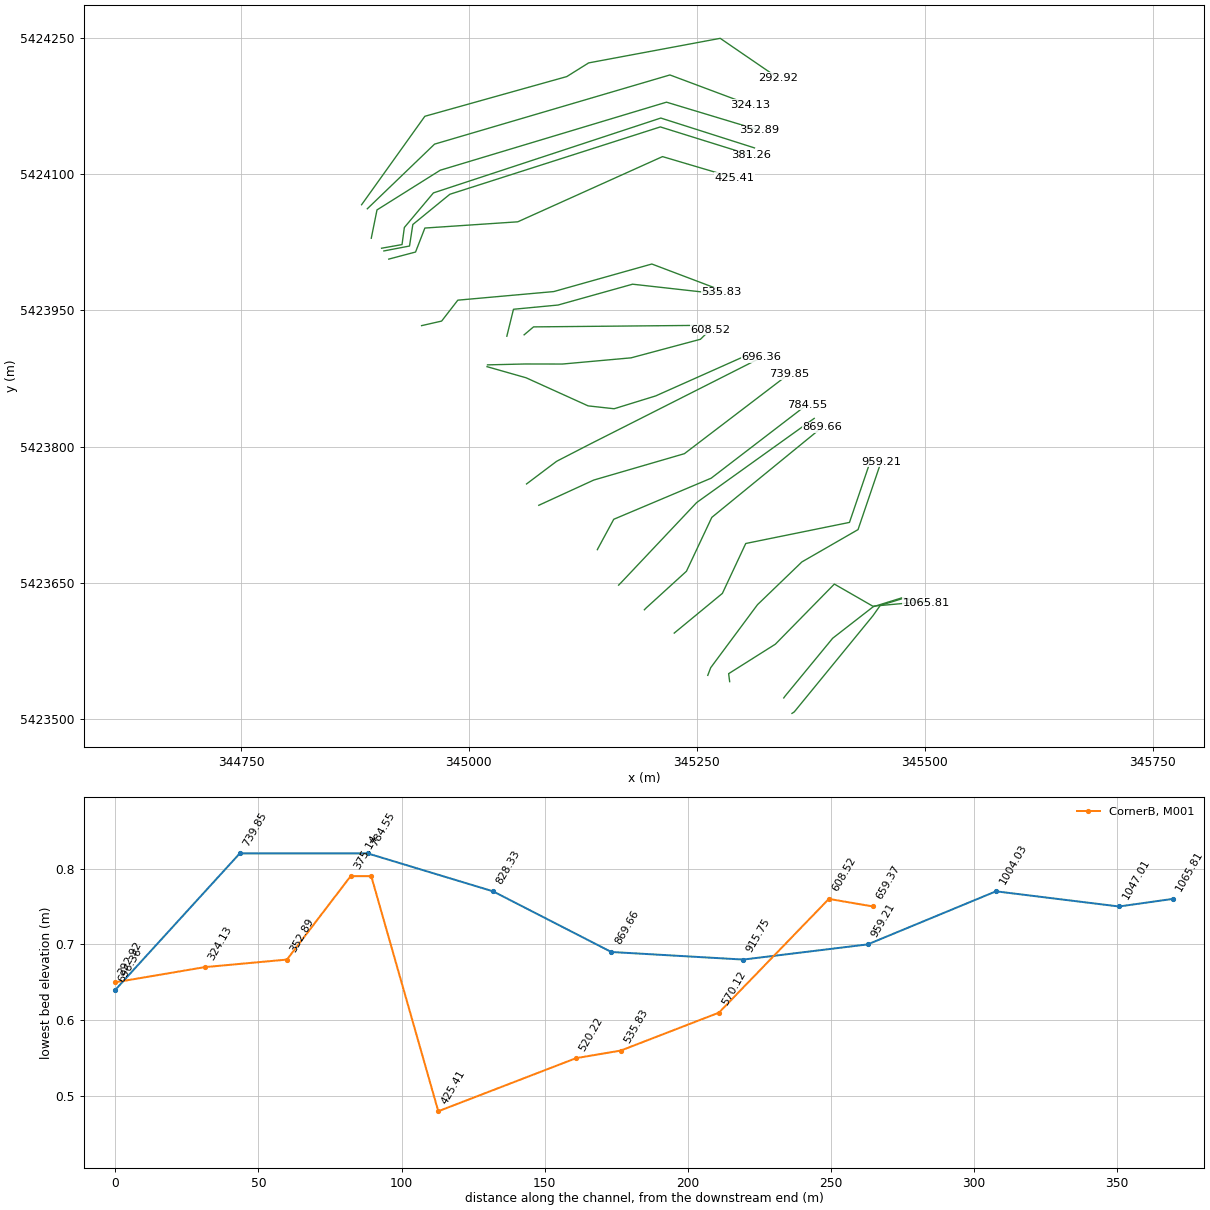
HEC-RAS study Corner_Brook2.prj: Corner_Brook2

--- Corner_Brook2.g03 (geometry) --- (continued)

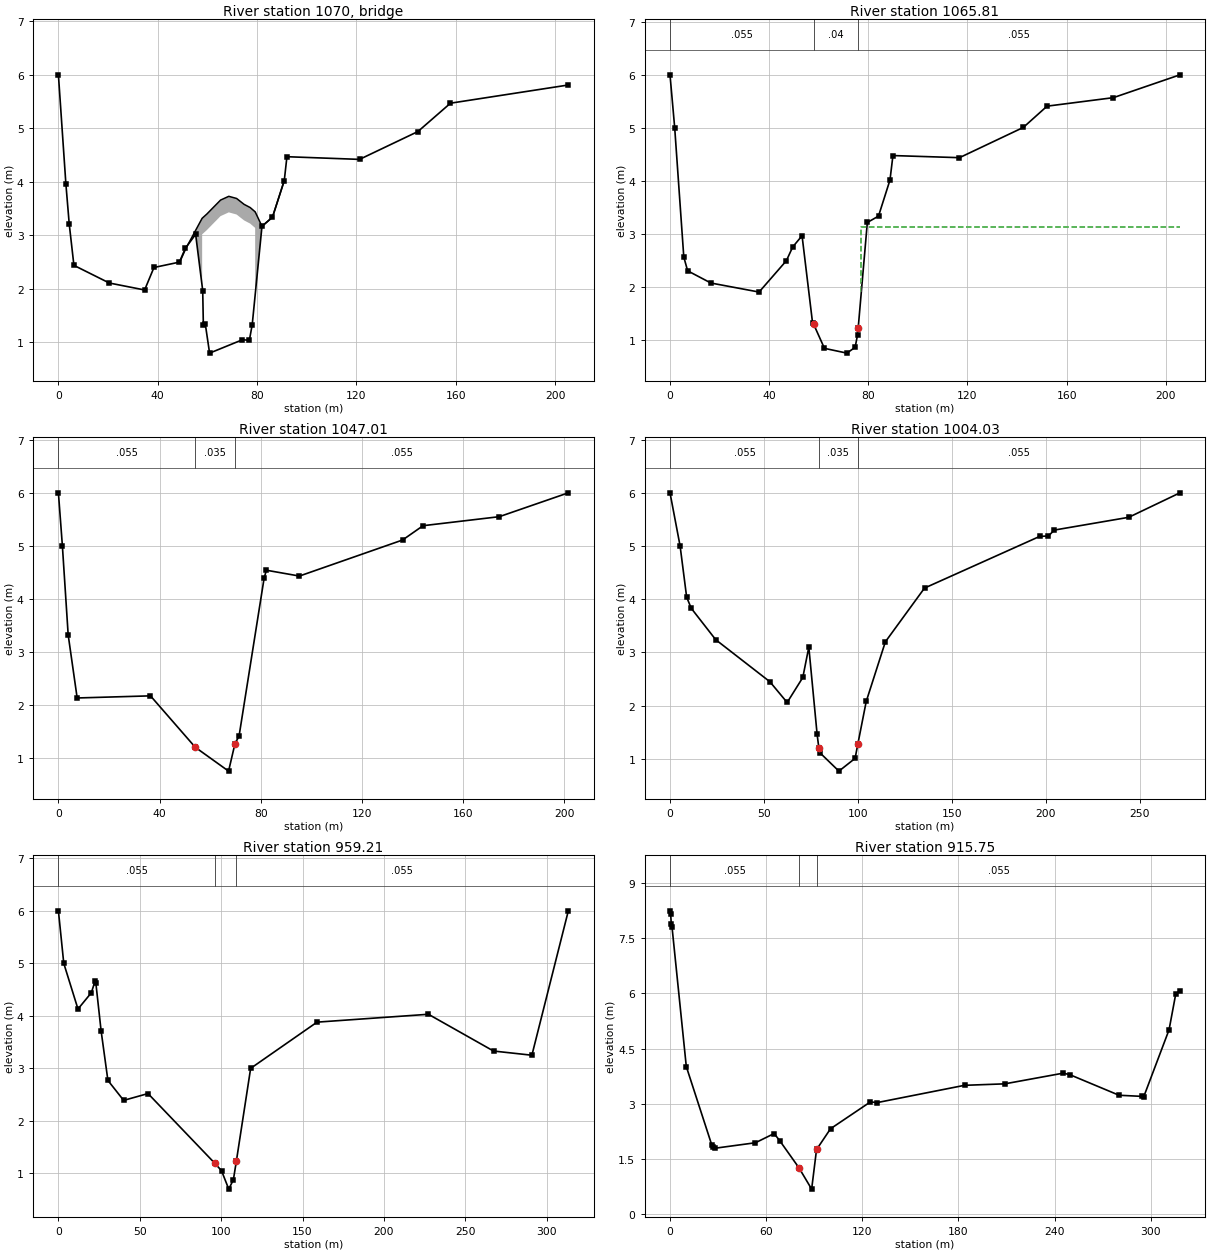
Type RM Length L Ch R = 3 ,1070    ,,,
Node Photo=..\..\..\Corner Brook\Windshield Survey\CB photos\P1000649.JPG
BEGIN DESCRIPTION:
Pedestrian Trail Bridge (Structure #2107)
END DESCRIPTION:
Bridge Culvert--1,0,-1,-1, 0
Deck Dist Width WeirC Skew NumUp NumDn MinLoCord MaxHiCord MaxSubmerge Is_Ogee
1.9,1.9,1.67,0, 16, 16, 1.98, , 0.98, 0, 0,0,,
   48.85   51.36   57.87   57.88   59.79   62.32   65.29    68.6   71.74   74.76
   77.22   79.22   79.23   81.96   86.19   90.88
     2.5    2.76    3.32    3.32     3.4    3.52    3.66    3.73    3.69    3.58
    3.52    3.44    3.44    3.17    3.34    4.02
                       1    3.02     3.1    3.22    3.36    3.43    3.39    3.28
    3.22    3.14       1
   46.83   49.37   55.76   55.77   57.69   60.23   63.19   66.51   69.65   72.74
   75.12   77.15   77.16   79.87   84.11   88.77
     2.5    2.76    3.32    3.32     3.4    3.52    3.66    3.73    3.69    3.58
    3.52    3.44    3.44    3.17    3.34    4.02
                       1    3.02     3.1    3.22    3.36    3.43    3.39    3.28
    3.22    3.14       1
BR Coef=-1 , 0 , 0 ,, 0 ,,,0.8,-1,,0,
WSPro=,,,, 1 ,,,, 0 ,,,, 0 ,,,,-1 ,-1 ,-1 , 0 , 0 , 0 , 0 , 0
BC Design=,, 0 ,, 0 ,,,,,,
BC Use User HTab Curves=0
BC User HTab FreeFlow(D)= 0

Type RM Length L Ch R = 1 ,1065.81 ,18.84,18.79,18.93
Node Photo=..\..\..\..\Corner Brook\Windshield Survey\CB photos\P1000648.JPG
XS GIS Cut Line= 6
      345354.466     5423506.021      345356.933     5423507.606
      345443.205     5423613.497      345451.303     5423624.964
      345475.468     5423632.417       345501.96     5423628.005
#Sta/Elev= 25
       0       6     1.9       5    5.56    2.57    7.11    2.31   16.49    2.08
   35.93    1.91   46.94     2.5   49.51    2.76   53.27    2.97   57.53    1.32
   57.98     1.3    62.3     .85   71.37     .76   74.68     .87   75.68    1.11
   75.93    1.24    79.6    3.22   84.11    3.34   88.74    4.02   89.93    4.48
  116.77    4.44  142.54    5.01   152.1    5.41  178.84    5.57   205.7       6
#Mann= 3 , 0 , 0
       0    .055       0   57.98     .04       0   75.93    .055       0
#XS Ineff= 2 , 0
    2.93   55.77    1.98   77.16    2.93    3.14
Permanent Ineff=
       F       F
Bank Sta=57.98,75.93
XS Rating Curve= 0 ,0
Exp/Cntr=0.5,0.3

Type RM Length L Ch R = 1 ,1047.01 ,53.72,42.98,45.75
XS GIS Cut Line= 6
      345345.453     5423523.043      345346.931     5423525.098
      345399.131      5423588.82      345443.606     5423623.533
       345475.05     5423633.312      345501.969       5423628.9
#Sta/Elev= 16
       0       6    1.57       5    3.86    3.32    7.41    2.13   36.39    2.17
   54.09     1.2   67.25     .75   69.79    1.27   71.39    1.41    81.3    4.39
   82.19    4.54   95.25    4.43  136.02    5.11  144.12    5.38  174.25    5.55
  201.53       6
#Mann= 3 , 0 , 0
       0    .055       0   54.09    .035       0   69.79    .055       0
Bank Sta=54.09,69.79
XS Rating Curve= 0 ,0
Exp/Cntr=0.3,0.1

Type RM Length L Ch R = 1 ,1004.03 ,33.48,44.82,43.49
XS GIS Cut Line= 6
      345286.098     5423540.982      345284.981     5423549.769
      345336.244     5423582.255      345400.947     5423648.475
      345443.145     5423624.111      345501.909     5423629.421
#Sta/Elev= 23
       0       6    5.38       5    8.86    4.04   11.31    3.83   24.33    3.24
   53.16    2.45   62.36    2.06   70.69    2.53   73.89     3.1   78.31    1.46
   79.25     1.2   79.94    1.11   89.91     .77   98.52    1.01   99.99    1.28
  104.45    2.08  114.63     3.2  135.47    4.21   196.7    5.18  201.44    5.19
  204.57     5.3  244.18    5.54  271.42       6
#Mann= 3 , 0 , 0
       0    .055       0   79.25    .035       0   99.99    .055       0
Bank Sta=79.25,99.99
XS Rating Curve= 0 ,0
Exp/Cntr=0.3,0.1

Type RM Length L Ch R = 1 ,959.21  ,44.89,43.46,56.67
XS GIS Cut Line= 6
       345262.09     5423547.921      345265.312     5423556.369
      345316.575     5423625.714      345365.337      5423672.88
      345426.915      5423708.49      345452.275     5423783.359
#Sta/Elev= 21
       0       6    3.29       5   12.02    4.13   20.24    4.44   22.48    4.66
   22.99    4.63   26.21    3.72   30.41    2.77   40.09    2.39   55.05    2.52
   96.16    1.19  100.23    1.05  104.66      .7  107.51     .88  109.37    1.24
  118.11       3   158.9    3.88  227.34    4.03  267.33    3.33  290.91    3.25
   313.3       6
#Mann= 3 , 0 , 0
       0    .055       0   96.16    .035       0  109.37    .055       0
Bank Sta=96.16,109.37
XS Rating Curve= 0 ,0
Exp/Cntr=0.3,0.1

Type RM Length L Ch R = 1 ,915.75  ,44.49,46.09,46.12
XS GIS Cut Line= 5
      345225.291      5423594.48      345278.116     5423638.211
      345303.747     5423693.187      345417.539     5423716.431
      345440.982     5423785.463
#Sta/Elev= 28
       0    8.24     .38    8.16     .85    7.87    1.26     7.8   10.17    4.01
   26.14    1.87    26.6    1.83   27.93    1.79   53.33    1.94      65    2.19
   68.58    1.99   80.48    1.26   88.41     .68   91.45    1.75   91.86    1.78
  100.19    2.32  125.11    3.05  129.23    3.03  183.83     3.5  208.97    3.54
  245.38    3.83  249.51    3.79  280.29    3.23  294.34     3.2  295.62    3.18
  311.51    5.01  315.71    5.99  318.28    6.06
#Mann= 3 , 0 , 0
       0    .055       0   80.48    .035       0   91.86    .055       0
Bank Sta=80.48,91.86
XS Rating Curve= 0 ,0
Exp/Cntr=0.3,0.1

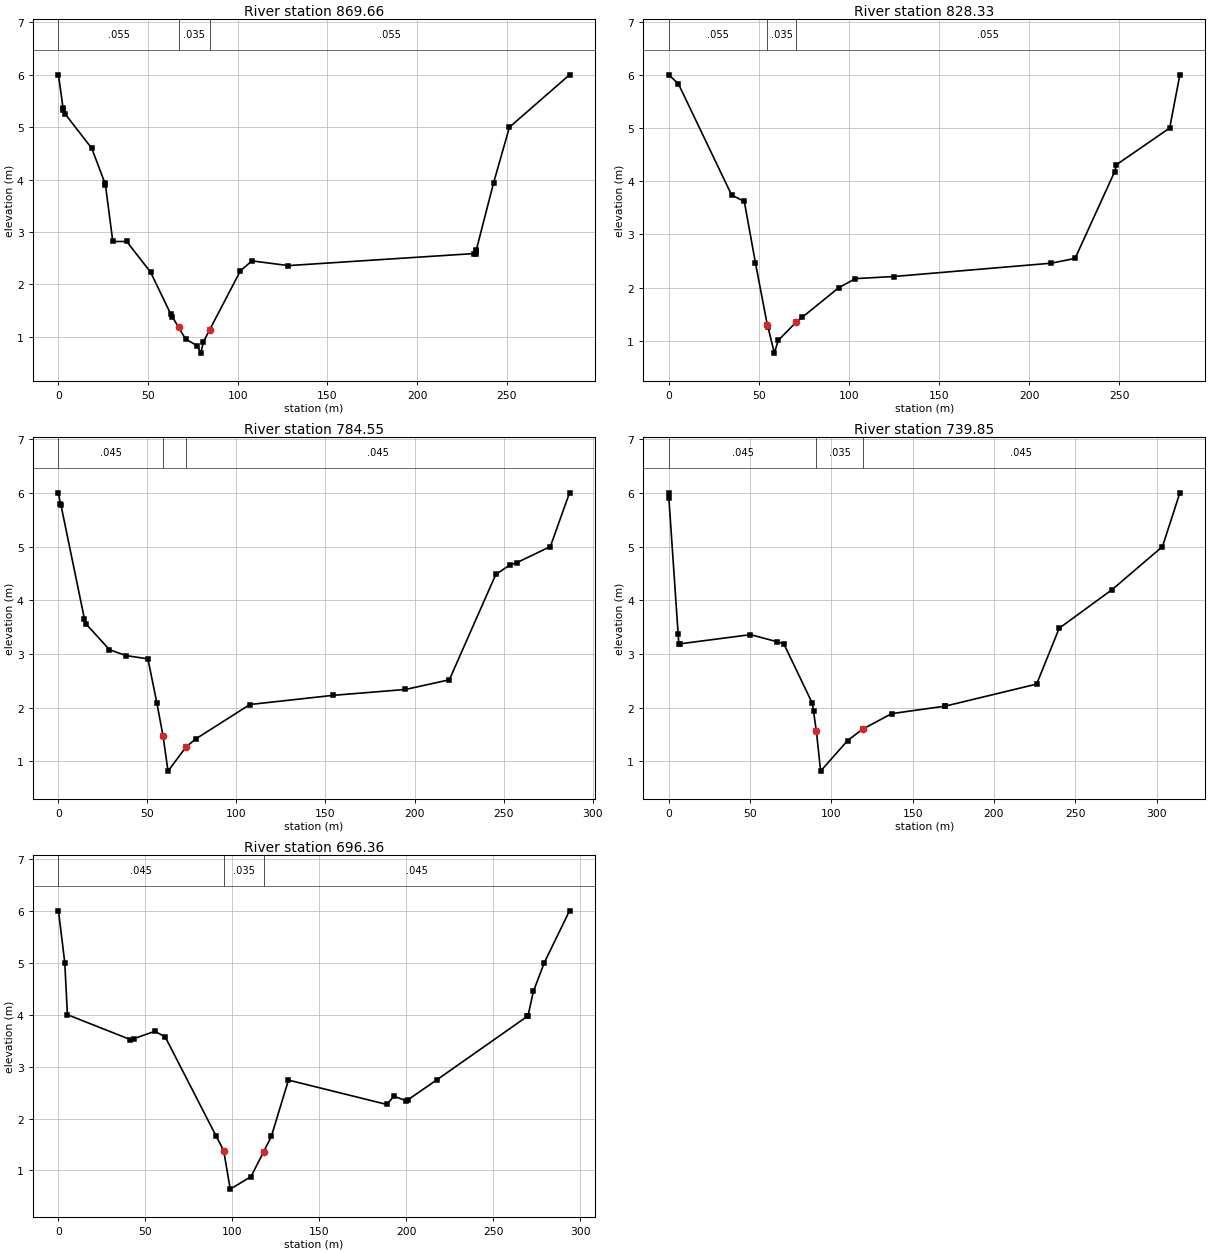
Type RM Length L Ch R = 1 ,869.66  ,42.02,41.32,31.8
XS GIS Cut Line= 5
      345192.565     5423620.154        345194.3      5423621.99
      345238.686     5423662.597      345266.505     5423721.946
       345387.72     5423821.424
#Sta/Elev= 28
       0       6    2.53    5.37    2.61    5.33    3.56    5.26   18.53     4.6
   25.83    3.94   26.23    3.89   30.31    2.82   38.07    2.82   51.46    2.23
   62.69    1.43   63.54    1.38   66.98   1.183   70.88     .96   77.41     .83
   79.44     .69   80.74      .9   84.36   1.137  101.47    2.26   107.9    2.45
  128.23    2.36  231.87    2.59  232.69    2.59  232.97    2.64  232.99    2.65
   242.7    3.94  251.52       5  285.04       6
#Mann= 3 , 0 , 0
       0    .055       0   66.98    .035       0   84.36    .055       0
Bank Sta=66.98,84.36
XS Rating Curve= 0 ,0
Exp/Cntr=0.3,0.1

Type RM Length L Ch R = 1 ,828.33  ,50.77,43.78,31.08
XS GIS Cut Line= 4
      345164.294     5423647.316      345168.009     5423651.144
      345249.904     5423738.293      345378.862     5423831.031
#Sta/Elev= 20
       0       6    5.33    5.83   34.89    3.74   41.92    3.62   48.13    2.46
   54.75    1.29   55.06    1.26   58.59     .77   60.77    1.01   70.65    1.35
   73.94    1.44   94.38       2  103.58    2.17  124.92    2.21  212.31    2.46
  225.59    2.55  247.57    4.18  248.51    4.31   278.1       5  283.77       6
#Mann= 3 , 0 , 0
       0    .055       0   54.75    .035       0   70.65    .055       0
Bank Sta=54.75,70.65
XS Rating Curve= 0 ,0
Exp/Cntr=0.3,0.1

Type RM Length L Ch R = 1 ,784.55  ,56.66,44.7,40.93
XS GIS Cut Line= 5
      345140.972     5423686.402       345141.44     5423687.378
      345158.944     5423719.864      345265.845     5423765.156
      345371.196     5423846.325
#Sta/Elev= 22
       0       6    1.08    5.79    1.41    5.77   14.55    3.66   15.48    3.56
   28.65    3.08   37.98    2.97   50.24    2.91   55.27    2.09   58.77    1.47
   61.54     .82   71.65    1.27   77.13    1.42  107.56    2.06  154.08    2.23
  194.93    2.34  219.57    2.52  245.66    4.48   253.7    4.66  257.47     4.7
  276.33       5  287.08       6
#Mann= 3 , 0 , 0
       0    .045       0   58.77    .035       0   71.65    .045       0
Bank Sta=58.77,71.65
XS Rating Curve= 0 ,0
Exp/Cntr=0.3,0.1

Type RM Length L Ch R = 1 ,739.85  ,37.83,43.49,53.15
XS GIS Cut Line= 4
      345076.712     5423735.284      345137.039     5423763.084
      345236.439     5423792.134      345351.066      5423879.91
#Sta/Elev= 22
       0       6     .02    5.91    5.71    3.38    6.21    3.18    6.96    3.19
   50.21    3.36   66.42    3.23   70.74    3.19   88.31    2.08   89.02    1.93
    90.8   1.558   93.38     .82     110    1.39  119.17     1.6  137.07    1.89
  169.98    2.03  170.06    2.03  226.25    2.44  240.15    3.48  272.74     4.2
  303.67       5  314.36       6
#Mann= 3 , 0 , 0
       0    .045       0    90.8    .035       0  119.17    .045       0
Bank Sta=90.8,119.17
XS Rating Curve= 0 ,0
Exp/Cntr=0.3,0.1

Type RM Length L Ch R = 1 ,696.36  ,64.23,36.99,20.23
XS GIS Cut Line= 4
      345063.287     5423758.789      345096.278     5423783.749
      345132.515     5423802.491      345321.259     5423898.327
#Sta/Elev= 24
       0       6    3.63       5    5.14       4   41.37    3.52   43.54    3.54
   55.45    3.68    61.4    3.57   90.68    1.66   95.01    1.38   98.76     .64
  110.67     .88  117.99    1.36  122.44    1.66  132.24    2.74  188.88    2.27
  192.82    2.43  200.02    2.34  200.92    2.36  217.79    2.75  269.67    3.97
  269.99    3.98  273.09    4.45  279.33       5  293.85       6
#Mann= 3 , 0 , 0
       0    .045       0   95.01    .035       0  117.99    .045       0
Bank Sta=95.01,117.99
XS Rating Curve= 0 ,0
Exp/Cntr=0.3,0.1

River Reach=CornerB         ,M001

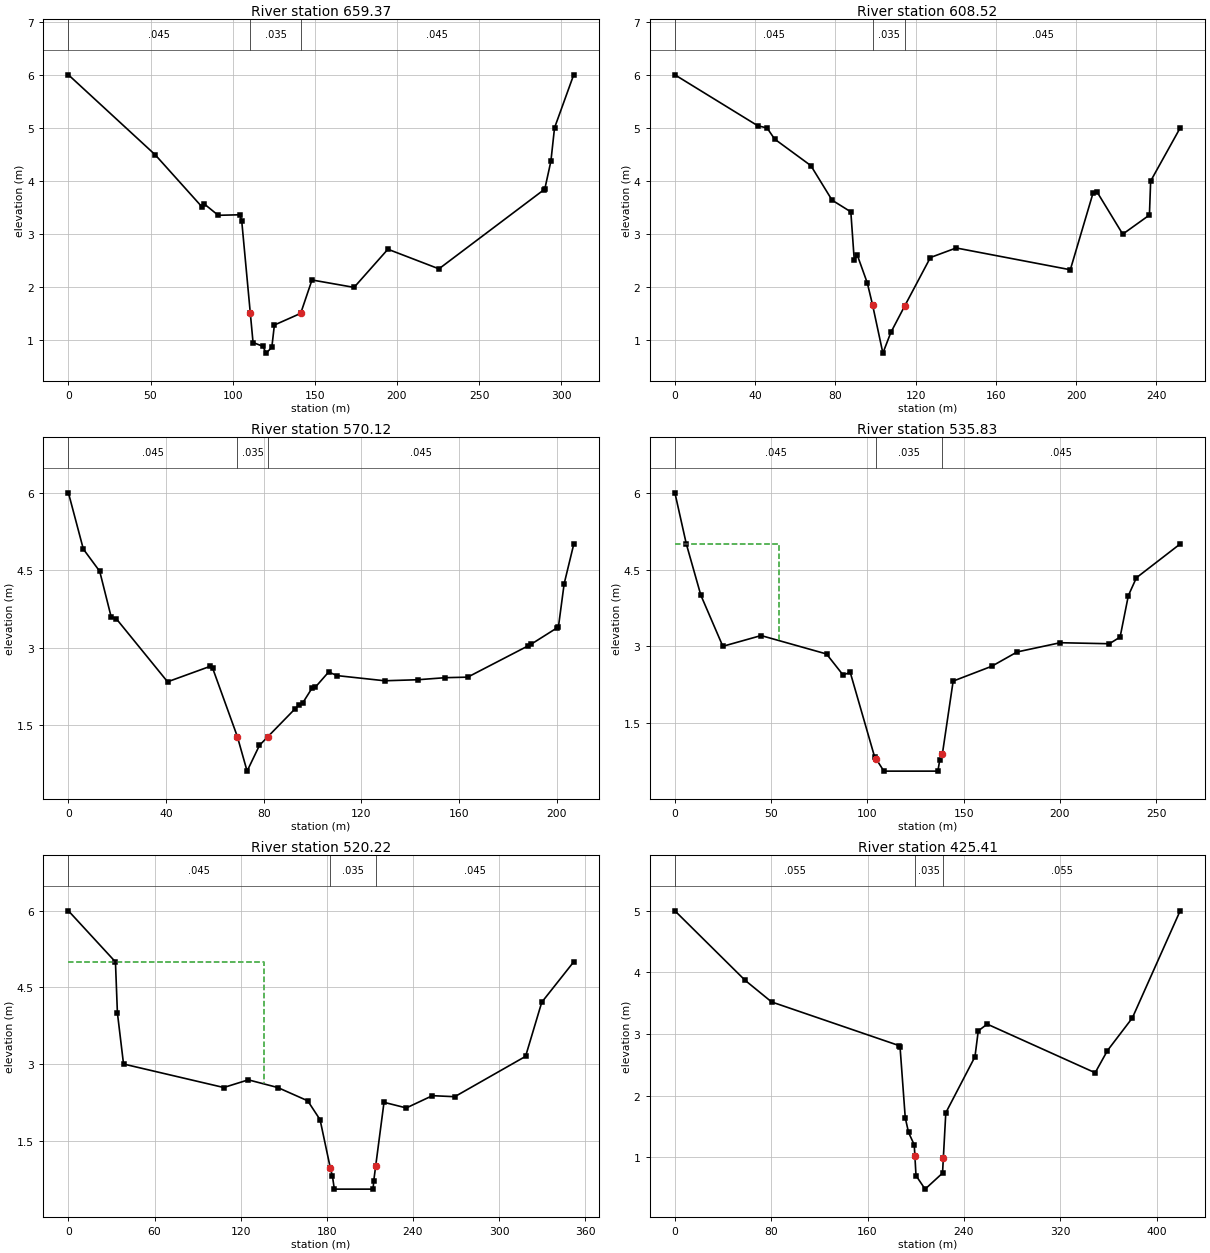
Type RM Length L Ch R = 1 ,659.37  ,6.01,15.44,16.77
XS GIS Cut Line= 6
      345019.923     5423888.005      345062.738     5423875.777
      345130.858       5423844.8      345159.361     5423841.647
      345204.919     5423855.768      345306.953     5423901.466
#Sta/Elev= 23
       0       6   52.88    4.49   81.27    3.51   82.46    3.57   91.21    3.35
  104.43    3.36  105.52    3.24  110.73   1.506   112.4     .95  118.32     .88
  120.42     .75  123.84     .86  125.39    1.28   141.4     1.5  148.29    2.13
  173.91    1.99  194.51    2.71  225.58    2.34  289.42    3.83  290.06    3.85
  293.74    4.37  295.96       5  307.62       6
#Mann= 3 , 0 , 0
       0    .045       0  110.73    .035       0   141.4    .045       0
Bank Sta=110.73,141.4
XS Rating Curve= 0 ,0
Exp/Cntr=0.3,0.1

Type RM Length L Ch R = 1 ,608.52  ,41.15,38.4,36.15
XS GIS Cut Line= 6
      345020.472     5423889.988      345061.819     5423890.967
      345102.693     5423890.907      345177.941      5423897.73
      345254.053     5423918.189      345265.011     5423928.885
#Sta/Elev= 23
       0       6   41.36    5.04   45.94       5   49.74    4.79    67.8    4.29
   78.37    3.64   87.72    3.42   89.41    2.52      91     2.6   95.94    2.08
   98.56   1.668   103.7     .76  107.68    1.15  114.64   1.652  127.39    2.56
  140.25    2.74  197.16    2.33  208.45    3.77   210.4     3.8  223.29       3
   236.6    3.36  237.21       4  251.92       5
#Mann= 3 , 0 , 0
       0    .045       0   98.56    .035       0  114.64    .045       0
Bank Sta=98.56,114.64
XS Rating Curve= 0 ,0
Exp/Cntr=0.3,0.1

Type RM Length L Ch R = 1 ,570.12  ,24.66,34.29,42.16
XS GIS Cut Line= 3
      345060.639     5423923.096      345070.954     5423931.842
      345264.424     5423933.617
#Sta/Elev= 29
       0       6    6.11    4.91   12.82    4.48   17.49     3.6   19.63    3.56
   40.62    2.34    58.1    2.64   59.04    2.61    69.2    1.28    73.2     .61
   78.27    1.11   81.71   1.277   92.91    1.82   94.33    1.89   95.97    1.93
   99.84    2.22  101.05    2.23  106.61    2.53  110.05    2.46  129.57    2.36
  143.11    2.38  154.45    2.42  163.57    2.43  188.48    3.04  189.63    3.07
  200.02    3.38  200.77    3.41   203.1    4.24     207       5
#Mann= 3 , 0 , 0
       0    .045       0    69.2    .035       0   81.71    .045       0
Bank Sta=69.2,81.71
XS Rating Curve= 0 ,0
Exp/Cntr=0.3,0.1

Type RM Length L Ch R = 1 ,535.83  ,15.48,15.61,15.92
XS GIS Cut Line= 6
      345041.667     5423921.564      345048.939     5423951.247
      345097.825      5423955.91      345179.627     5423978.872
      345254.305     5423970.477      345277.023      5423969.84
#Sta/Elev= 23
       0       6    5.94       5   13.47       4   24.91       3   44.79    3.21
   78.78    2.85   87.35    2.44    91.1    2.49  103.75     .84  104.68     .79
  108.59     .56  136.62     .56  137.63     .78  138.99      .9  144.57    2.32
  164.63    2.61  177.83    2.89  200.21    3.07  225.72    3.05  231.31    3.18
  235.59    3.99  239.78    4.34  262.51       5
#Mann= 3 , 0 , 0
       0    .045       0  104.68    .035       0  138.99    .045       0
#XS Ineff= 2 , 0
       0    54.3       5               0
Permanent Ineff=
       F       F
Bank Sta=104.68,138.99
XS Rating Curve= 0 ,0
Exp/Cntr=0.3,0.1

Type RM Length L Ch R = 1 ,520.22  ,48.43,48.15,48.46
XS GIS Cut Line= 6
      344948.158     5423933.212      344970.145     5423938.241
      344987.893     5423961.271      345093.136     5423970.747
      345200.729     5424001.107      345276.787     5423972.194
#Sta/Elev= 22
       0       6   32.75       5   34.12       4   38.38       3  108.19    2.54
  125.31    2.69  145.78    2.54  166.66    2.28  175.28    1.91  182.41    .966
  183.94      .8  185.21     .55  212.24     .55  212.62      .7  214.06    1.01
  219.82    2.25  235.36    2.14  253.53    2.38  269.09    2.36  318.43    3.15
  329.71    4.21  351.95       5
#Mann= 3 , 0 , 0
       0    .045       0  182.41    .035       0  214.06    .045       0
#XS Ineff= 2 , 0
       0   135.9       5               0
Permanent Ineff=
       F       F
Bank Sta=182.41,214.06
XS Rating Curve= 0 ,0
Exp/Cntr=0.3,0.1

Type RM Length L Ch R = 1 ,425.41  ,33.23,23.41,23.54
Node Photo=..\..\..\Corner Brook\Windshield Survey\CB photos\P1000632.JPG
XS GIS Cut Line= 6
      344912.125       5424006.5      344941.527     5424014.313
      344951.749     5424040.729      345053.649     5424047.601
      345212.438     5424119.444      345291.579     5424095.917
#Sta/Elev= 21
       0       5   58.39    3.87   80.33    3.52  186.34    2.81  186.98    2.79
   191.3    1.64  194.05     1.4  198.77     1.2  199.32   1.012  200.23      .7
  207.79     .48  222.27     .74  222.95     .99  224.98    1.72   249.2    2.63
  251.93    3.05  259.35    3.16  349.01    2.37  359.22    2.73  379.88    3.26
   419.6       5
#Mann= 3 , 0 , 0
       0    .055       0  199.32    .035       0  222.95    .055       0
Bank Sta=199.32,222.95
XS Rating Curve= 0 ,0
Exp/Cntr=0.3,0.1

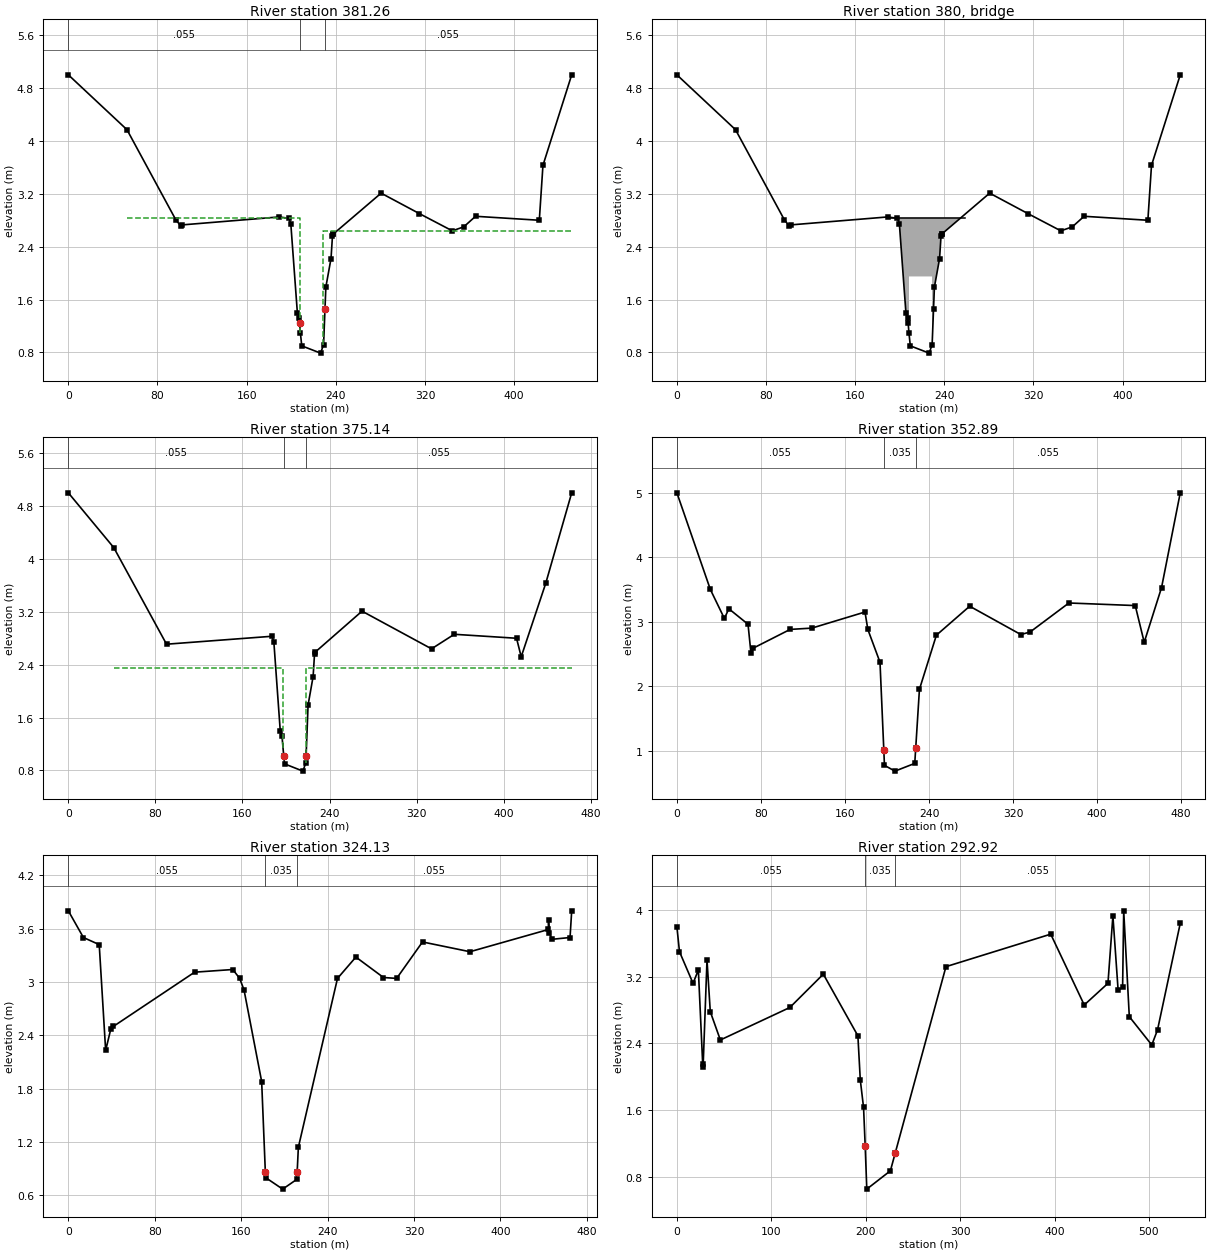
Type RM Length L Ch R = 1 ,381.26  ,7.2,7.2,7.2
Node Photo=..\..\..\Corner Brook\Windshield Survey\CB photos\P1000628.JPG
XS GIS Cut Line= 6
      344906.781       5424015.5      344934.904     5424020.931
      344938.538     5424044.632      344979.135     5424077.939
      345210.052     5424152.158       345309.16     5424121.075
#Sta/Elev= 29
       0       5   52.62    4.17   96.34    2.81  101.04    2.71  102.31    2.73
  189.03    2.85  197.87    2.83  199.63    2.75  205.53     1.4  207.13    1.32
   207.5    1.25  208.28    1.09  209.47      .9  226.38     .79  229.06     .92
  230.32    1.46   231.1    1.79  235.72    2.22  237.03    2.56  237.63    2.59
  237.64    2.59  280.68    3.21   315.1     2.9  344.56    2.64  354.82     2.7
  365.44    2.86  422.65     2.8  425.91    3.63  451.71       5
#Mann= 3 , 0 , 0
       0    .055       0   207.5    .035       0  230.32    .055       0
#XS Ineff= 2 , 0
   52.62  208.28    2.84  228.98   52.62    2.64
Permanent Ineff=
       F       F
Bank Sta=207.5,230.32
XS Rating Curve= 0 ,0
Exp/Cntr=0.5,0.3

Type RM Length L Ch R = 3 ,380     ,,,
Node Photo=..\..\..\Corner Brook\Windshield Survey\CB photos\P1000626.JPG
BEGIN DESCRIPTION:
Corner Brook Pulp & Paper #3 - Foot Bridge (Structure #2104)
END DESCRIPTION:
Bridge Culvert--1,0,-1,-1, 0
Deck Dist Width WeirC Skew NumUp NumDn MinLoCord MaxHiCord MaxSubmerge Is_Ogee
1.3,4,1.67,0, 6, 6, 2.64, , 0.98, 0, 0,0,,
  189.03  208.28  208.29  228.97  228.98  258.65
    2.84    2.84    2.84    2.84    2.84    2.84
      .9      .9    1.95    1.95      .9      .9
  178.22  197.47  197.48  218.16  218.17  247.84
    2.84    2.84    2.84    2.84    2.84    2.84
      .9      .9    1.95    1.95      .9      .9
BR Coef=-1 , 0 , 0 ,, 0 ,,,0.8,-1,,0,
WSPro=,,,, 1 ,,,, 0 ,,,, 0 ,,,,-1 ,-1 ,-1 , 0 , 0 , 0 , 0 , 0
BC Design=,, 0 ,, 0 ,,,,,,
BC Use User HTab Curves=0
BC User HTab FreeFlow(D)= 0

Type RM Length L Ch R = 1 ,375.14  ,22.33,22.25,22.11
Node Photo=..\..\..\Corner Brook\Windshield Survey\CB photos\P1000623.JPG
XS GIS Cut Line= 6
       344904.25       5424018.5      344926.692     5424022.519
      344929.243     5424041.353      344961.126     5424079.461
      345210.563     5424161.925      345313.322     5424129.032
#Sta/Elev= 23
       0       5   41.81    4.17   90.23    2.71  187.06    2.83  188.82    2.75
  194.72     1.4  196.32    1.32  197.94   1.015  198.66      .9  215.57     .79
  218.25     .92  218.48   1.019  220.29    1.79  224.91    2.22  226.22    2.56
  226.82    2.59  269.87    3.21  333.75    2.64  354.63    2.86  411.84     2.8
  416.13    2.52  438.65    3.63  462.52       5
#Mann= 3 , 0 , 0
       0    .055       0  197.94    .035       0  218.48    .055       0
#XS Ineff= 2 , 0
   41.81  197.47    2.35  218.17   41.81    2.35
Permanent Ineff=
       F       F
Bank Sta=197.94,218.48
XS Rating Curve= 0 ,0
Exp/Cntr=0.5,0.3

Type RM Length L Ch R = 1 ,352.89  ,29.06,28.77,28.44
Node Photo=..\..\..\..\Corner Brook\Windshield Survey\CB photos\P1000622.JPG
BEGIN DESCRIPTION:
Grade change in stream
END DESCRIPTION:
XS GIS Cut Line= 5
      344892.938       5424029.5      344899.236      5424060.72
      344968.628     5424104.451      345216.814     5424179.417
       345318.23     5424148.638
#Sta/Elev= 27
       0       5   31.85     3.5   45.19    3.05   49.47     3.2   67.71    2.96
   70.52    2.51   72.78    2.59  107.82    2.88  128.46     2.9  179.05    3.15
  181.74    2.88  193.33    2.37  196.94   1.014  197.56     .77  207.57     .68
  226.41      .8  227.35   1.042  230.87    1.95     247    2.79   278.7    3.24
   327.4     2.8  336.24    2.84  373.13    3.29  436.28    3.25  444.82    2.68
  461.33    3.53  479.12       5
#Mann= 3 , 0 , 0
       0    .055       0  196.94    .035       0  227.35    .055       0
Bank Sta=196.94,227.35
XS Rating Curve= 0 ,0
Exp/Cntr=0.3,0.1

Type RM Length L Ch R = 1 ,324.13  ,31.82,31.21,30.62
XS GIS Cut Line= 4
344888.6082763675424061.96929932344962.3762817385424133.18768311
345220.5648803715424209.40411377345308.7117309575424176.29370117
#Sta/Elev= 29
       0     3.8   13.94     3.5   28.59    3.42   34.54    2.23   39.29    2.47
   41.68     2.5  116.89    3.11  152.25    3.14  158.58    3.04  162.62    2.91
  178.94    1.88  182.35     .86  182.56      .8  198.39     .67  211.49     .78
   211.8    .859   212.9    1.14  249.12    3.04  266.15    3.28   291.7    3.05
  303.88    3.04  327.81    3.45  371.74    3.34  444.33    3.59  444.45     3.7
  445.07    3.55  447.87    3.48  464.37     3.5   465.9     3.8
#Mann= 3 , 0 , 0
       0    .055       0  182.35    .035       0   211.8    .055       0
Bank Sta=182.35,211.8
XS Rating Curve= 0 ,0
Exp/Cntr=0.3,0.1

Type RM Length L Ch R = 1 ,292.92  ,27.57,18.3,8.5
XS GIS Cut Line= 6
 344882.333923345424066.41009521344951.7260742195424163.86712646
345107.3892822275424207.59771729345131.3881225595424222.67687988
345275.7416992195424249.74768066345338.8267211915424206.36010742
#Sta/Elev= 30
       0     3.8    2.73     3.5   17.11    3.12   22.75    3.28   27.45    2.12
   27.87    2.15   31.89     3.4   35.37    2.78   46.02    2.44  119.64    2.83
  155.08    3.23  191.69    2.49  194.24    1.96   197.7    1.63  199.44   1.165
  201.12     .65  226.12     .87  231.16    1.08  284.97    3.32  395.93    3.71
  431.43    2.86  456.54    3.12  461.77    3.93  467.28    3.04  472.05    3.07
  473.22    3.99  479.15    2.72  502.95    2.38  509.01    2.56   533.1    3.84
#Mann= 3 , 0 , 0
       0    .055       0  199.44    .035       0  231.16    .055       0
Bank Sta=199.44,231.16
XS Rating Curve= 0 ,0
Exp/Cntr=0.3,0.1