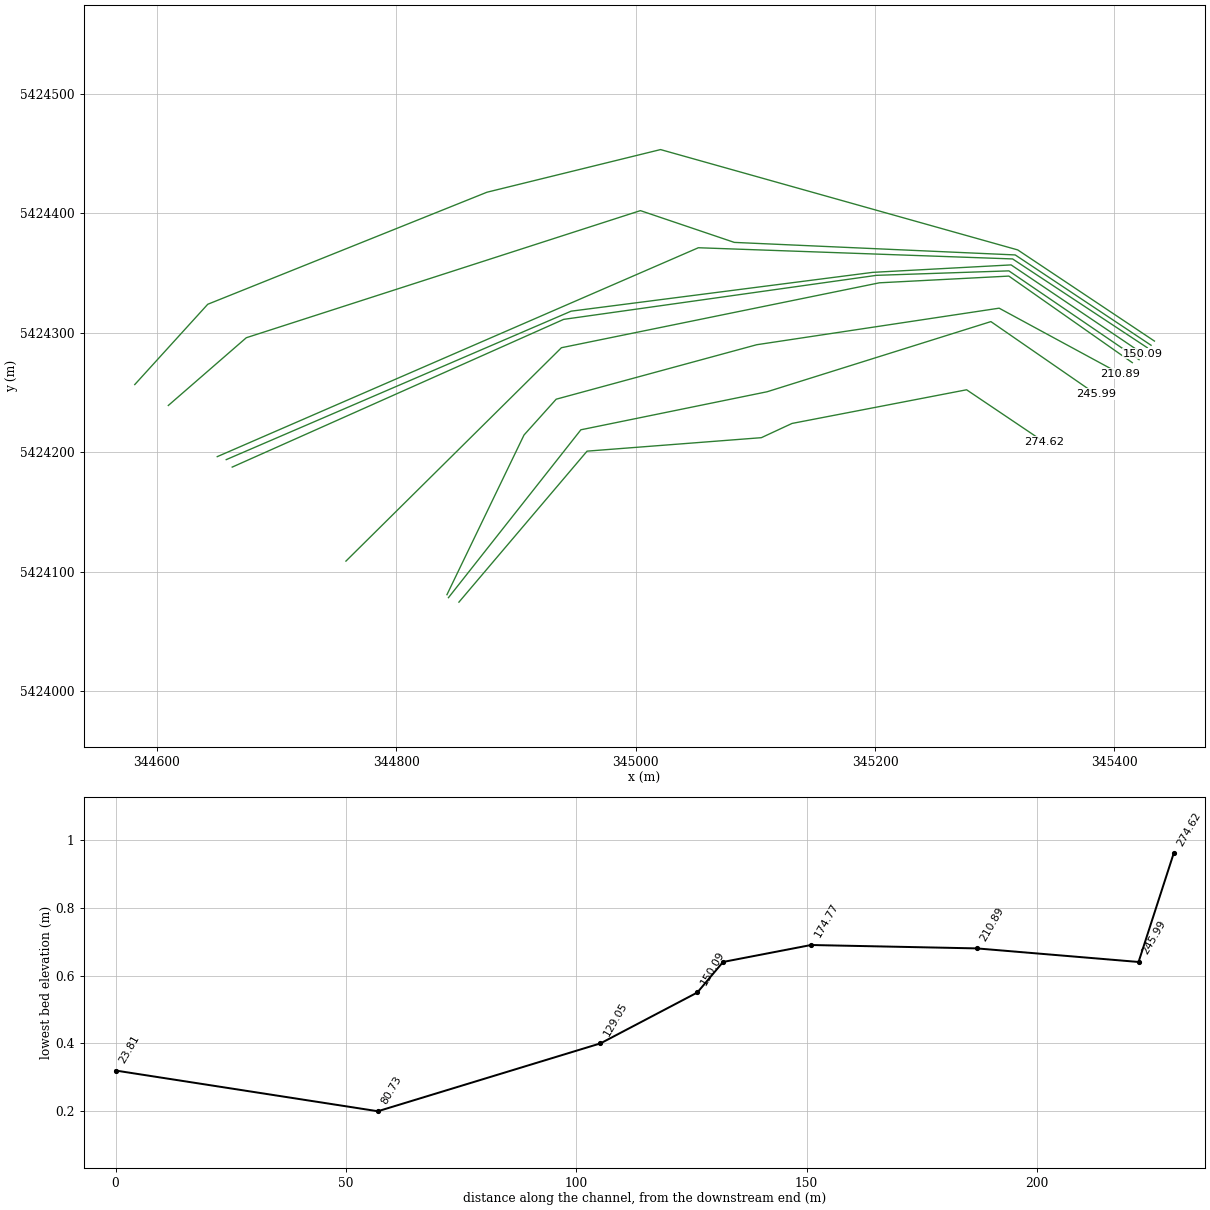
HEC-RAS study Corner_Brook2.prj: Corner_Brook2

--- Corner_Brook2.g03 (geometry) --- (continued)

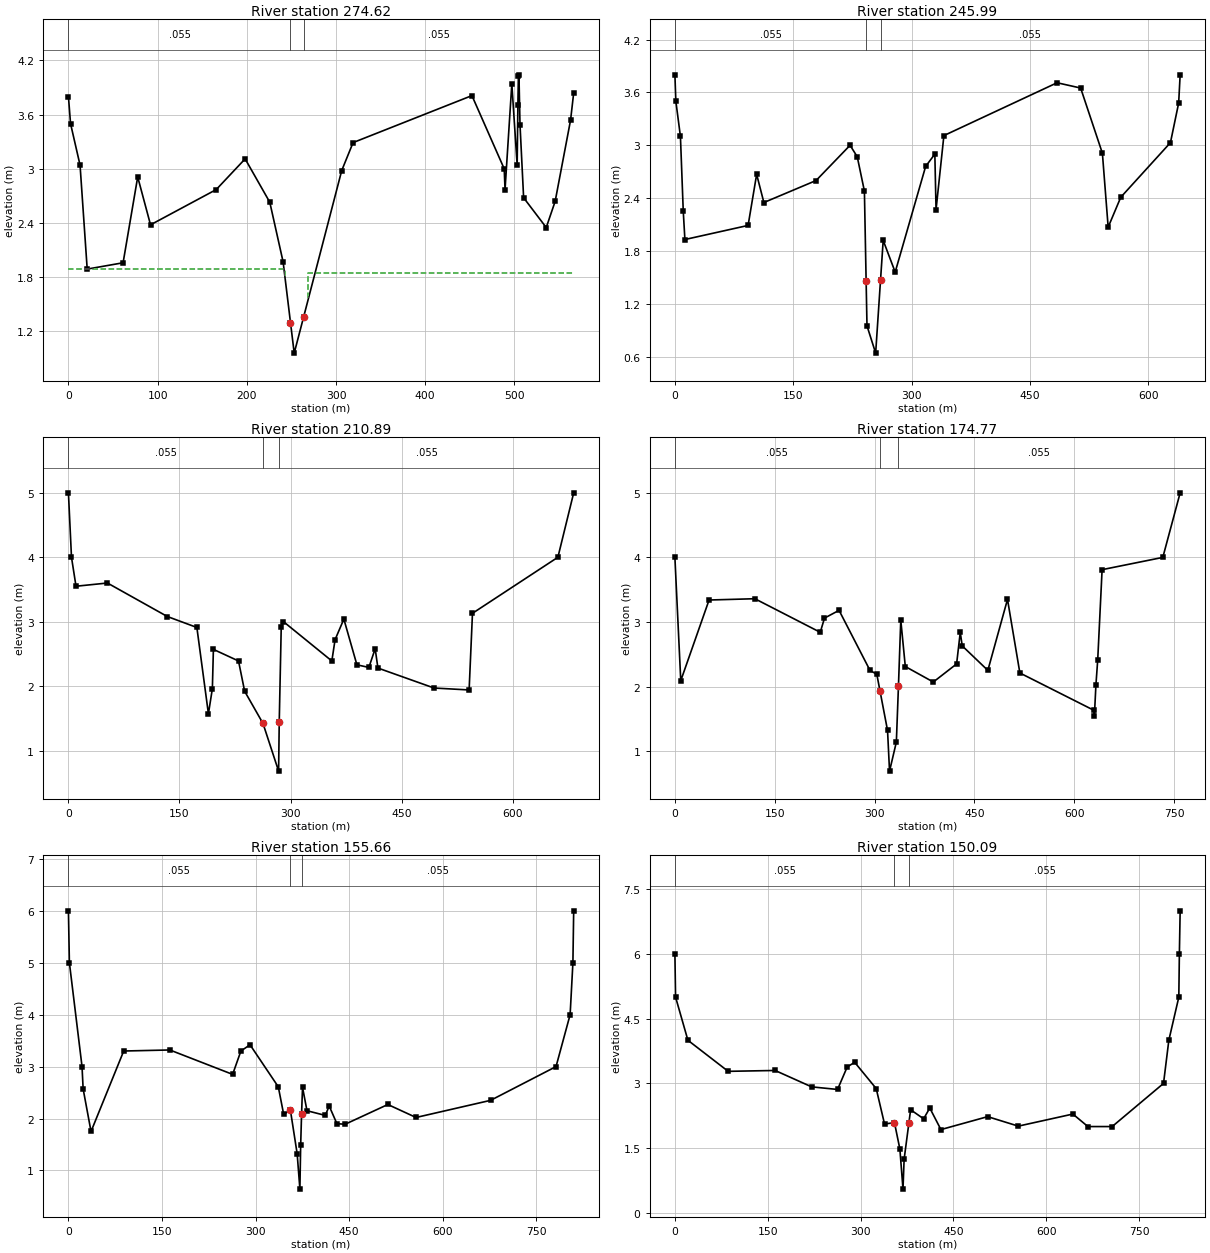
Type RM Length L Ch R = 1 ,274.62  ,7.58,7.62,7.75
Node Photo=..\..\..\..\Corner Brook\Windshield Survey\CB photos\P1000620.JPG
XS GIS Cut Line= 6
344852.3264770515424074.53149414344959.4033203135424200.96429443
345105.0242919925424212.23687744345130.6458740235424224.16027832
345276.4838867195424252.34350586345341.0532836915424208.77050781
#Sta/Elev= 30
       0     3.8    2.37     3.5   13.04    3.04   21.04    1.89   61.28    1.96
   77.66    2.91   92.03    2.38  165.68    2.77  198.09    3.11  225.74    2.63
  240.67    1.97  248.95   1.298  253.11     .96  263.72   1.362  306.36    2.98
   319.1    3.29  452.36    3.81  488.54       3  489.47    2.77  497.08    3.94
  503.06    3.04  503.88    3.71  504.45    4.03  505.06    4.04  506.24    3.49
   510.3    2.68  535.66    2.35  545.66    2.64  562.95    3.54  566.43    3.84
#Mann= 3 , 0 , 0
       0    .055       0  248.95    .035       0  263.72    .055       0
#XS Ineff= 2 , 0
       0  242.99    1.89  269.06       0    1.85
Permanent Ineff=
       F       F
Bank Sta=248.95,263.72
XS Rating Curve= 0 ,0
Exp/Cntr=0.5,0.3

Type RM Length L Ch R = 1 ,245.99  ,31.94,35.1,38.27
XS GIS Cut Line= 5
      344843.574      5424078.28      344954.227     5424218.843
       345109.89     5424250.704      345296.811     5424309.428
      345384.333      5424248.83
#Sta/Elev= 30
       0     3.8     1.2     3.5    7.02     3.1    10.6    2.25   12.67    1.93
   92.75    2.09  103.58    2.67  112.74    2.35  178.89     2.6  221.94       3
  231.03    2.87  240.11    2.48  242.29   1.458  243.38     .95  254.36     .64
  260.54    1.47  263.91    1.92   279.1    1.56  317.69    2.76  329.35     2.9
  330.88    2.27  340.82    3.11  484.25    3.71  514.08    3.65  541.63    2.91
  548.95    2.07  564.92    2.41  627.86    3.03  638.27    3.48  640.16     3.8
#Mann= 3 , 0 , 0
       0    .055       0  242.29    .035       0  260.54    .055       0
Bank Sta=242.29,260.54
XS Rating Curve= 0 ,0
Exp/Cntr=0.3,0.1

Type RM Length L Ch R = 1 ,210.89  ,38.68,35.99,33.1
XS GIS Cut Line= 6
      344842.324     5424080.779      344906.715      5424214.47
      344933.596     5424244.456      345101.138     5424290.061
      345303.688     5424320.673      345404.963     5424265.697
#Sta/Elev= 28
       0       5    4.13       4   10.23    3.55   52.68     3.6  133.57    3.08
  173.47    2.91  189.06    1.57   194.4    1.96  195.79    2.57  229.71    2.39
  237.99    1.92  262.78    1.42  283.86     .68   284.7   1.438  287.41    2.92
  290.45       3  355.75    2.39  360.11    2.72  371.98    3.04  389.61    2.33
  405.78    2.29  414.27    2.58  417.98    2.28  493.81    1.97  541.16    1.94
  545.69    3.13  661.06       4  682.38       5
#Mann= 3 , 0 , 0
       0    .055       0  262.78    .035       0   284.7    .055       0
Bank Sta=262.78,284.7
XS Rating Curve= 0 ,0
Exp/Cntr=0.3,0.1

Type RM Length L Ch R = 1 ,174.77  ,22.25,19.11,16.6
XS GIS Cut Line= 5
      344757.928     5424108.891      344937.972     5424287.562
      345203.663     5424341.913      345311.815     5424347.536
      345414.965     5424275.068
#Sta/Elev= 30
       0       4    8.81    2.09   51.34    3.34  120.15    3.36  218.42    2.84
  224.78    3.06  246.67    3.18  293.16    2.25   303.4    2.19  308.15   1.934
  319.52    1.32  322.52     .69  332.76    1.14  335.93    2.01  339.41    3.03
  346.21    2.31   388.3    2.07  423.29    2.35  428.78    2.84  431.71    2.63
  470.25    2.25  499.77    3.35  518.36    2.21  629.98    1.63  630.35    1.55
  632.66    2.03  635.32    2.41  641.92    3.81  733.15       4   759.2       5
#Mann= 3 , 0 , 0
       0    .055       0  308.15    .035       0  335.93    .055       0
Bank Sta=308.15,335.93
XS Rating Curve= 0 ,0
Exp/Cntr=0.3,0.1

Type RM Length L Ch R = 1 ,155.66  ,6.01,5.58,5.11
Node Photo=..\..\..\Corner Brook\Windshield Survey\CB photos\P1000612.JPG
XS GIS Cut Line= 5
      344662.905     5424187.607      344939.848     5424311.302
      345201.162     5424348.161      345311.815     5424351.909
      345420.591     5424277.567
#Sta/Elev= 30
       0       6    1.54       5    21.8       3   23.57    2.57   36.22    1.75
   88.59     3.3   162.5    3.32  263.15    2.85  276.38     3.3  291.02    3.42
  336.33    2.61  344.93    2.08  355.72    2.16  366.56    1.32  370.92     .64
  372.17   1.483  373.59    2.08  375.16     2.6  382.29    2.15  411.58    2.06
  417.88    2.24  430.26     1.9  443.51    1.89  511.86    2.27  557.05    2.02
  676.56    2.35  781.39       3  803.97       4  808.43       5  809.68       6
#Mann= 3 , 0 , 0
       0    .055       0  355.72    .035       0  373.59    .055       0
#XS Ineff= 2 , 0
       0  355.72    2.08  373.59       0    1.89
Permanent Ineff=
       F       F
Bank Sta=355.72,373.59
XS Rating Curve= 0 ,0
Exp/Cntr=0.4,0.2

Type RM Length L Ch R = 1 ,150.09  ,8.19,21.03,33.59
Node Photo=..\..\..\Corner Brook\Windshield Survey\CB photos\P1000610.JPG
XS GIS Cut Line= 5
      344657.904     5424193.854      344946.099     5424318.174
      345198.037     5424350.659       345313.69     5424356.907
      345423.717     5424282.565
#Sta/Elev= 30
       0       6     1.1       5   21.03       4   86.09    3.28  161.96     3.3
  221.01    2.92  262.85    2.86   278.4    3.38  290.49    3.49  325.33    2.88
  338.75    2.06  354.83    2.09  363.56    1.48  368.61     .55  370.41    1.24
  378.07   2.077  380.93    2.39  401.95    2.18   411.9    2.43  429.89    1.93
  505.42    2.23  554.96    2.01  643.15    2.29  667.43       2  706.63       2
  789.62       3  798.21       4  814.33       5  815.24       6   816.5       7
#Mann= 3 , 0 , 0
       0    .055       0  354.83    .035       0  378.07    .055       0
#XS Ineff= 2 , 0
       0  354.83    2.06  378.07       0    1.91
Permanent Ineff=
       F       F
Bank Sta=354.83,378.07
XS Rating Curve= 0 ,0
Exp/Cntr=0.4,0.2

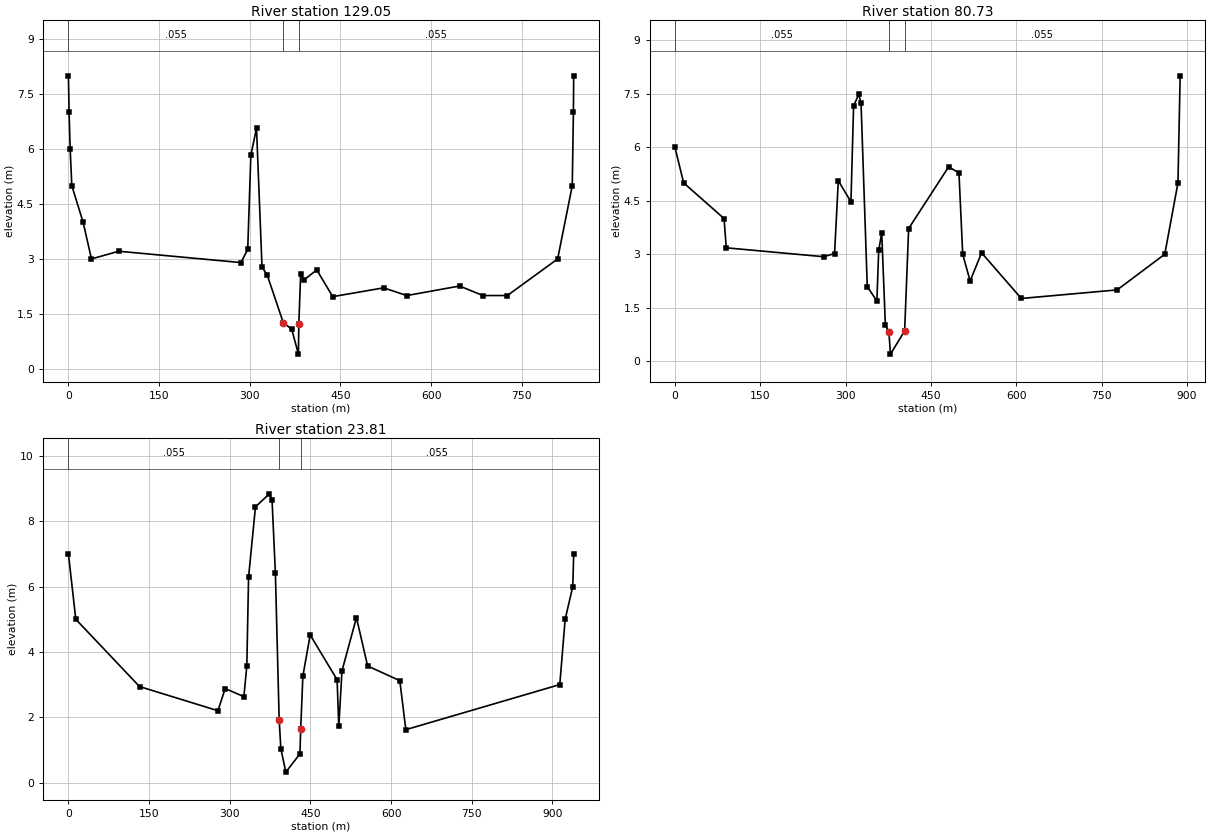
Type RM Length L Ch R = 1 ,129.05  ,48.12,48.32,47.32
XS GIS Cut Line= 5
      344650.402     5424196.353      344946.099     5424325.046
      345052.376     5424371.275       345314.94     5424361.904
      345427.468     5424287.562
#Sta/Elev= 30
       0       8    1.08       7     2.9       6    5.57       5   24.33       4
   38.08       3   83.26    3.21  285.42     2.9  296.64    3.26  301.83    5.83
   311.2    6.57   320.3    2.78  329.09    2.55  355.45    1.26  369.46    1.08
  380.53      .4  381.21   1.234  384.24    2.58  390.04    2.43  410.86     2.7
  437.31    1.97   521.5    2.21  559.94       2  647.23    2.26  685.77       2
  726.23       2  809.44       3  833.62       5  835.52       7  835.98       8
#Mann= 3 , 0 , 0
       0    .055       0  355.45    .035       0  381.21    .055       0
Bank Sta=355.45,381.21
XS Rating Curve= 0 ,0
Exp/Cntr=0.3,0.1

Type RM Length L Ch R = 1 ,80.73   ,61.44,56.94,50.51
XS GIS Cut Line= 6
      344609.509     5424239.208      344674.667     5424295.925
      345003.964     5424402.357      345082.434     5424375.749
      345317.145     5424365.246      345430.647     5424289.623
#Sta/Elev= 30
       0       6   15.38       5   86.42       4   90.25    3.18  261.49    2.93
  280.63    3.02  287.18    5.06   309.4    4.47  314.06    7.16  323.23    7.48
  327.16    7.23   338.1    2.09  354.99    1.69  358.19    3.11  363.51     3.6
  369.86    1.03  376.11     .81  378.91      .2  403.76     .85  410.81    3.72
  481.14    5.45  499.25    5.28  505.82       3  518.84    2.25     539    3.04
  608.87    1.76  777.28       2  860.94       3  884.12       5  887.98       8
#Mann= 3 , 0 , 0
       0    .055       0  376.11    .035       0  403.76    .055       0
Bank Sta=376.11,403.76
XS Rating Curve= 0 ,0
Exp/Cntr=0.3,0.1

Type RM Length L Ch R = 1 ,23.81   ,26,23.8,24.26
XS GIS Cut Line= 6
      344581.484     5424256.713      344642.438     5424323.933
      344875.748     5424417.761      345020.779     5424453.472
      345319.247     5424369.447       345433.45     5424293.124
#Sta/Elev= 30
       0       7   13.67       5  132.18    2.94  278.01     2.2   291.5    2.88
  326.26    2.63  331.69    3.57  334.97    6.29  347.76    8.44  373.57    8.84
  378.62    8.65  384.84    6.41  391.86    1.93  394.97    1.04  404.26     .32
  430.52     .88  431.89    1.65  435.95    3.26  449.49    4.52  499.58    3.15
  502.73    1.72  508.67    3.42  535.57    5.05  556.33    3.57   616.2    3.12
  627.38    1.62  913.66       3  923.64       5  937.79       6  939.51       7
#Mann= 3 , 0 , 0
       0    .055       0  391.86    .035       0  431.89    .055       0
Bank Sta=391.86,431.89
XS Rating Curve= 0 ,0
Exp/Cntr=0.3,0.1